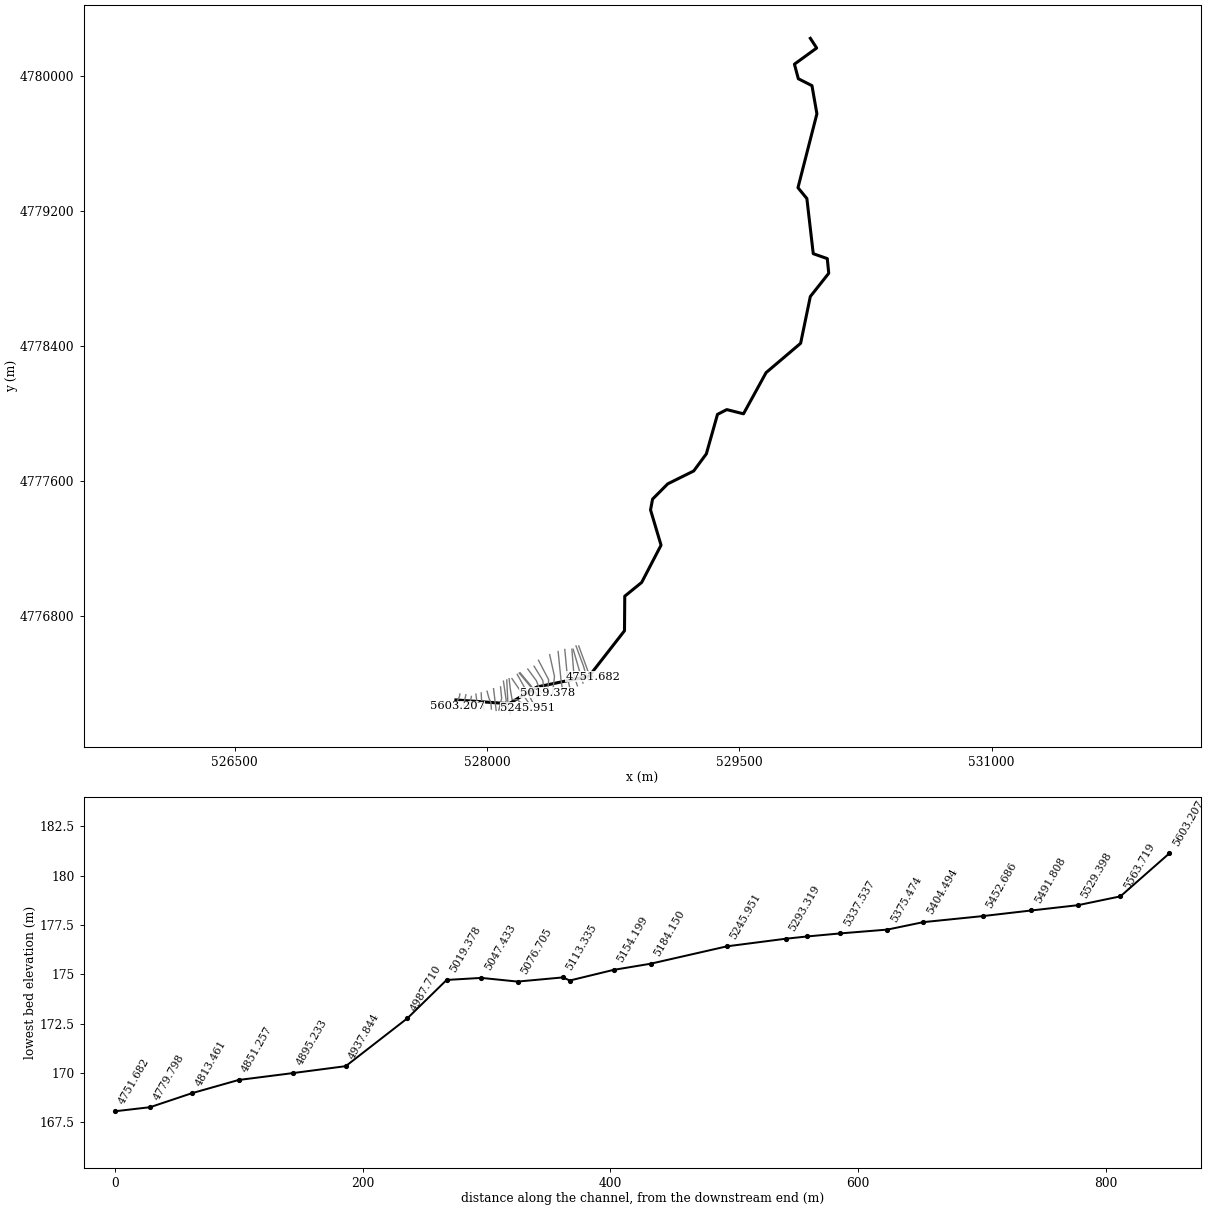
--- Durango.prj (project) ---

Proj Title=Durango
Current Plan=p17
Default Exp/Contr=0.3,0.1
SI Units
Geom File=g10
Geom File=g18
Geom File=g19
Geom File=g20
Flow File=f08
Flow File=f10
Plan File=p12
Plan File=p17
Plan File=p18
Plan File=p01
Y Axis Title=Elevation
X Axis Title(PF)=Main Channel Distance
X Axis Title(XS)=Station
BEGIN DESCRIPTION:
END DESCRIPTION:
DSS File=dss
DSS Export Rating Curves= 0
DSS Export Rating Curve Sorted= 0
DSS Export Volume Flow Curves= 0
DXF OffsetX= 0
DXF OffsetY= 0
DXF ScaleX= 1
DXF ScaleY= 10

--- Durango.p17 (plan) ---

Plan Title=ZALDEI T500 IBAIZABAL T500 visor
Program Version=4.10
Short Identifier=T500VISOR
Geom File=g18
Flow File=f10
Subcritical Flow
K Sum by GR= 0
Std Step Tol= 0.003
Critical Tol= 0.003
Num of Std Step Trials= 20
Max Error Tol= 0.1
Flow Tol Ratio= 0.001
Split Flow NTrial= 30
Split Flow Tol= 0.006
Split Flow Ratio= 0.02
Log Output Level= 0
Friction Slope Method= 1
Unsteady Friction Slope Method= 2
Unsteady Bridges Friction Slope Method= 1
Parabolic Critical Depth
Global Vel Dist= 5 , 5 , 5
Global Log Level= 0
CheckData=Verdadero
Encroach Param=-1 ,0,0, 0
Computation Interval=1HOUR
Output Interval=1HOUR
Run HTab= 0
Run UNet= 0
Run PostProcess= 0
Run WQNet= 0
UNET Theta= 1
UNET Theta Warmup= 1
UNET ZTol= 0.006
UNET ZSATol= 0.015
UNET MxIter= 20
UNET MaxInSteps= 0
UNET DtIC= 0
UNET DtMin= 0
UNET MaxCRTS= 20
UNET WFStab= 2
UNET SFStab= 1
UNET WFX= 1
UNET SFX= 1
UNET DSS MLevel= 4
UNET DZMax Abort= 30
UNET Convert EG Bridges= 0
UNET Use Existing IB Tables=-1
UNET Froude Reduction=Falso
UNET Froude Limit= 1
UNET Froude Power= 10
UNET Time Slicing=0,0, 5
UNET Junction Losses=0
Instantaneous Interval=1HOUR
Write IC File= 0
Write IC File at Sim End=0
Echo Input=Falso
Echo Parameters=Falso
Echo Output=Falso
Write Detailed= 0
WQ AD Non Conservative
WQ ULTIMATE=-1
WQ Max Comp Step=1HOUR
WQ Output Interval=15MIN
WQ Output Selected Increments= 0
WQ Output face flow=0
WQ Output face velocity=0
WQ Output face area=0
WQ Output face dispersion=0
WQ Output cell volume=0
WQ Output cell surface area=0
WQ Output cell continuity=0
WQ Output cumulative cell continuity=0
WQ Output face conc=0
WQ Output face dconc_dx=0
WQ Output face courant=0
WQ Output face peclet=0
WQ Output face adv mass=0
WQ Output face disp mass=0
WQ Output cell mass=0
WQ Output cell source sink temp=0
WQ Output cell source sink nsm=0
WQ Output MaxMinRange=-1
WQ Daily Max Min Mean=-1
WQ Daily Range=0
WQ Daily Time=0
WQ Create Restart=0
WQ Fixed Restart=0
WQ System Summary=0
WQ Use Fixed Temperature=0
Sorting and Armoring Iterations= 10
XS Update Threshold= 0.02
Hydraulics Update Threshold= 0.02
Energy Slope Method= 1
Volume Change Method= 0
XS Weighting Method= 0
Number of US Weighted Cross Sections= 1
Number of DS Weighted Cross Sections= 1
Upstream XS Weight=0.25
Main XS Weight=0.5
Downstream XS Weight=0.25
Number of DS XS's Weighted with US Boundary= 1
Upstream Boundary Weight= 1
Weight of XSs Associated with US Boundary= 0
Number of US XS's Weighted with DS Boundary= 1
Downstream Boundary Weight= 0.5
Weight of XSs Associated with DS Boundary= 0.5
Sediment Output Level= 4
Mass or Volume Output= 0
Output Increment Type= 1
Profile and TS Output Increment= 10
XS Output Flag= 0
XS Output Increment= 10
Disregard all LS=0
Disregard all Conn=0
Disregard all Breaches=0
Disregard all Pumps=0

--- Durango.p01 (plan) ---

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Plan Title=ZALDEI T100 IBAIZABAL T100 visor VID
Short Identifier=VID
Geom File=g20
Flow File=f08
Global Vel Dist= 0 , 0 , 0
CheckData=True
UNET Froude Reduction=False
Echo Input=False
Echo Parameters=False
Echo Output=False

--- Durango.p12 (plan) ---

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Plan Title=ZALDEI T100 IBAIZABAL T100 visor
Short Identifier=T100 visor
Geom File=g10
Flow File=f08
CheckData=True
UNET Froude Reduction=False
Echo Input=False
Echo Parameters=False
Echo Output=False

--- Durango.p18 (plan) ---

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Plan Title=ZALDEI T500 IBAIZABAL T500 visor URBAN
Short Identifier=T500VisorUrban
Geom File=g19
Flow File=f10

--- Durango.f10 (steady flow) ---

Flow Title=ZALDEI T500 - IBAIZABAL T500 visor
Program Version=4.10
Number of Profiles= 1
Profile Names=T500
River Rch & RM=CORTA,MANA            ,244
      .1
River Rch & RM=IBAIZABAL,IBAIZABAL-103   ,8399.296
     456
River Rch & RM=IBAIZABAL,IBAIZABAL-102   ,6903.275
     456
River Rch & RM=IBAIZABAL,IBAIZABAL-101   ,6688.85
     456
River Rch & RM=IBAIZABAL,IBAIZABAL-100   ,6400.460
     456
River Rch & RM=IBAIZABAL,IBAIZABAL-100   ,5761.419
     456
River Rch & RM=MAÑARIA,MAÑARIA-100     ,5603.207
     145
River Rch & RM=ZALDEI,ZALDEI          ,1634.223
      44
Boundary for River Rch & Prof#=ZALDEI,ZALDEI          , 1
Up Type= 3
Up Slope=0.0176
Dn Type= 0
Boundary for River Rch & Prof#=AFIBI100,AFIBI100-100    , 1
Up Type= 3
Up Slope=0.011
Dn Type= 0
Boundary for River Rch & Prof#=IBAIZABAL,IBAIZABAL-103   , 1
Up Type= 3
Up Slope=0.00182
Dn Type= 0
Boundary for River Rch & Prof#=IBAIZABAL,IBAIZABAL-102   , 1
Up Type= 0
Dn Type= 0
Boundary for River Rch & Prof#=IBAIZABAL,IBAIZABAL-101   , 1
Up Type= 0
Dn Type= 0
Boundary for River Rch & Prof#=IBAIZABAL,IBAIZABAL-100   , 1
Up Type= 0
Dn Type= 3
Dn Slope=0.002
Boundary for River Rch & Prof#=MAÑARIA,MAÑARIA-100     , 1
Up Type= 2
Dn Type= 0
Boundary for River Rch & Prof#=IBAIZABAL  B,IBAIZABAL-103 B , 1
Up Type= 0
Dn Type= 3
Dn Slope=0.002
DSS Import GetInterval= 0
DSS Import GetPeak= 0
DSS Import FillOption= 0

--- Durango.f08 (steady flow) ---

Flow Title=ZALDEI T100 - IBAIZABAL T100 visor
Program Version=4.10
Number of Profiles= 1
Profile Names=T100
River Rch & RM=CORTA,MANA            ,244
      .1
River Rch & RM=IBAIZABAL,IBAIZABAL-103   ,8399.296
     347
River Rch & RM=IBAIZABAL,IBAIZABAL-102   ,6903.275
     347
River Rch & RM=IBAIZABAL,IBAIZABAL-101   ,6688.85
     347
River Rch & RM=IBAIZABAL,IBAIZABAL-100   ,6400.460
     347
River Rch & RM=IBAIZABAL,IBAIZABAL-100   ,5761.419
     347
River Rch & RM=MAÑARIA,MAÑARIA-100     ,5603.207
      95
River Rch & RM=ZALDEI,ZALDEI          ,1634.223
      30
Boundary for River Rch & Prof#=ZALDEI,ZALDEI          , 1
Up Type= 3
Up Slope=0.0176
Dn Type= 0
Boundary for River Rch & Prof#=AFIBI100,AFIBI100-100    , 1
Up Type= 3
Up Slope=0.011
Dn Type= 0
Boundary for River Rch & Prof#=IBAIZABAL,IBAIZABAL-103   , 1
Up Type= 3
Up Slope=0.00182
Dn Type= 0
Boundary for River Rch & Prof#=IBAIZABAL,IBAIZABAL-102   , 1
Up Type= 0
Dn Type= 0
Boundary for River Rch & Prof#=IBAIZABAL,IBAIZABAL-101   , 1
Up Type= 0
Dn Type= 0
Boundary for River Rch & Prof#=IBAIZABAL,IBAIZABAL-100   , 1
Up Type= 0
Dn Type= 3
Dn Slope=0.002
Boundary for River Rch & Prof#=MAÑARIA,MAÑARIA-100     , 1
Up Type= 2
Dn Type= 0
Boundary for River Rch & Prof#=IBAIZABAL  B,IBAIZABAL-103 B , 1
Up Type= 0
Dn Type= 3
Dn Slope=0.002
DSS Import GetInterval= 0
DSS Import GetPeak= 0
DSS Import FillOption= 0

--- Durango.g18 (geometry) ---

Geom Title=ZALDEI T500 - IBAIZ T500 visor
Program Version=4.10

Junct Name=9
Junct Desc=, 0 , 0 ,-1 ,0
Up River,Reach=ZALDEI          ,ZALDEI
Up River,Reach=IBAIZABAL       ,IBAIZABAL-102
Dn River,Reach=IBAIZABAL       ,IBAIZABAL-101
Junc L&A=10.593,0
Junc L&A=140.584,0

Junct Name=3
Junct Desc=, 0 , 0 ,-1 ,0
Up River,Reach=IBAIZABAL       ,IBAIZABAL-103
Up River,Reach=MAÑARIA         ,MAÑARIA-100
Dn River,Reach=IBAIZABAL       ,IBAIZABAL-102
Junc L&A=71.69,0
Junc L&A=79.113,0

Junct Name=COR
Junct Desc=, 0 , 0 ,-1 ,0
Up River,Reach=IBAIZABAL       ,IBAIZABAL-101
Up River,Reach=CORTA           ,MANA
Dn River,Reach=IBAIZABAL       ,IBAIZABAL-100
Junc L&A=75.552,
Junc L&A=50,

River Reach=MAÑARIA         ,MAÑARIA-100
Reach XY= 30
527814.7754939654776301.97524814528130.816625826 4776279.6084832
528296.2685341164776378.55020767528607.0240734264776442.98052542
528817.3298927214776712.13732028528818.8756903974776916.96788163
528919.4654462674776998.68523006529034.6572041664777219.45510134
  528972.18736844777428.55474898528984.2938279844777492.59893462
529074.3957541034777583.01255481529228.756575301 4777659.2206499
529303.9175540954777760.63787842529370.2826154014777994.90522989
529425.4181297274778023.22566557529524.9677479274777998.29136894
 529659.311547324778242.49692797529864.6051187664778416.31685036
529922.2162508114778693.47030766530031.7884510354778831.45729369
530023.1369595834778918.39558892529939.7031714884778947.49114601
529901.716307949 4779274.4221739529848.8065081394779338.70588934
529961.3573970054779776.83330172529932.0188729914779943.70162179
529850.8409679054779984.82863604529827.7257091784780071.04174308
529960.0900950624780166.83039556529922.4819193484780224.27112185

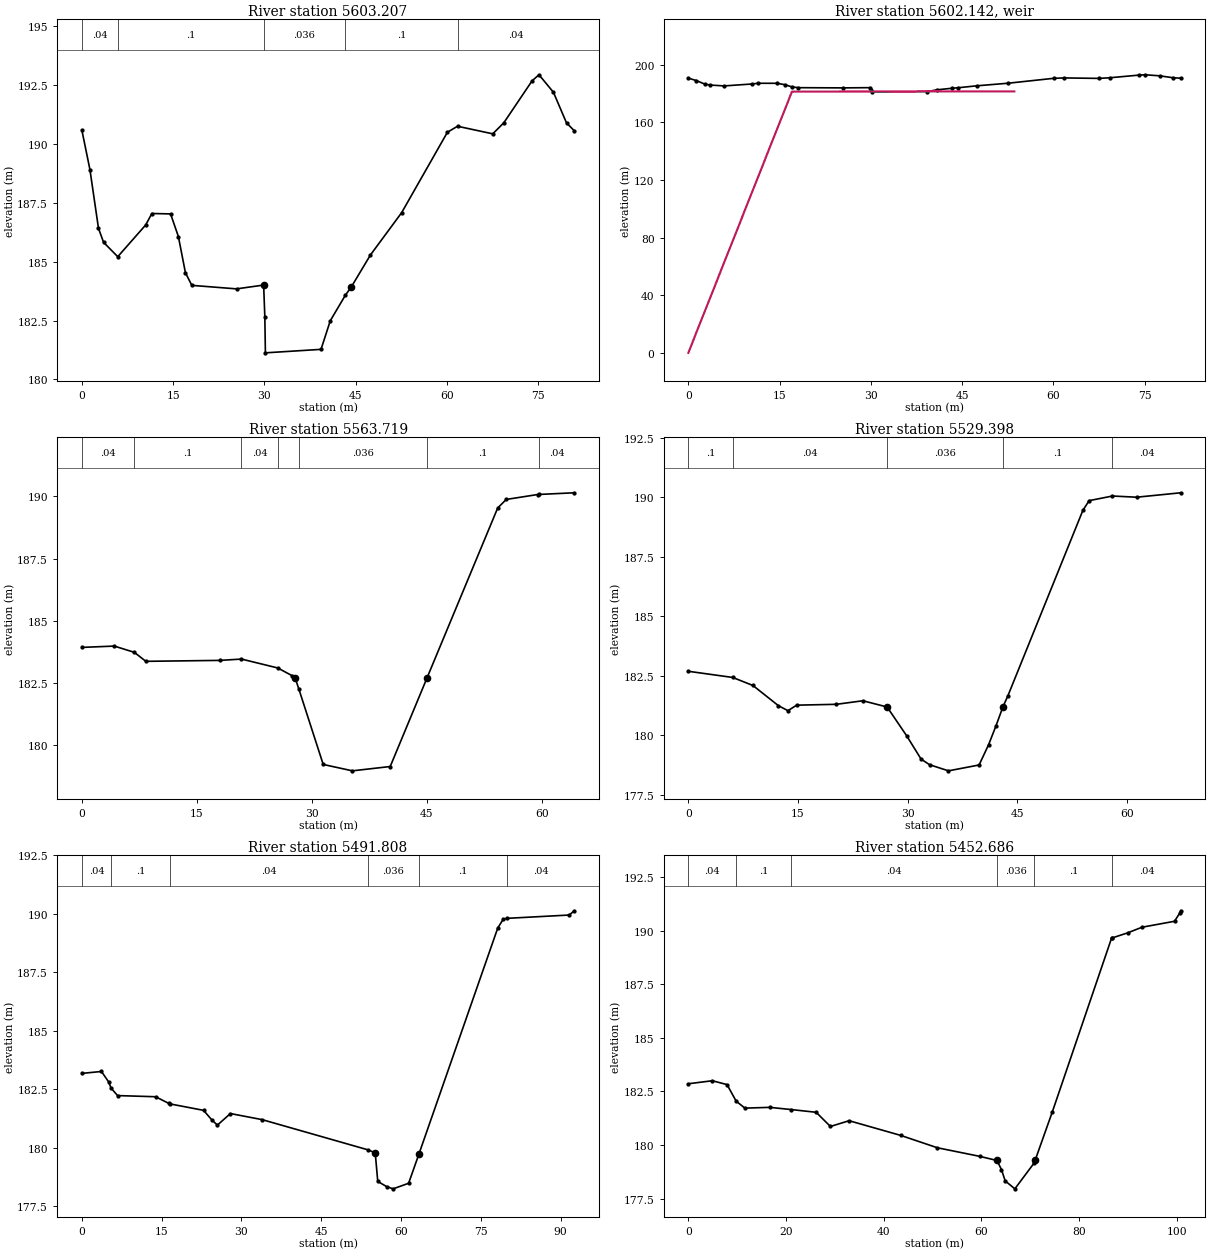
Type RM Length L Ch R = 1 ,5603.207,38.447,39.487,40.528
XS GIS Cut Line= 4
527838.6566630234776337.31765074527835.2796795194776320.62039409
 527814.429287154776278.19451119527822.1803457434776263.50571136
#Sta/Elev= 30
       0 190.595   1.326 188.921   2.731 186.425    3.57 185.826   5.899 185.217
  10.481 186.563  11.509 187.052  14.581 187.035  15.863  186.07  17.015 184.539
  18.067 183.999  25.423  183.85  29.869 184.012  30.066 182.658  30.158 181.132
  39.298  181.28  40.819 182.495  43.289 183.578  44.287 183.937   47.42 185.292
  52.543 187.087  60.064 190.504  61.723 190.759  67.514 190.437  69.326 190.904
   73.98  192.69  75.111 192.946  77.482 192.204  79.633 190.901  80.917 190.567
#Mann= 5 ,-1 , 0
       0     .04       0   5.899      .1       0  29.869    .036       0
  43.289      .1       0  61.723     .04       0
Bank Sta=29.869,44.287
XS Rating Curve= 0 ,0
Exp/Cntr=0.3,0.1

Type RM Length L Ch R = 5 ,5602.142,,,
BEGIN DESCRIPTION:
E126
END DESCRIPTION:
IW Pilot Flow=0
#Inline Weir SE= 6
       0       0   17.02  181.21   26.38  181.34   35.94  181.37   39.38  181.43
   53.56  181.43
IW Dist,WD,Coef,Skew,MaxSub,Min_El,Is_Ogee,SpillHt,DesHd
1,1.3,1.7,0,0.98,, 0 ,,,0,0,

Type RM Length L Ch R = 1 ,5563.719,34.324,34.321,34.319
XS GIS Cut Line= 2
527874.0140118174776332.58080992527859.9162835764776269.88301853
#Sta/Elev= 19
       0 183.923   4.231 183.976    6.85 183.724   8.349 183.362   18.04   183.4
  20.828 183.453  25.563 183.095  27.463 182.779   27.83 182.695  28.304 182.258
  31.495  179.21  35.301 178.953  40.238 179.127  45.013 182.674  54.262 189.535
  55.383  189.88  59.486 190.078  59.592  190.08  64.263 190.148
#Mann= 7 ,-1 , 0
       0     .04       0    6.85      .1       0  20.828     .04       0
  25.563      .1       0  28.304    .036       0  45.013      .1       0
  59.592     .04       0
Bank Sta=27.83,45.013
XS Rating Curve= 0 ,0
Exp/Cntr=0.3,0.1

Type RM Length L Ch R = 1 ,5529.398,37.69,37.59,37.489
XS GIS Cut Line= 2
527907.0323944674776322.93499951 527892.208860954776257.21677324
#Sta/Elev= 23
       0 182.687    6.07 182.428   8.837 182.091  12.321 181.243  13.628 181.032
  14.822 181.264  20.253   181.3  23.879 181.449  27.196 181.187  29.853 179.984
  31.839     179  33.001 178.762  35.589 178.505  39.778 178.751  41.078 179.604
  42.091 180.397   43.02  181.18  43.726 181.664  53.977 189.449  54.834 189.856
  58.025  190.05   61.33     190  67.369 190.186
#Mann= 5 ,-1 , 0
       0      .1       0    6.07     .04       0  27.196    .036       0
   43.02      .1       0  58.025     .04       0
Bank Sta=27.196,43.02
XS Rating Curve= 0 ,0
Exp/Cntr=0.3,0.1

Type RM Length L Ch R = 1 ,5491.808,37.341,39.122,40.903
XS GIS Cut Line= 3
527933.7438944674776336.29069951527939.6797944674776294.73949951
527927.1987866994776245.70545989
#Sta/Elev= 25
       0 183.172   3.687 183.254   5.018 182.813   5.508 182.539   6.718 182.223
  13.857 182.174  16.372 181.886  16.607 181.866   22.88 181.592  24.463 181.175
  25.483 180.962  27.931 181.455  33.876 181.196  53.769 179.905  55.146 179.776
  55.622 178.554  57.296 178.333  58.505 178.237  61.423 178.475   63.37  179.73
   78.18 189.387  79.223 189.767  79.935   189.8  91.606 189.941  92.571 190.123
#Mann= 6 ,-1 , 0
       0     .04       0   5.508      .1       0  16.607     .04       0
  53.769    .036       0   63.37      .1       0  79.935     .04       0
Bank Sta=55.146,63.37
XS Rating Curve= 0 ,0
Exp/Cntr=0.3,0.1

Type RM Length L Ch R = 1 ,5452.686,47.605,48.192,48.78
XS GIS Cut Line= 3
527965.2782944674776343.71059951 527966.835787854776307.97915107
527982.0014772914776244.68228497
#Sta/Elev= 27
       0  182.86   4.927 183.001   7.931  182.82   9.793 182.049  11.587 181.722
  16.703 181.758  21.079 181.655  26.183 181.528  29.098 180.865  32.925 181.134
  43.459 180.451  51.004 179.871  59.709 179.469  63.205 179.277  64.133  178.85
   64.89 178.325  66.873 177.953  70.833 179.164  71.076 179.319  74.553 181.551
  86.678 189.661  86.856 189.674  89.961 189.906  92.916  190.17  99.572 190.448
 100.697 190.851 100.854 190.938
#Mann= 6 ,-1 , 0
       0     .04       0   9.793      .1       0  21.079     .04       0
  63.205    .036       0  70.833      .1       0  86.856     .04       0
Bank Sta=63.205,71.076
XS Rating Curve= 0 ,0
Exp/Cntr=0.3,0.1

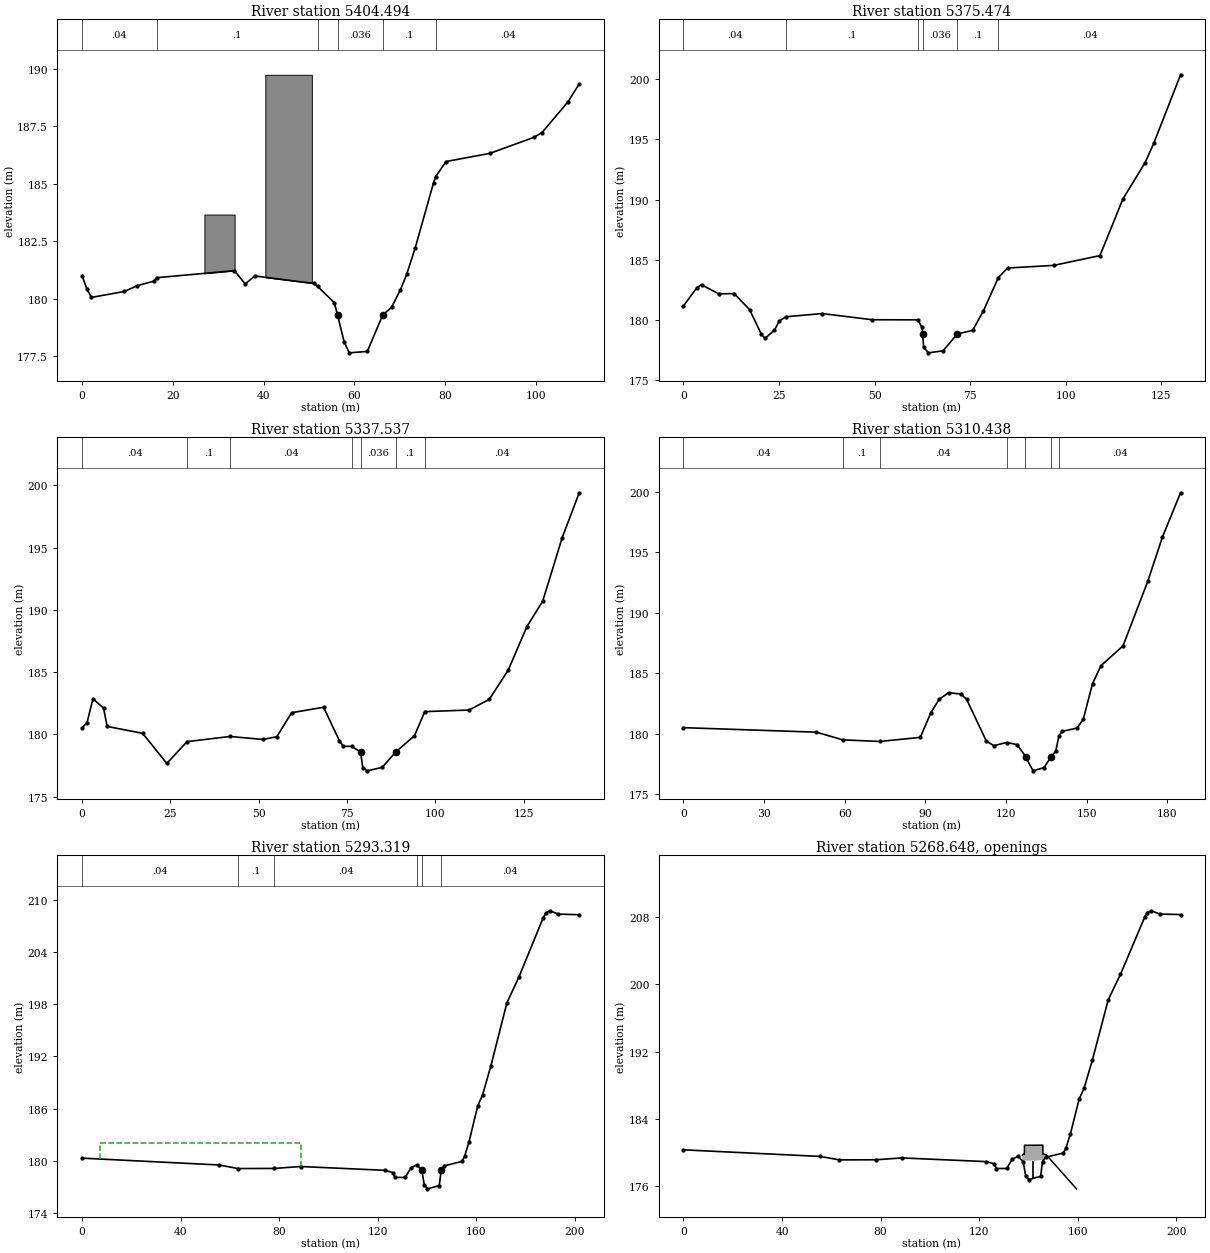
Type RM Length L Ch R = 1 ,5404.494,30.033,29.019,28.006
XS GIS Cut Line= 4
528000.1375047764776353.62756011528010.4249919284776315.49362488
528022.7435972834776285.91979466528025.8562226564776248.00943775
#Sta/Elev= 30
       0 181.007   1.022 180.439   2.058 180.056   9.308 180.314  12.176 180.568
  15.792  180.76  16.425 180.913  33.589  181.22  35.961 180.638  38.028 180.989
  51.121 180.664  51.905 180.534  55.587 179.831    56.3  179.29  57.754 178.127
  58.892 177.645  62.864 177.707   66.26 179.289   68.21 179.623  70.144 180.381
  71.534 181.053  73.403 182.195  77.468 185.045  77.939 185.306  80.207 185.966
  89.875 186.322  99.636 187.021 101.385 187.228 107.053 188.554 109.573 189.337
#Mann= 6 ,-1 , 0
       0     .04       0  16.425      .1       0  51.905      .1       0
    56.3    .036       0   66.26      .1       0  77.939     .04       0
#XS Ineff= 1 ,-1
     .11   17.23  180.85
Permanent Ineff=
       T
#Block Obstruct= 2 ,-1
   26.96   33.62  183.66   40.39   50.64  189.74
Bank Sta=56.3,66.26
XS Rating Curve= 0 ,0
Exp/Cntr=0.3,0.1

Type RM Length L Ch R = 1 ,5375.474,39.248,37.937,36.627
XS GIS Cut Line= 2
528038.7172791684776368.83698391528054.1386331184776239.70372096
#Sta/Elev= 30
       0 181.163   3.538 182.685   4.737 182.923   9.221  182.17   13.29 182.189
  17.318 180.852   20.34 178.843  21.347 178.466  23.822 179.152  25.067 179.914
  26.803 180.263  36.286  180.53  49.416 180.016  61.293 180.008  62.409 179.388
   62.58  178.85  62.838 177.748  64.075 177.267  67.918 177.433  71.638 178.835
  75.646 179.133  78.496 180.763  82.374 183.511  84.785 184.312  96.851 184.531
 108.965 185.345 114.955 190.036  120.78 193.071 123.064 194.692 130.051 200.365
#Mann= 6 ,-1 , 0
       0     .04       0  26.803      .1       0  61.293      .1       0
   62.58    .036       0  71.638      .1       0  82.374     .04       0
#XS Ineff= 1 ,-1
   13.94   29.11  180.28
Permanent Ineff=
       T
Bank Sta=62.58,71.638
XS Rating Curve= 0 ,0
Exp/Cntr=0.3,0.1

Type RM Length L Ch R = 1 ,5337.537,28.07,27.099,26.127
XS GIS Cut Line= 3
528080.2859944674776379.69689951528086.8819520084776311.39165048
528069.8981944674776241.31659951
#Sta/Elev= 30
       0 180.515   1.412 180.953    3.07 182.859   6.084 182.114   7.089 180.641
  17.135 180.087  23.988 177.669  29.707  179.42   41.88 179.834  51.215 179.594
  55.125 179.815  59.331 181.744  68.373 182.179  72.864 179.475  73.952 179.045
  76.302 179.037   78.83  178.59  79.461 177.322  80.714 177.074  84.965 177.352
  88.814 178.595   94.09  179.89  97.003 181.829 109.525 181.957  115.27 182.812
 120.629 185.166 125.907 188.653 130.393 190.701 135.899 195.794 140.727 199.404
#Mann= 7 ,-1 , 0
       0     .04       0  29.707      .1       0   41.88     .04       0
  76.302      .1       0   78.83    .036       0  88.814      .1       0
  97.003     .04       0
#XS Ineff= 1 ,-1
    6.06   59.35180.9033
Permanent Ineff=
       T
Bank Sta=78.83,88.814
XS Rating Curve= 0 ,0
Exp/Cntr=0.3,0.1

Type RM Length L Ch R = 1 ,5310.438,15.461,17.12,18.778
XS GIS Cut Line= 3
528097.3744944674776413.17339951528114.2873869074776297.64576098
528081.5330080844776237.93716959
#Sta/Elev= 30
       0  180.49  49.398 180.115  59.304  179.48  73.057 179.347  88.096 179.687
   92.02 181.728  95.123 182.841  98.572 183.374 103.168 183.273 105.283 182.842
  112.64  179.38 115.426 178.998 120.178 179.261  124.07 179.085 127.029 178.176
 127.233 178.072 130.011 176.917 134.083 177.182 136.749 178.082 138.435 178.539
 139.607 179.776 140.712 180.177 146.419 180.459   148.7 181.195 152.122 184.127
 155.258 185.614 163.471 187.258 172.653 192.584 178.129  196.26 184.861 199.918
#Mann= 7 ,-1 , 0
       0     .04       0  59.304      .1       0  73.057     .04       0
 120.178      .1       0 127.029    .036       0 136.749      .1       0
 139.607     .04       0
#XS Ineff= 1 ,-1
    6.17   94.98   180.4
Permanent Ineff=
       T
Bank Sta=127.233,136.749
XS Rating Curve= 0 ,0
Exp/Cntr=0.5,0.3

Type RM Length L Ch R = 1 ,5293.319,41.592,47.368,53.144
XS GIS Cut Line= 4
 528117.12109619 4776420.4013088528123.5910029534776293.53918098
528122.2558374954776268.67605913528140.2917221894776222.28996323
#Sta/Elev= 30
       0 180.327  55.559 179.543  63.272 179.131  78.056 179.147  88.675 179.366
 122.953 178.928 126.149 178.658 126.925 178.108 131.131 178.115 133.412 179.209
 135.801179.5529  137.85  178.92 138.855 177.235 140.126 176.803 144.918 177.173
 145.682 178.938 146.954 179.443 154.109 179.949 155.182 180.523 156.986 182.203
 160.547 186.351 162.519 187.613 165.881 190.944 172.349 198.147 177.315 201.172
 187.094 207.928 188.179  208.49 189.852  208.72 193.193 208.337 201.695 208.266
#Mann= 6 ,-1 , 0
       0     .04       0  63.272      .1       0  78.056     .04       0
 135.801      .1       0  137.85    .036       0 145.682     .04       0
#XS Ineff= 1 ,-1
    7.27   88.99  182.09
Permanent Ineff=
       T
Bank Sta=137.85,145.682
XS Rating Curve= 0 ,0
Exp/Cntr=0.5,0.3

Type RM Length L Ch R = 4 ,5268.648,,,
BEGIN DESCRIPTION:
E127
END DESCRIPTION:
Bridge Culvert--1,0,-1,-1, 0
Deck Dist Width WeirC Skew NumUp NumDn MinLoCord MaxHiCord MaxSubmerge Is_Ogee
0.01,47.17,1.44,0, 16, 14, , , 0.95, 0, ,,,
   137.5 137.777 138.079 138.163 138.338 138.361 142.078 142.586 145.658 145.838
 145.844 145.855 146.037 147.083 159.308 159.437
  179.71  179.81 179.785 179.785 179.786  180.87 180.875 180.875  180.88  180.88
 179.814 179.814 179.815 179.774 175.748 175.695
  118.94 118.899 165.963 179.048 179.048 179.047 179.037  179.03 179.116 123.701
 121.816 118.577 118.576 118.566 118.454 175.695
 115.218 115.297 126.609 130.283 130.285 131.765 131.939 139.615 139.647 141.491
 141.492   144.1 155.768 155.836
 176.288 176.314 180.018  180.34 181.524 181.608 181.617 182.053 182.055  182.16
 181.905  182.04 179.516 179.497
 176.288 134.704 134.625   134.6   134.6  134.59 178.829 178.829 134.886 134.893
 134.893 134.893 134.943 179.497
Pier Skew, UpSta & Num, DnSta & Num=  ,141.76, 2 ,, 0 , 0 , 0 , 0 ,,
      .5      .5
   176.8   180.7
BR Coef=-1 , 0 , 0 ,, 0 ,,,0.8,-1,,0,
WSPro=,,,, 1 ,,,, 0 ,,,, 0 ,,,,-1 ,-1 ,-1 , 0 , 0 , 0 , 0 , 0
BC Mult= 1 ,0,137.5,0,128
BC Mult= 3 ,137.5,147,128,144
BC Mult= 1 ,147,300,144,250
BC Design=,, 0 ,, 0 ,,,,,,
BC Use User HTab Curves=0
BC User HTab FreeFlow(D)= 0

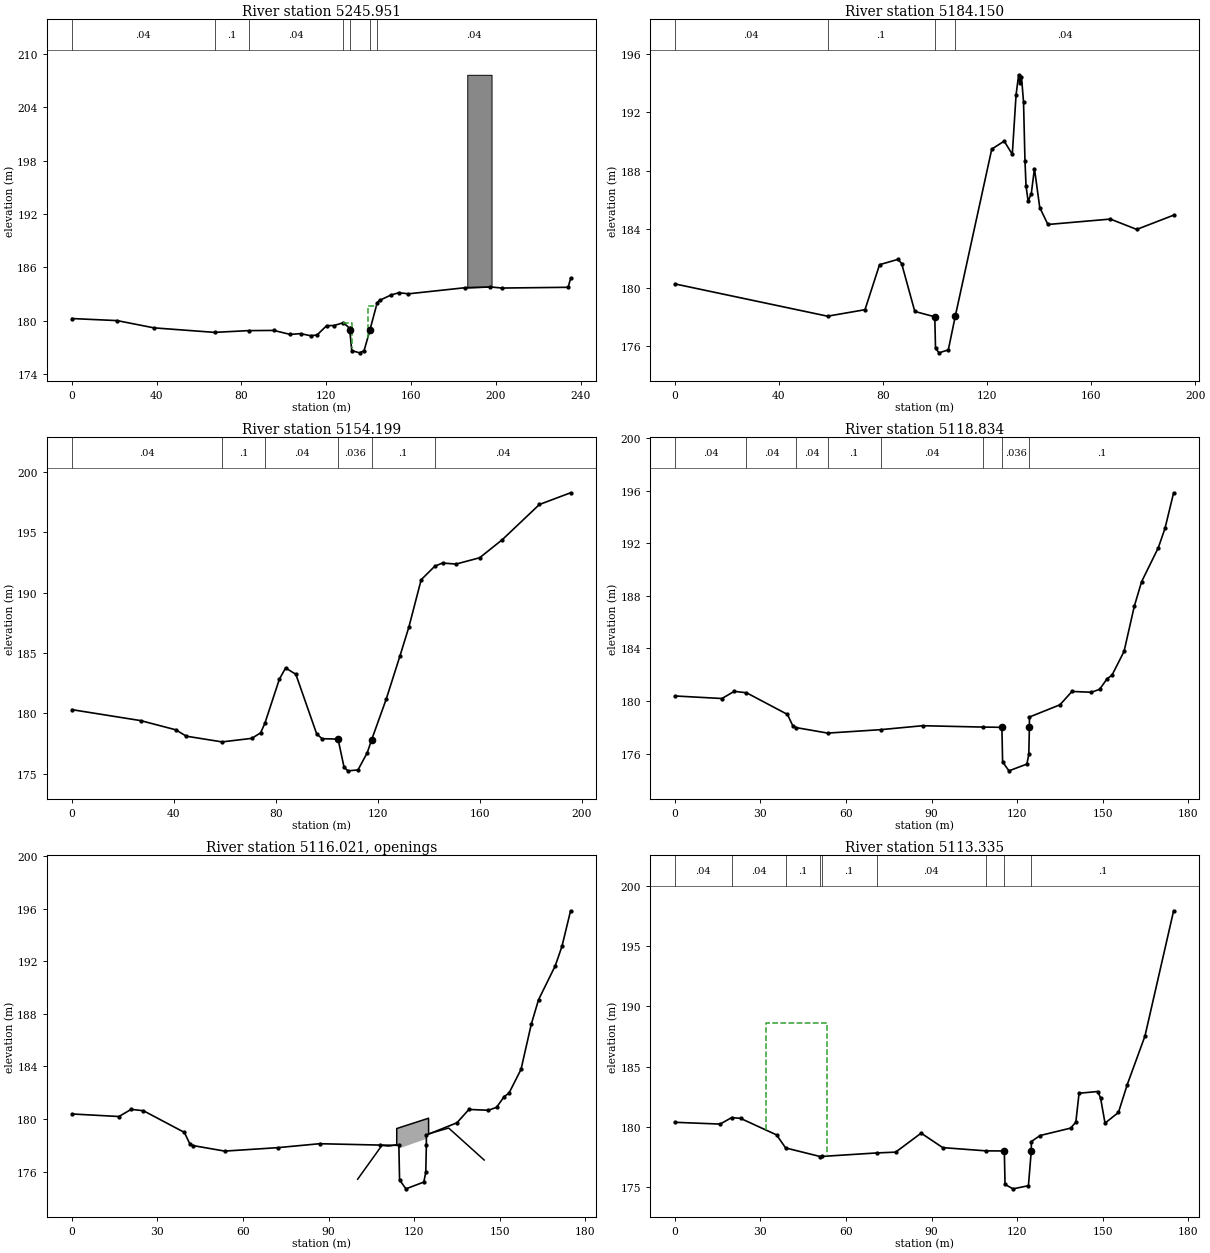
Type RM Length L Ch R = 1 ,5245.951,65.147,61.8,58.454
XS GIS Cut Line= 5
528131.2859586854776427.61294675528137.3514121024776372.63301907
528148.6719999254776304.85782121528178.9150536654776302.85269949
528243.6967917634776254.26653832
#Sta/Elev= 30
       0 180.268  21.363 180.035   38.72 179.221  67.323 178.715  83.348 178.912
   95.27 178.934 102.957 178.487 107.887 178.573 112.597 178.342 115.636 178.414
 120.192 179.467 123.672 179.484 128.101   179.8 131.035 179.176   131.1  179.01
 132.053 176.673 135.708 176.419 137.855 176.651 140.654 178.984 140.671 179.028
 144.062 182.041 145.173 182.304  150.45 182.897 154.337 183.169 158.732  183.04
 185.597 183.728 197.243 183.818 202.977  183.69 234.157 183.774 235.314 184.768
#Mann= 7 ,-1 , 0
       0     .04       0  67.323      .1       0  83.348     .04       0
 128.101      .1       0   131.1    .036       0 140.654      .1       0
 144.062     .04       0
#XS Ineff= 2 ,-1
   128.1  131.94   179.8  139.62  144.06  181.65
Permanent Ineff=
       T       T
#Block Obstruct= 1 ,-1
  186.56  198.02  207.62
Bank Sta=131.1,140.671
XS Rating Curve= 0 ,0
Exp/Cntr=0.5,0.3

Type RM Length L Ch R = 1 ,5184.150,30.3,29.952,29.603
XS GIS Cut Line= 2
528147.9805944674776428.30859951528257.0524944674776270.63659951
#Sta/Elev= 30
       0 180.251  58.667 178.043  73.062 178.487  78.658 181.567  85.762 181.933
  87.145 181.648   92.21 178.368  99.898     178 100.173 175.856 101.523 175.535
 105.097 175.738 107.816 178.079 121.797 189.477 126.586 190.024 129.697 189.119
 131.141 193.175 132.135 194.564 132.579 193.986 133.221 194.445 134.017 192.697
 134.567 188.693 134.979 186.961 135.782 185.905 136.999 186.433 138.215 188.142
 140.252 185.475 143.398 184.319 167.397 184.689 177.547 183.981 191.721 184.956
#Mann= 4 ,-1 , 0
       0     .04       0  58.667      .1       0  99.898    .036       0
 107.816     .04       0
Bank Sta=99.898,107.816
XS Rating Curve= 0 ,0
Exp/Cntr=0.3,0.1

Type RM Length L Ch R = 1 ,5154.199,35.06,35.365,35.669
XS GIS Cut Line= 2
528179.5546779114776453.45008407528274.5926348924776282.39126577
#Sta/Elev= 30
       0 180.293  26.931 179.387  40.771 178.622  44.878 178.095  58.921  177.62
  70.592 177.915  74.041 178.371  75.711 179.157  81.411 182.819  83.854 183.749
  87.867 183.228  96.041 178.289  98.163 177.886 104.438 177.853 106.797 175.518
 108.298 175.222  112.25 175.295 115.894 176.721  117.62   177.8 123.331  181.16
 128.692 184.719 132.224 187.134 137.058 191.062 142.402 192.183 145.433 192.447
 150.708 192.358 159.995 192.881 168.844 194.373 183.457 197.298 195.687 198.268
#Mann= 6 ,-1 , 0
       0     .04       0  58.921      .1       0  75.711     .04       0
 104.438    .036       0  117.62      .1       0 142.402     .04       0
Bank Sta=104.438,117.62
XS Rating Curve= 0 ,0
Exp/Cntr=0.5,0.3

Type RM Length L Ch R = 1 ,5118.834,5.499,5.499,5.499
XS GIS Cut Line= 3
 528191.465498474776461.11776726528256.3733235374776383.52219455
528297.4611821944776322.31754375
#Sta/Elev= 30
       0 180.381  16.492 180.187  20.779 180.732  25.078 180.626  39.441 178.978
  41.382 178.091  42.584 177.971  53.584 177.555  72.121 177.816  86.862 178.117
 108.111 178.013 114.661 177.995 114.906 175.361 117.134 174.683 123.407 175.197
 124.096 175.936   124.3  177.99 124.316 178.778 135.035 179.711 139.233 180.725
 146.046 180.663 148.928 180.888 151.608 181.709 153.252 181.955 157.496 183.771
 161.084 187.203 163.652 189.079 169.482 191.648 171.849  193.13 174.881 195.844
#Mann= 8 ,-1 , 0
       0     .04       0  25.078     .04       0  42.584     .04       0
  53.584      .1       0  72.121     .04       0 108.111      .1       0
 114.661    .036       0   124.3      .1       0
Bank Sta=114.661,124.3
XS Rating Curve= 0 ,0
Exp/Cntr=0.5,0.3

Type RM Length L Ch R = 4 ,5116.021,,,
BEGIN DESCRIPTION:
E129
END DESCRIPTION:
Bridge Culvert--1,0,-1,-1, 0
Deck Dist Width WeirC Skew NumUp NumDn MinLoCord MaxHiCord MaxSubmerge Is_Ogee
0.01,5.3,1.44,0, 19, 19, , , 0.95, 0, ,,,
 100.203 100.499 108.705 110.948 111.898 113.079 113.908 113.916 114.525 114.747
 124.212 124.424 125.078 125.092 125.097 126.311 132.123   144.4 144.578
 175.414 175.504 177.987 177.938  177.96  178.01 178.045 179.273 179.316 179.332
 179.996 180.011 180.057 179.127 178.858 178.949 179.309 176.911 176.876
 175.414 119.189 119.277 119.301 119.311 119.324 119.333 119.333 119.339 177.756
  178.48 119.768 119.767 119.767 119.767 119.765 119.755 119.733 176.876
 101.068 101.364  109.57 111.813 112.763 113.944 114.773 114.781  115.39 115.612
 125.077 125.289 125.943 125.957 125.962 127.176 132.988 145.265 145.443
 175.414 175.504 177.987 177.938  177.96  178.01 178.045 179.273 179.316 179.332
 179.996 180.011 180.057 179.127 178.858 178.949 179.309 176.911 176.876
 175.414 119.189 119.277 119.301 119.311 119.324 119.333 119.333 119.339 177.756
  178.48 119.768 119.767 119.767 119.767 119.765 119.755 119.733 176.876
BR Coef=-1 , 0 , 0 ,, 0 ,,,0.8,-1,,0,
WSPro=,,,, 1 ,,,, 0 ,,,, 0 ,,,,-1 ,-1 ,-1 , 0 , 0 , 0 , 0 , 0
BC Mult= 1 ,0,113.9,0,115
BC Mult= 3 ,113.9,126.5,115,126
BC Mult= 1 ,126.5,180,126,180
BC Design=,, 0 ,, 0 ,,,,,,
BC Use User HTab Curves=0
BC User HTab FreeFlow(D)= 0

Type RM Length L Ch R = 1 ,5113.335,37.44,36.63,35.82
XS GIS Cut Line= 3
528196.3797612864776463.46770588528261.2875863534776385.87213317
 528302.375445014776324.66748238
#Sta/Elev= 30
       0 180.372  15.847 180.223  19.901 180.766  22.995 180.699  35.638 179.324
  38.824  178.24  50.943 177.526   51.59 177.535  70.687 177.824  77.404 177.892
  86.331 179.469  93.927 178.266 109.126 177.997 115.511  177.99 115.759 175.208
 118.562 174.841 123.958 175.101  124.95  177.97 125.001 178.774 128.048 179.273
  138.78 179.888 140.594 180.392 141.718 182.786 148.283 182.931 149.242 182.411
 150.824 180.301 155.535 181.192  158.61   183.5 164.826 187.537 174.881 197.952
#Mann= 9 ,-1 , 0
       0     .04       0  19.901     .04       0  38.824      .1       0
  50.943     .04       0   51.59      .1       0  70.687     .04       0
 109.126      .1       0 115.511    .036       0  124.95      .1       0
#XS Ineff= 1 ,-1
   31.88   53.29   188.6
Permanent Ineff=
       T
Bank Sta=115.511,124.95
XS Rating Curve= 0 ,0
Exp/Cntr=0.5,0.3

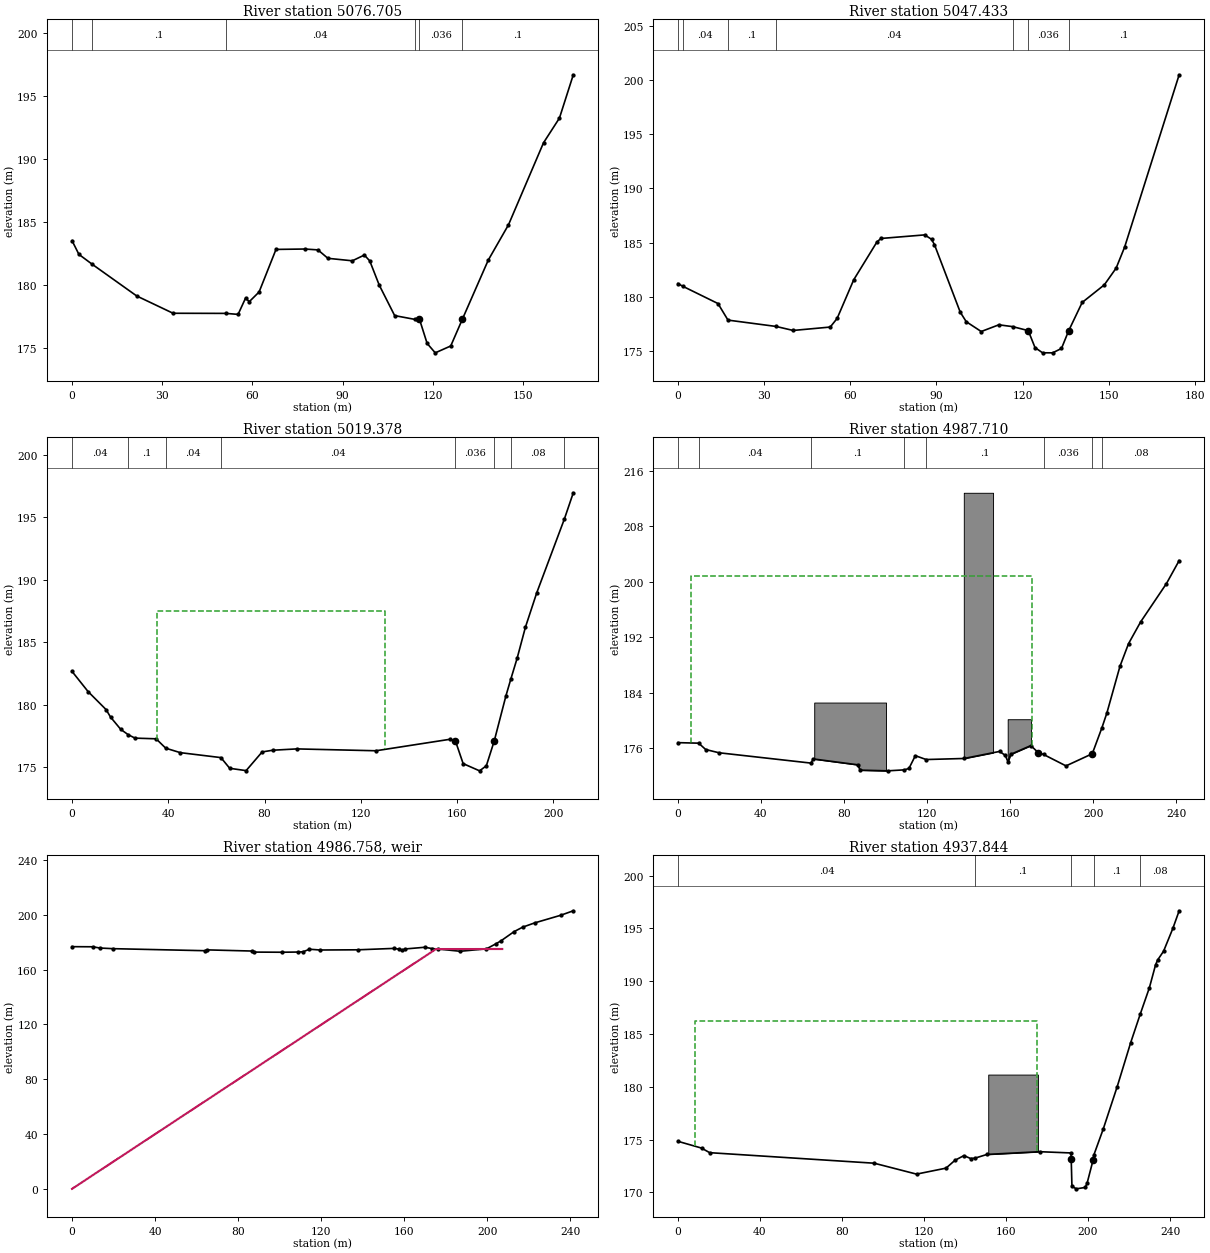
Type RM Length L Ch R = 1 ,5076.705,30.191,29.273,28.355
XS GIS Cut Line= 3
528242.2127944674776485.07049951528293.4097944674776415.69479951
528322.7182944674776340.75419951
#Sta/Elev= 30
       0 183.529   2.282 182.442   6.668 181.663  21.523 179.139    33.6 177.769
   51.19 177.759  55.217 177.679  57.703 178.971  58.946  178.69  62.204 179.457
  67.823 182.835  77.393 182.866  81.776 182.797  85.087 182.129  93.206 181.932
  97.209 182.388  99.005 181.923 102.149 180.007 107.285 177.584 113.965 177.285
 115.544  177.29 118.086 175.375 120.785 174.629 125.933 175.174 129.767 177.277
 138.419 181.989 145.139 184.787 156.783 191.293 162.082 193.254 166.689 196.691
#Mann= 6 ,-1 , 0
       0     .04       0   6.668      .1       0   51.19     .04       0
 113.965      .1       0 115.544    .036       0 129.767      .1       0
Bank Sta=115.544,129.767
XS Rating Curve= 0 ,0
Exp/Cntr=0.3,0.1

Type RM Length L Ch R = 1 ,5047.433,28.853,28.054,27.255
XS GIS Cut Line= 3
528279.6830944674776501.76509951528331.6220944674776417.54979951
528340.8968944674776342.60919951
#Sta/Elev= 30
       0 181.217   1.675 180.968  13.944  179.37  17.428  177.84  34.159 177.255
  40.099 176.884  53.016 177.198  55.413 177.994  61.197 181.568  69.248 185.049
  70.639 185.381  85.905 185.712  88.263 185.306  89.287 184.814  98.259 178.575
 100.351 177.693 105.568 176.786 111.697 177.405 116.488 177.238 121.931 176.869
  124.29   175.3 126.922  174.82 130.403 174.816 133.501  175.22  135.99  176.85
 140.699  179.47  148.41 181.097 152.528 182.645 155.485  184.59 174.456 200.503
#Mann= 7 ,-1 , 0
       0    .045       0   1.675     .04       0  17.428      .1       0
  34.159     .04       0 116.488      .1       0 121.931    .036       0
  135.99      .1       0
Bank Sta=121.931,135.99
XS Rating Curve= 0 ,0
Exp/Cntr=0.3,0.1

Type RM Length L Ch R = 1 ,5019.378,31.78,31.668,31.555
XS GIS Cut Line= 3
528305.7900022114776537.16747841528366.5772786094776421.05514593
528359.311828258 4776344.1345818
#Sta/Elev= 30
       0 182.666   6.654 181.056  14.139 179.613  16.013  179.01  20.243  178.03
  23.374 177.599  26.185 177.329  34.934 177.275  38.936 176.524  44.994 176.167
  61.872 175.771   65.53 174.914  72.347 174.729  79.006 176.224  83.424 176.361
  93.435 176.467 126.325 176.318 157.081 177.237 159.353 177.097 162.545  175.29
 169.373 174.712 172.189 175.116  175.48  177.11 180.351 180.728 182.367 182.055
 184.978 183.714 188.436 186.207 193.138 188.957 204.595 194.845 208.324 196.957
#Mann= 8 ,-1 , 0
       0     .04       0  23.374      .1       0  38.936     .04       0
  61.872     .04       0 159.353    .036       0  175.48      .1       0
 182.367     .08       0 204.595      .1       0
#XS Ineff= 1 ,-1
   35.24  130.18  187.52
Permanent Ineff=
       T
Bank Sta=159.353,175.48
XS Rating Curve= 0 ,0
Exp/Cntr=0.3,0.1

Type RM Length L Ch R = 1 ,4987.710,48.885,49.866,50.848
XS GIS Cut Line= 3
528372.3791727224776570.24250008528401.0884892844776441.24758054
528388.1717730144776332.79110306
#Sta/Elev= 30
       0 176.828   9.993 176.753  13.378 175.838  19.803  175.37  64.085 173.883
  65.158 174.482  86.672 173.636  87.697 172.868 101.015 172.769 109.029  172.91
 111.259 173.117 114.333 174.952 119.553 174.396 137.798 174.548 154.918 175.563
 157.633 174.995 158.946 174.067 160.204 175.135 169.942 176.403  173.49   175.4
 176.066 175.128 186.886 173.481 199.533 175.229 204.179 178.967  206.54 181.067
 212.882 187.832 216.996 191.079 222.796 194.197 235.263 199.734 241.375 203.038
#Mann= 8 ,-1 , 0
       0      .1       0   9.993     .04       0  64.085      .1       0
 109.029     .04       0 119.553      .1       0 176.066    .036       0
 199.533      .1       0 204.179     .08       0
#XS Ineff= 1 ,-1
    6.17  170.48   200.8
Permanent Ineff=
       T
#Block Obstruct= 3 ,-1
   65.64  100.22   182.6  137.67  151.76   212.8  158.81  170.04   180.2
Bank Sta=173.49,199.533
XS Rating Curve= 0 ,0
Exp/Cntr=0.3,0.1

Type RM Length L Ch R = 5 ,4986.758,,,
BEGIN DESCRIPTION:
E310
END DESCRIPTION:
IW Pilot Flow=0
#Inline Weir SE= 6
       0       0  175.26  175.09  183.33  175.09  192.98  175.09  200.66  175.12
  207.12  175.12
IW Dist,WD,Coef,Skew,MaxSub,Min_El,Is_Ogee,SpillHt,DesHd
0.1,2.2,1.7,0,0.98,, 0 ,,,0,0,

Type RM Length L Ch R = 1 ,4937.844,42.327,42.611,42.895
XS GIS Cut Line= 3
528422.7488944674776589.05149951528439.4573944674776423.72609951
528450.5329250324776346.25887753
#Sta/Elev= 30
       0  174.84  11.521 174.198  15.488 173.763  95.696 172.766  116.36 171.732
 130.742 172.299 135.095  173.04 139.451 173.485 142.803 173.206 144.796 173.242
 150.747 173.598 176.355 173.856 191.683 173.737  191.79  173.13 192.141 170.579
 194.242 170.338 198.653 170.471 199.573 170.903 202.504 173.103 202.756 173.508
 207.406 176.006 214.224 180.024 220.802 184.196  225.43 186.878 229.894 189.376
 232.924 191.556 233.935 192.017 236.805 192.838 241.346 195.002 244.422 196.674
#Mann= 5 ,-1 , 0
       0     .04       0 144.796      .1       0 191.683    .036       0
 202.756      .1       0  225.43     .08       0
#XS Ineff= 1 ,-1
    8.15  175.33  186.28
Permanent Ineff=
       T
#Block Obstruct= 1 ,-1
  151.32  175.55  181.16
Bank Sta=191.79,202.504
XS Rating Curve= 0 ,0
Exp/Cntr=0.3,0.1

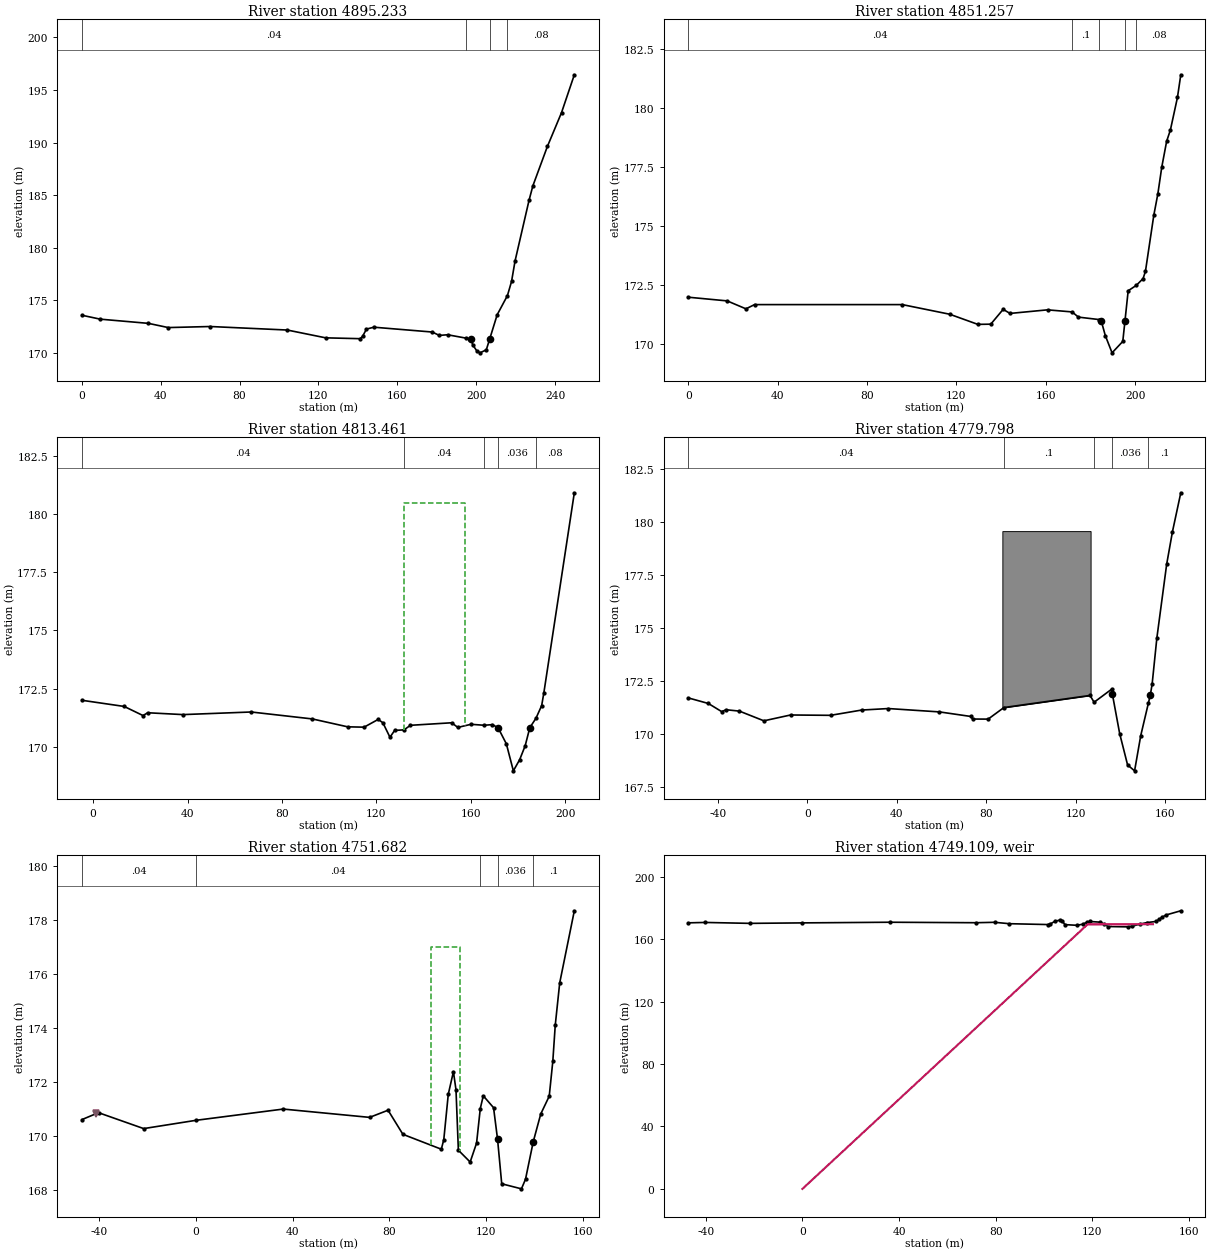
Type RM Length L Ch R = 1 ,4895.233,43.596,43.976,44.357
XS GIS Cut Line= 3
528462.3215033034776601.36298167528478.1505315034776435.15818557
528496.1745441154776354.29991495
#Sta/Elev= 30
       0 173.566   9.313 173.192  33.749 172.792  43.821 172.392  65.151 172.492
 104.191 172.157 123.683 171.414 141.159 171.334 142.363 171.547 144.372 172.245
 148.078 172.427 177.732 171.967 181.323 171.645 185.503 171.708 194.769  171.39
 197.414 171.275 198.256 170.749 200.272  170.19 201.966 169.987 205.151 170.277
   206.8  171.26 210.665 173.609 215.877 175.439 217.958 176.783 219.738 178.731
 226.849 184.518 228.787 185.886 236.131 189.623 243.303 192.843   249.8 196.447
#Mann= 4 ,-1 , 0
       0     .04       0 194.769    .036       0   206.8      .1       0
 215.877     .08       0
#XS Ineff= 1 ,-1
   70.04  146.04  172.28
Permanent Ineff=
       T
Bank Sta=197.414,206.8
XS Rating Curve= 0 ,0
Exp/Cntr=0.3,0.1

Type RM Length L Ch R = 1 ,4851.257,37.94,37.796,37.652
XS GIS Cut Line= 3
528504.5322944674776602.24239951528516.8436944674776446.59029951
528537.2476240494776385.64131545
#Sta/Elev= 30
       0 171.992  17.397 171.836  25.784   171.5  29.644 171.679  95.774 171.679
 116.993 171.271 129.566 170.842 135.362  170.85 140.912 171.478 143.973 171.305
  160.77 171.457  171.78 171.369 174.578 171.149 183.993 171.044 184.844 170.978
 186.633 170.366 189.652 169.636 194.451  170.12  195.43  170.99  196.86 172.265
 200.477 172.492 203.539 172.782 204.594 173.089 208.327  175.46 210.141 176.367
 211.895   177.5 214.084 178.599  215.76 179.075  218.91 180.451 220.412 181.413
#Mann= 5 ,-1 , 0
       0     .04       0  171.78      .1       0 183.993    .036       0
  195.43      .1       0 200.477     .08       0
Bank Sta=184.844,195.43
XS Rating Curve= 0 ,0
Exp/Cntr=0.3,0.1

Type RM Length L Ch R = 1 ,4813.461,32.613,33.662,34.712
XS GIS Cut Line= 4
528512.0747009264776602.63910636 528512.07470106 4776602.6391059
528550.2941981694776471.60049305528570.4897343824776402.35847651
#Sta/Elev= 30
-4.79853171.995413.13564171.730421.10637171.339323.09901171.459138.04394171.3801
 66.9379 171.492 92.8427171.1938107.7879170.8551114.7622170.8399120.7402171.1732
122.7329171.0282 125.722170.4074127.7146170.7009   131.7 170.724 134.388  170.92
  151.88 171.029 154.468 170.829 160.062 170.963 165.591 170.922 169.117 170.949
 171.533 170.814  175.03 170.125 177.999 168.964 180.665 169.442 183.013 170.043
  184.97  170.82 187.568  171.22 189.992 171.768 190.923 172.318 203.827 180.909
#Mann= 5 ,-1 , 0
-4.79853     .04       0   131.7     .04       0 165.591      .1       0
 171.533    .036       0 187.568     .08       0
#XS Ineff= 1 ,-1
   131.5  157.71  180.49
Permanent Ineff=
       T
Bank Sta=171.533,184.97
XS Rating Curve= 0 ,0
Exp/Cntr=0.3,0.1

Type RM Length L Ch R = 1 ,4779.798,27.295,28.116,28.938
XS GIS Cut Line= 5
528528.9999986664776622.00000357         528529.        4776622.
  528573.6432108 4776502.4355151  528589.6681945 4776445.1337995
 528607.771236564776416.84784274
#Sta/Elev= 30
-53.3075171.6946-44.3562171.4329-38.3886171.0492-36.3994171.1371-30.4318 171.072
-19.4915170.6147-7.55647170.889710.34611170.873424.27057171.122736.20554171.1935
59.08116171.034973.00531170.8218  73.978 170.699  80.855 170.695  87.913 171.241
 126.434 171.811 128.275 171.491 136.082 172.103 136.458 171.867 139.715 170.012
 143.252 168.535 146.384 168.256 149.142 169.918 152.594 171.462 153.457 171.847
 154.248 172.355 156.352 174.519 160.741 177.997 163.349 179.542 167.062 181.368
#Mann= 5 ,-1 , 0
-53.3075     .04       0  87.913      .1       0 128.275     .04       0
 136.458    .036       0 152.594      .1       0
#Block Obstruct= 1 ,-1
   87.22   126.7  179.56
Bank Sta=136.458,153.457
XS Rating Curve= 0 ,0
Exp/Cntr=0.3,0.1

Type RM Length L Ch R = 1 ,4751.682,32.596,32.648,32.699
XS GIS Cut Line= 5
528545.2513617944776622.06265994528545.2513631064776622.06265636
528561.5003241634776577.69336945528602.3926020434776466.03323294
528630.2391210054776440.64055938
#Sta/Elev= 30
 -47.251170.6167-40.3602170.8742-21.6568170.2842       0 170.591  36.108 171.008
  71.857   170.7  79.496 170.965   85.64 170.072  101.54  169.52 102.564 169.874
 104.421 171.555 106.551 172.395 107.616 171.723   108.6 169.483 113.481 169.045
 116.135 169.746 117.673 171.028 118.913 171.499 123.165 171.059  124.82  169.89
 126.545 168.238 134.708 168.051 136.392 168.407 139.598 169.799 142.699 170.825
 146.208 171.485 147.693 172.779 148.705  174.12 150.551 175.688 156.598 178.358
#Mann= 5 ,-1 , 0
 -47.251     .04       0       0     .04       0 117.673      .1       0
  124.82    .036       0 139.598      .1       0
Levee=-1,-41.41,170.88,0,,,Levee 1,
#XS Ineff= 1 ,-1
   97.44  109.07     177
Permanent Ineff=
       T
Bank Sta=124.82,139.598
XS Rating Curve= 0 ,0
Exp/Cntr=0.3,0.1

Type RM Length L Ch R = 5 ,4749.109,,,
BEGIN DESCRIPTION:
E130
END DESCRIPTION:
IW Pilot Flow=0
#Inline Weir SE= 7
       0       0  118.04  169.68  123.49  169.68  130.69  169.66   138.4  169.69
  141.98   169.7  145.08   169.7
IW Dist,WD,Coef,Skew,MaxSub,Min_El,Is_Ogee,SpillHt,DesHd
0.1,3.45,1.7,0,0.98,, 0 ,,,0,0,