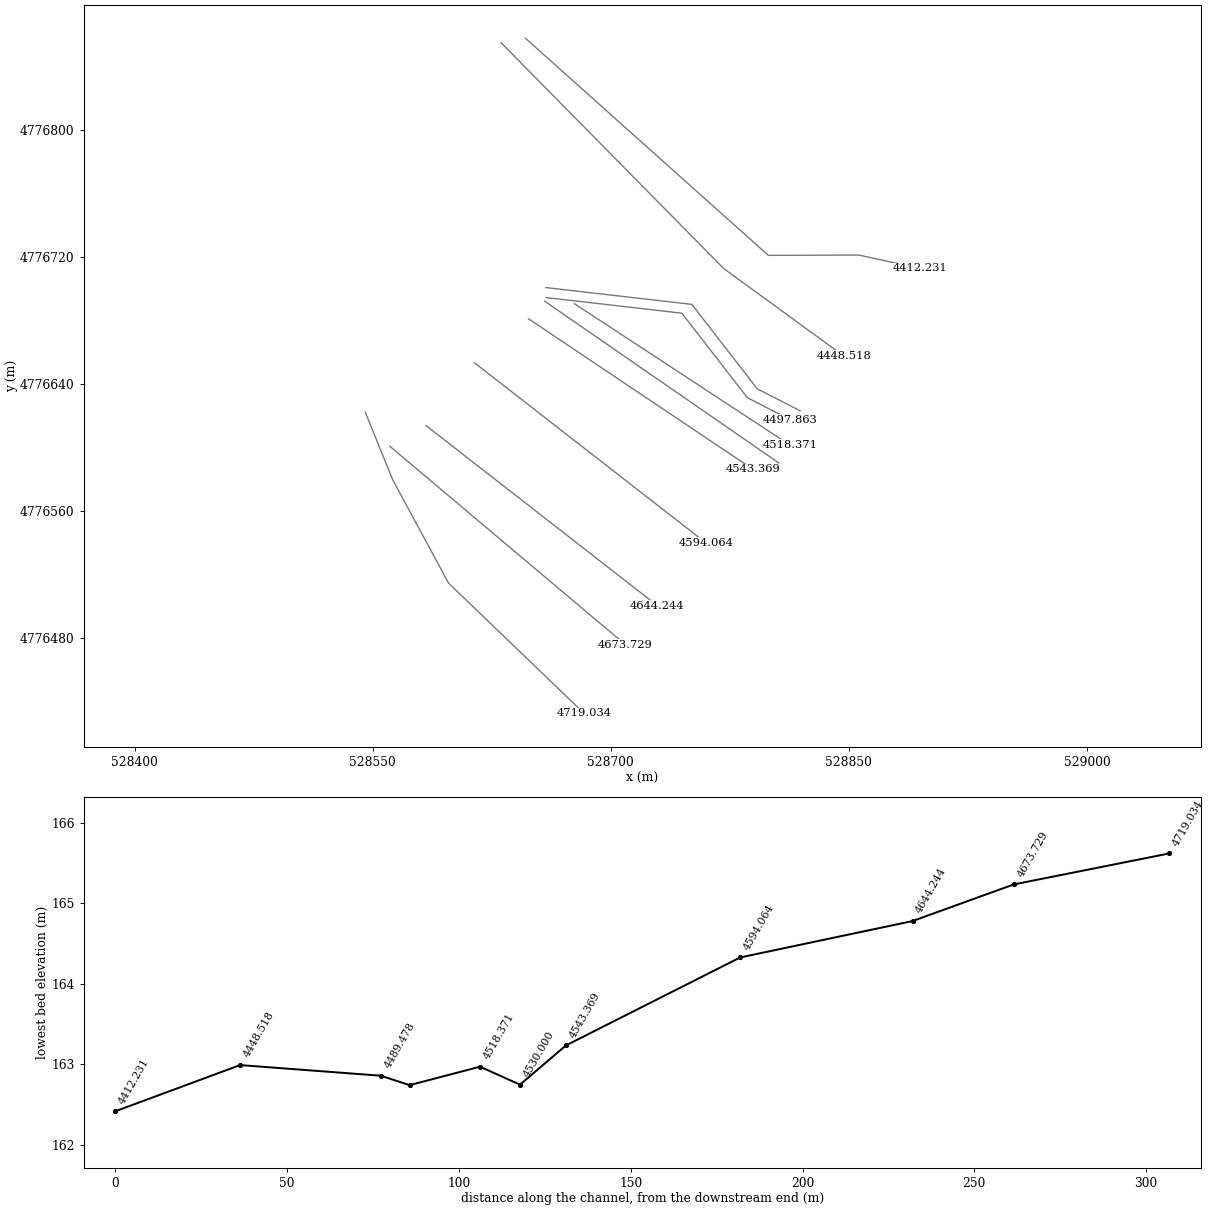
HEC-RAS study Durango.prj: Durango

--- Durango.g18 (geometry) --- (continued)

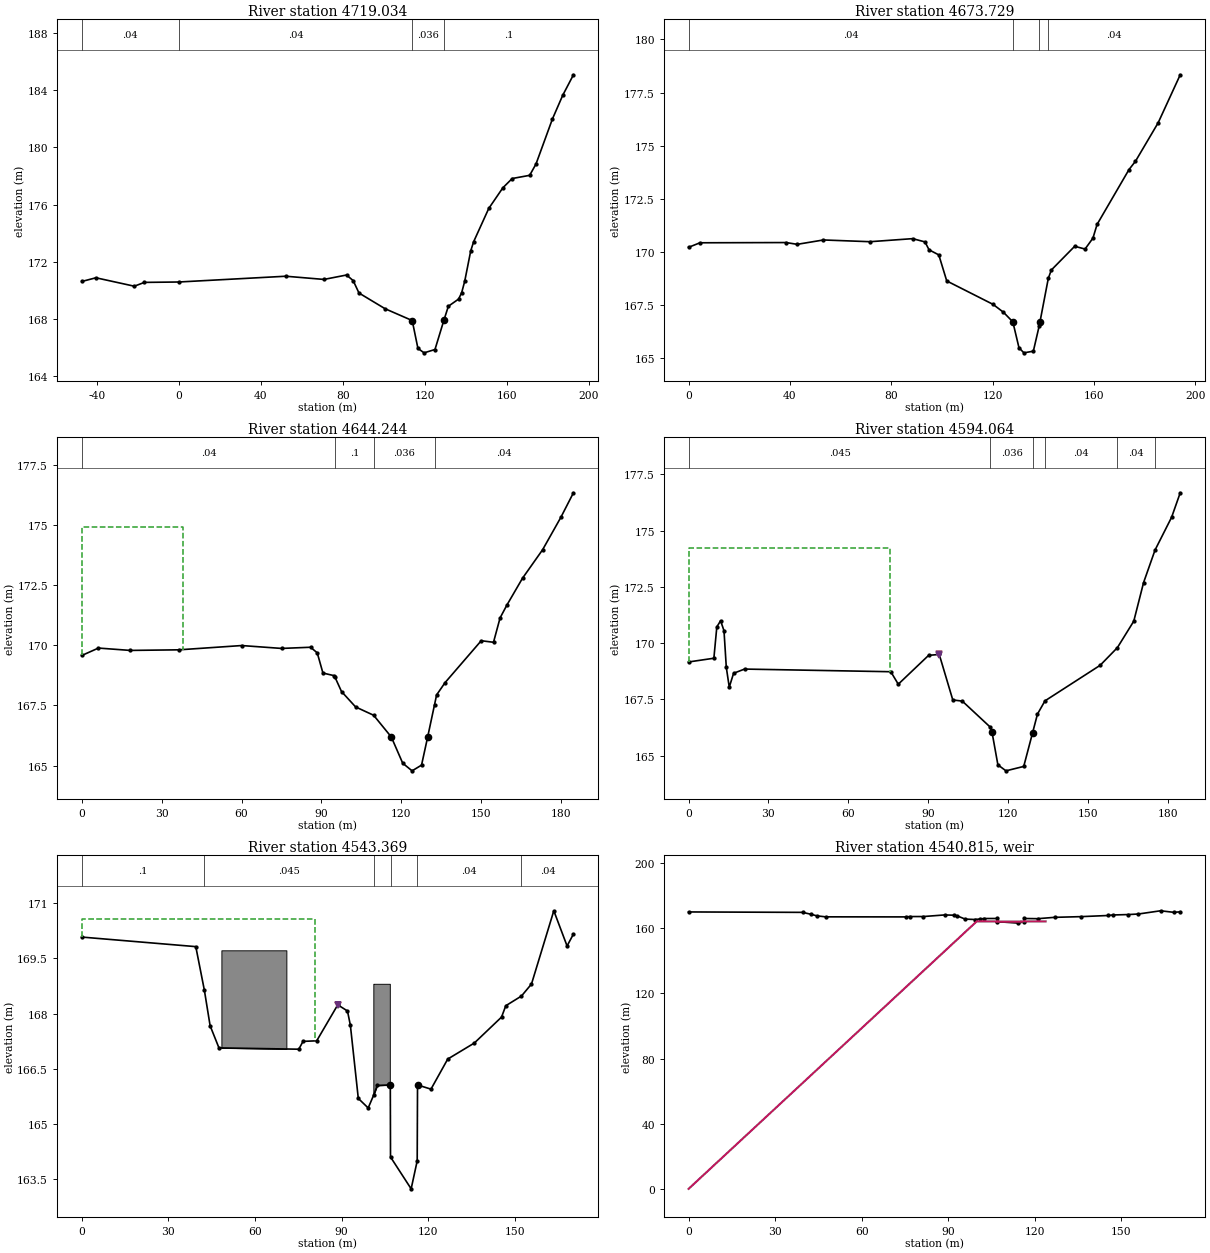
Type RM Length L Ch R = 1 ,4719.034,45.066,45.305,45.545
XS GIS Cut Line= 4
  528545.2513618 4776622.0626599  528562.5720152 4776579.3782203
  528597.7476335 4776514.3033266   528683.156969 4776432.2370473
#Sta/Elev= 30
 -47.251170.6167-40.3602170.8742-21.6568170.2842-16.7348170.5515       0 170.579
  52.204 170.983   70.79 170.759  81.799 171.068  85.032 170.678  87.874 169.806
 100.626 168.705 113.821 167.879 116.607  165.93 119.598 165.618 124.918 165.851
  129.24  167.89 131.446 168.881 136.412 169.381 137.914 169.823  139.41 170.629
 142.354 172.764 143.768   173.4 151.125 175.727 158.017 177.177 162.569 177.826
 171.082 178.049  174.18 178.846 182.177 181.996 187.185  183.65  192.42 185.091
#Mann= 4 ,-1 , 0
 -47.251     .04       0       0     .04       0 113.821    .036       0
  129.24      .1       0
Bank Sta=113.821,129.24
XS Rating Curve= 0 ,0
Exp/Cntr=0.3,0.1

Type RM Length L Ch R = 1 ,4673.729,29.343,29.485,29.626
XS GIS Cut Line= 2
528560.8131944674776600.48359951528709.2835669014776475.43530612
#Sta/Elev= 30
       0 170.206   4.485 170.419  38.508  170.43  42.879 170.346   53.24 170.552
  71.633  170.47  88.466 170.614  93.336  170.46  94.942 170.088  98.792 169.848
 101.925 168.621 120.212 167.517 124.304 167.147 128.025 166.692 128.058 166.675
 130.443 165.475 132.381 165.233  136.12 165.311 138.398 166.485  138.72  166.68
 142.034 168.746 143.217 169.135 152.443 170.254  156.54 170.124 159.645 170.637
 161.292 171.286 173.887 173.869 176.449 174.262 185.401 176.073 194.116 178.336
#Mann= 4 ,-1 , 0
       0     .04       0 128.058    .036       0 138.398      .1       0
 142.034     .04       0
Bank Sta=128.025,138.72
XS Rating Curve= 0 ,0
Exp/Cntr=0.3,0.1

Type RM Length L Ch R = 1 ,4644.244,50.181,50.18,50.18
XS GIS Cut Line= 2
528583.5674944674776613.56449951528729.3263944674776500.12319951
#Sta/Elev= 30
       0 169.582   6.243 169.891  18.194 169.793  36.517 169.818  60.069 169.996
  75.059 169.876  85.945 169.925  88.451 169.692  90.588 168.851  94.864  168.74
   95.14 168.673  97.565 168.081 102.863 167.439 109.631 167.093 116.274 166.188
 120.567 165.095  124.08 164.778 127.634 165.016  129.92  166.18 132.505 167.527
 133.288 167.938  136.47 168.452 150.058 170.197 154.669 170.132 157.139 171.147
 159.709 171.683 165.574 172.801 173.123 173.987 179.949  175.33 184.701 176.358
#Mann= 4 ,-1 , 0
       0     .04       0   95.14      .1       0 109.631    .036       0
 132.505     .04       0
#XS Ineff= 2 , 0
           37.89  174.92
Permanent Ineff=
       T       T
Bank Sta=116.274,129.92
XS Rating Curve= 0 ,0
Exp/Cntr=0.3,0.1

Type RM Length L Ch R = 1 ,4594.064,50.435,50.695,50.956
XS GIS Cut Line= 2
528614.2768944674776653.02249951528760.0357944674776539.58119951
#Sta/Elev= 30
       0 169.166   9.496 169.332    10.6 170.722  12.018     171  13.298 170.555
  14.163  168.93  15.274 168.045  16.903 168.663  21.027  168.85  75.962 168.732
  78.773 168.177   90.17  169.46  94.166   169.5  99.258 167.477 102.823 167.426
 113.404 166.261 113.997 166.042 116.197 164.594 119.225 164.326 125.903 164.522
  129.26  166.03 131.068  166.85  133.89 167.437 154.613 169.017 161.096 169.803
 167.247 170.979 170.931 172.695 175.245 174.143 181.465 175.599 184.701 176.687
#Mann= 6 ,-1 , 0
       0    .045       0 113.404    .036       0  129.26      .1       0
  133.89     .04       0 161.096     .04       0 175.245     .04       0
Levee=-1,93.92,169.51,0,,,Levee 23,
#XS Ineff= 2 , 0
           75.59  174.25
Permanent Ineff=
       T       T
Bank Sta=113.997,129.26
XS Rating Curve= 0 ,0
Exp/Cntr=0.3,0.1

Type RM Length L Ch R = 1 ,4543.369,13.421,13.369,13.317
XS GIS Cut Line= 2
528648.0981115334776680.90453896528789.6020187714776586.03401021
#Sta/Elev= 30
       0  170.08  39.498  169.82  42.472 168.635  44.462 167.669  47.523 167.067
  75.193 167.031   76.66 167.244  81.398 167.259  88.699 168.238  92.057  168.07
  93.064 167.683  95.813 165.692   99.24 165.433 101.094 165.774 102.365 166.045
   106.9  166.06 106.974   164.1 114.124 163.234 116.222 163.994 116.336 166.059
 120.997 165.945 126.804 166.763 136.004 167.198 145.446 167.904 146.924 168.213
 152.357 168.477 155.826 168.803 163.562 170.795  168.16 169.838 170.364 170.162
#Mann= 6 ,-1 , 0
       0      .1       0  42.472    .045       0 101.094      .1       0
 106.974    .036       0 116.222     .04       0 152.357     .04       0
Levee=-1,88.81,168.24,0,,,Levee 23,
#XS Ineff= 2 , 0
           80.72  170.56
Permanent Ineff=
       T       T
#Block Obstruct= 2 ,-1
   48.37   70.89  169.72  101.02  106.73  168.81
Bank Sta=106.9,116.336
XS Rating Curve= 0 ,0
Exp/Cntr=0.3,0.1

Type RM Length L Ch R = 5 ,4540.815,,,
BEGIN DESCRIPTION:
E131
END DESCRIPTION:
IW Pilot Flow=0
#Inline Weir SE= 7
       0       0   99.83  164.26  106.59  164.26  109.45  164.15  113.51  164.14
  116.09  164.28  123.72  164.28
IW Dist,WD,Coef,Skew,MaxSub,Min_El,Is_Ogee,SpillHt,DesHd
0.1,1,1.7,0,0.98,, 0 ,,,0,0,

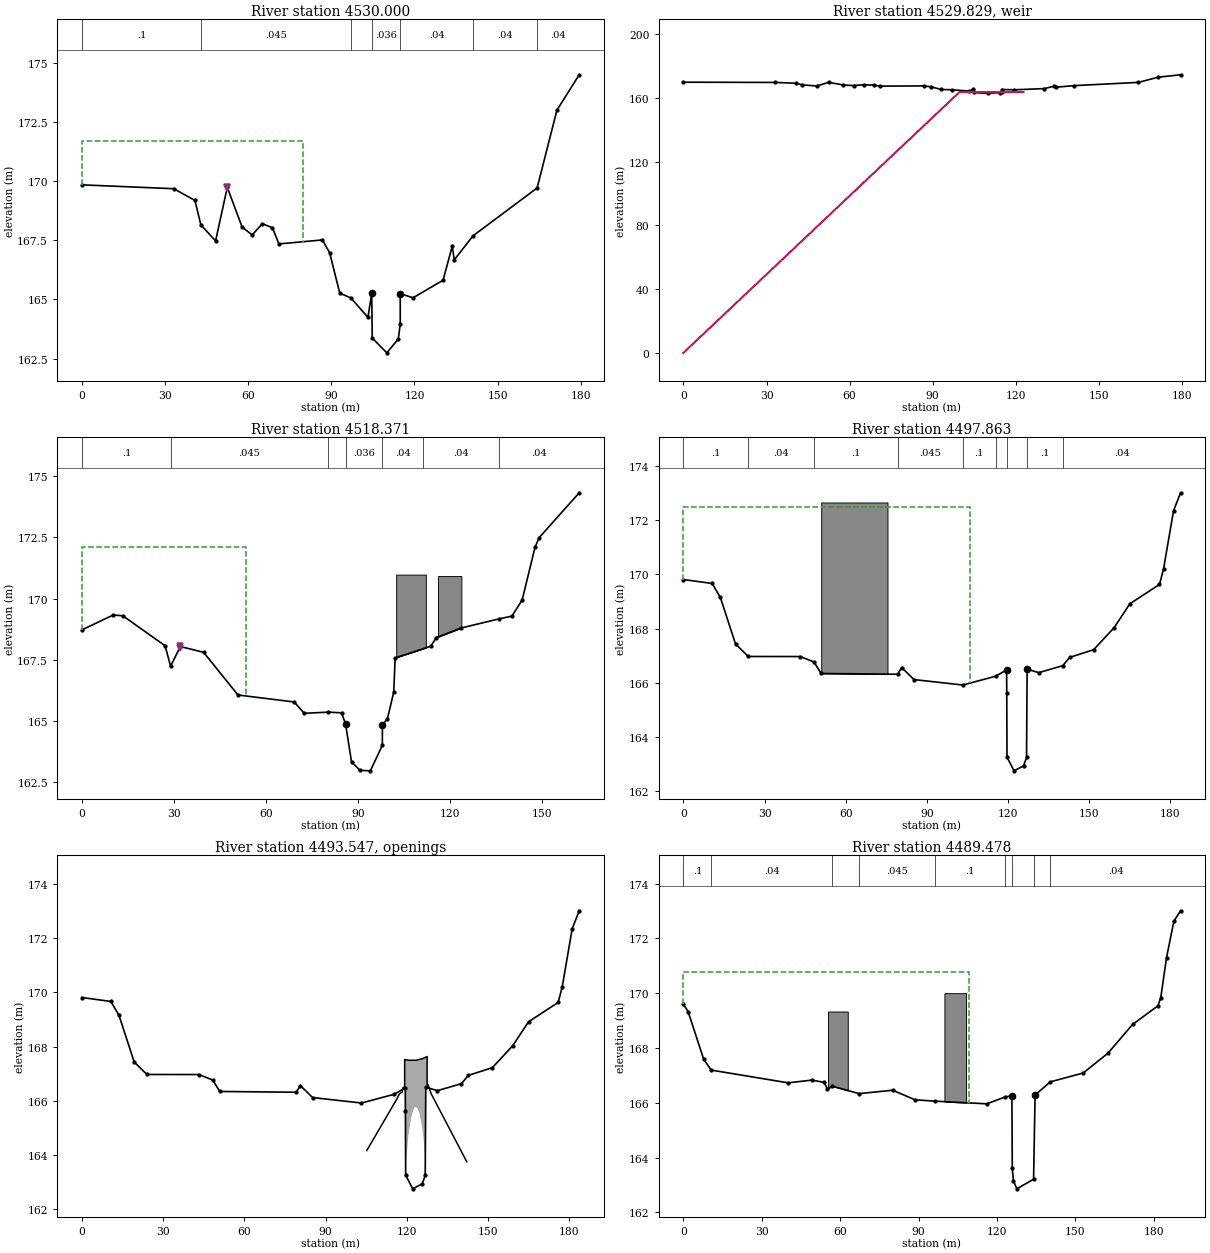
Type RM Length L Ch R = 1 ,4530.000,11.54,11.629,11.719
XS GIS Cut Line= 2
528658.2419597744776692.03644076528805.8971134544776590.01340744
#Sta/Elev= 30
       0  169.84   33.13 169.677  40.754  169.18  42.876 168.152  48.193 167.473
  52.419 169.735  57.771 168.057  61.417 167.725  65.064   168.2  68.711 168.029
  71.061 167.346  86.765 167.514  89.374 166.972  93.038 165.263  97.005 165.068
 103.199 164.247 104.568  165.26 104.754 163.372 110.015 162.747 114.163 163.332
 114.859 163.955  114.86  165.25 119.467  165.07 130.316 165.813 133.646 167.256
 134.347 166.671  141.12 167.686 164.272 169.708 171.438 172.998 179.473 174.488
#Mann= 7 ,-1 , 0
       0      .1       0  42.876    .045       0  97.005      .1       0
 104.568    .036       0  114.86     .04       0  141.12     .04       0
 164.272     .04       0
Levee=-1,52.33,169.73,0,,,Levee 23,
#XS Ineff= 2 , 0
           79.82  171.71
Permanent Ineff=
       T       T
Bank Sta=104.568,114.86
XS Rating Curve= 0 ,0
Exp/Cntr=0.3,0.1

Type RM Length L Ch R = 5 ,4529.829,,,
BEGIN DESCRIPTION:
E193
END DESCRIPTION:
IW Pilot Flow=0
#Inline Weir SE= 5
       0       0   99.66  163.63  104.51  163.63  114.87  163.62  122.76  163.62
IW Dist,WD,Coef,Skew,MaxSub,Min_El,Is_Ogee,SpillHt,DesHd
0.1,1,1.7,0,0.98,, 0 ,,,0,0,

Type RM Length L Ch R = 1 ,4518.371,21.725,20.508,19.291
XS GIS Cut Line= 2
528677.1198682794776690.37875909528812.7083095824776601.46272094
#Sta/Elev= 30
       0 168.727  10.122 169.329  13.281   169.3  27.087 168.074  28.861 167.241
  32.059 168.044   39.64 167.808  50.837 166.066  69.181 165.781  72.464 165.318
  80.147 165.365  84.621  165.34   85.92 164.891  87.878 163.337  90.653 162.992
  94.026  162.97  97.925 164.014  97.963 164.849  99.572 165.089 101.641 166.178
 102.115  167.58 113.671 168.055  115.58  168.41 123.523 168.797 135.989 169.172
 140.173 169.286  143.53  169.94  147.71 172.088 149.058 172.486 162.143  174.32
#Mann= 7 ,-1 , 0
       0      .1       0  28.861    .045       0  80.147      .1       0
   85.92    .036       0  97.963     .04       0 111.133     .04       0
 135.989     .04       0
Levee=-1,31.88,168.07,0,,,Levee 23,
#XS Ineff= 2 , 0
            53.6  172.12
Permanent Ineff=
       T       T
#Block Obstruct= 2 ,-1
  102.45  112.12  170.98  116.09   123.7  170.92
Bank Sta=85.92,97.963
XS Rating Curve= 0 ,0
Exp/Cntr=0.3,0.1

Type RM Length L Ch R = 1 ,4497.863,8.385,8.385,8.384
XS GIS Cut Line= 4
528659.2313189594776694.25946849528744.7369810254776684.42960571
 528786.03734473 4776631.1741661528812.9683329414776617.34921579
#Sta/Elev= 30
       0 169.811  10.609 169.667  13.629 169.158  19.246 167.431  23.959 166.968
  43.194 166.965  48.286 166.762  50.873  166.34  79.153 166.311  80.662  166.56
  85.207 166.114 103.259 165.913 115.386 166.237 119.442 166.472 119.497 165.626
 119.588  163.25 122.188 162.741 125.711 162.927 126.812 163.235  127.03   166.5
 131.331  166.37 140.208 166.628 142.748 166.934 151.607 167.218  159.13 168.026
 164.999 168.915 175.944  169.63  177.43 170.194 181.144 172.354 183.735 173.018
#Mann= 9 ,-1 , 0
       0      .1       0  23.959     .04       0  48.286      .1       0
  79.153    .045       0 103.259      .1       0 115.386      .1       0
 119.497    .036       0 126.812      .1       0 140.208     .04       0
#XS Ineff= 2 , 0
           105.9  172.51
Permanent Ineff=
       T       T
#Block Obstruct= 1 ,-1
   50.93   75.42  172.66
Bank Sta=119.442,127.03
XS Rating Curve= 0 ,0
Exp/Cntr=0.5,0.3

Type RM Length L Ch R = 4 ,4493.547,,,
BEGIN DESCRIPTION:
E132
END DESCRIPTION:
Bridge Culvert--1,0,-1,-1, 0
Deck Dist Width WeirC Skew NumUp NumDn MinLoCord MaxHiCord MaxSubmerge Is_Ogee
0.01,8.19,1.44,0, 34, 34, , , 0.95, 0, ,,,
 105.203 105.486 115.943  117.23 118.248 118.621 119.219 119.222 119.336  119.58
 119.612 119.875 120.575  120.88 121.546 122.622 123.192  123.48  123.81 124.617
 125.716 126.079 126.229 126.686 126.909 127.103 127.265  127.51 127.517 127.828
 128.518 128.992 142.027 142.167
 164.156 164.204 165.992 166.241 166.316 166.487 166.498 167.519 167.518 167.514
 167.513 167.509 167.498 167.493 167.493 167.494 167.494 167.494 167.503 167.523
 167.551 167.561 167.568 167.591 167.602 167.611 167.619 167.632 166.594 166.598
 166.403 166.261  163.77 163.744
 164.156 116.635 116.834 116.859 116.878 116.885 116.897 116.897 116.899  163.25
 163.326  163.83 164.685 164.894 165.353 165.706 165.767 165.756 165.743 165.564
 165.004 164.693 164.565 164.014 163.652 163.243 117.016 117.019 117.019 117.023
 117.031 117.037 117.192 163.744
 111.761 112.044 122.501 123.788 124.806 125.179 125.777  125.78 125.894 126.138
  126.17 126.433 127.133 127.438 128.104  129.18  129.75 130.038 130.368 131.175
 132.274 132.637 132.787 133.244 133.467 133.661 133.823 134.068 134.075 134.386
 135.076  135.55 148.585 148.725
 164.156 164.204 165.992 166.241 166.316 166.487 166.498 167.519 167.518 167.514
 167.513 167.509 167.498 167.493 167.493 167.494 167.494 167.494 167.503 167.523
 167.551 167.561 167.568 167.591 167.602 167.611 167.619 167.632 166.594 166.598
 166.403 166.261  163.77 163.744
 164.156 116.635 116.834 116.859 116.878 116.885 116.897 116.897 116.899  163.25
 163.326  163.83 164.685 164.894 165.353 165.706 165.767 165.756 165.743 165.564
 165.004 164.693 164.565 164.014 163.652 163.243 117.016 117.019 117.019 117.023
 117.031 117.037 117.192 163.744
BR Coef=-1 , 0 , 0 ,, 0 ,,,0.8,0,,0,
WSPro=,,,, 1 ,,,, 0 ,,,, 0 ,,,,-1 ,-1 ,-1 , 0 , 0 , 0 , 0 , 0
BC Mult= 1 ,0,119,0,125
BC Mult= 3 ,119,127,125,135
BC Mult= 1 ,127,200,135,200
BC Design=,, 0 ,, 0 ,,,,,,
BC Use User HTab Curves=0
BC User HTab FreeFlow(D)= 0

Type RM Length L Ch R = 1 ,4489.478,39.924,40.96,41.996
XS GIS Cut Line= 4
528658.9878948264776700.56642878528751.025453438 4776689.9856491
528792.3258171424776636.73020948528819.2568053534776622.90525918
#Sta/Elev= 30
       0 169.594   1.795 169.328   7.754 167.587  10.638 167.192  40.094 166.727
  49.154 166.827  53.905 166.743  55.144  166.49  56.846  166.61  67.236 166.333
  80.086 166.457  88.663 166.108  96.163 166.059  116.19 165.961 123.149 166.213
  125.75  166.25 125.891 163.603 126.324 163.154 127.632 162.858 134.047 163.208
  134.62  166.28  140.43 166.762 153.032 167.086 162.517 167.808 171.921 168.857
 181.644 169.537 182.717  169.83 184.945 171.301 187.757 172.628  190.31 173.007
#Mann= 9 ,-1 , 0
       0      .1       0  10.638     .04       0  56.846      .1       0
  67.236    .045       0  96.163      .1       0 123.149      .1       0
 125.891    .036       0 134.047      .1       0  140.43     .04       0
#XS Ineff= 2 , 0
          109.43  170.78
Permanent Ineff=
       T       T
#Block Obstruct= 2 ,-1
   55.33   62.91  169.33   99.91  108.19     170
Bank Sta=125.75,134.62
XS Rating Curve= 0 ,0
Exp/Cntr=0.5,0.3

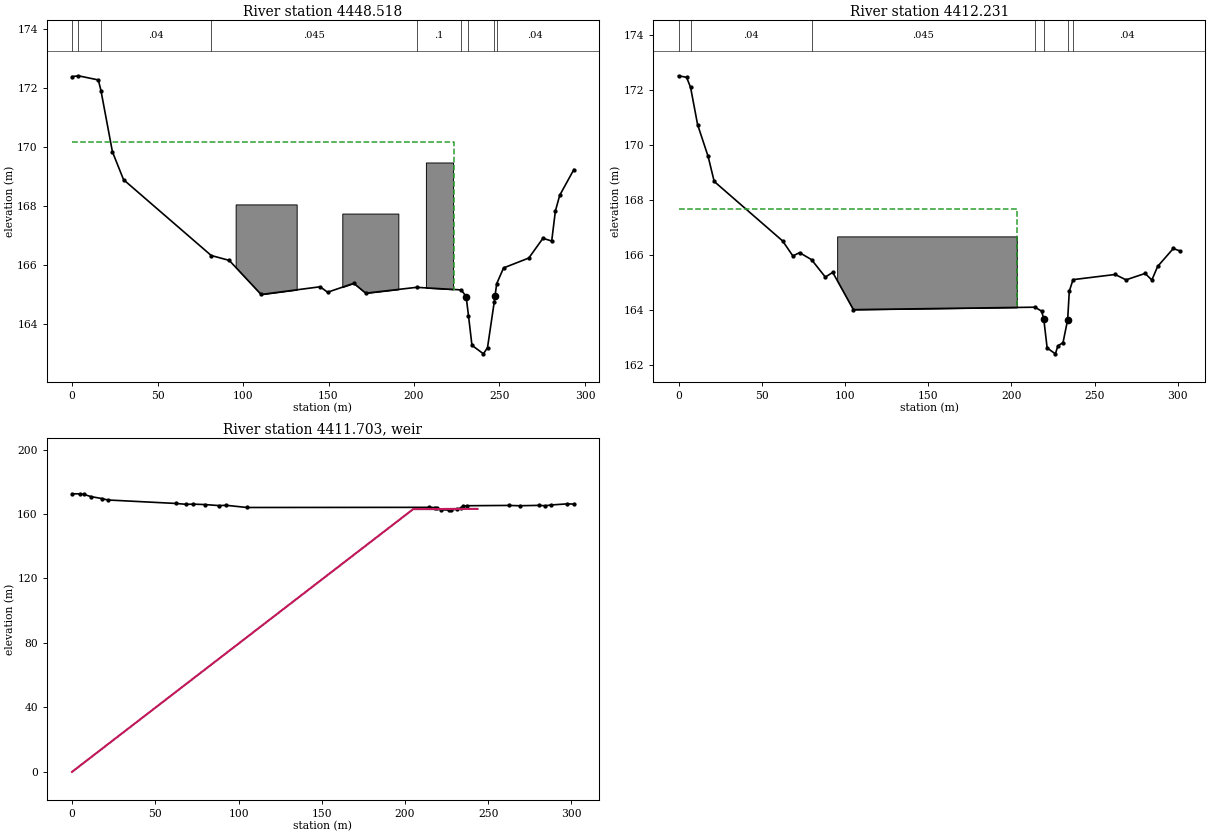
Type RM Length L Ch R = 1 ,4448.518,33.946,36.287,38.627
XS GIS Cut Line= 3
528630.7247944674776854.95719951528771.2073944674776712.49599951
528846.7345683364776657.49653428
#Sta/Elev= 30
       0 172.376    3.61 172.406  15.369 172.265  16.906 171.902  23.604 169.832
  30.117 168.887   81.39  166.32  91.942 166.154 110.567     165   145.1 165.261
 149.459 165.076 164.762 165.379 171.784 165.044 201.493 165.242 227.644 165.155
 230.491 164.931 231.871 164.284   233.9  163.28 240.605  162.99     243   163.2
 246.945  164.75  247.39  164.95 248.395 165.369 252.404   165.9  267.15 166.234
 275.443 166.904 280.545  166.81 282.693 167.824 285.228 168.358 293.507 169.231
#Mann= 9 ,-1 , 0
       0     .04       0    3.61      .1       0  16.906     .04       0
   81.39    .045       0 201.493      .1       0 227.644      .1       0
 231.871    .036       0 246.945      .1       0 248.395     .04       0
#XS Ineff= 2 , 0
          223.61  170.18
Permanent Ineff=
       T       T
#Block Obstruct= 3 ,-1
   95.68  131.37  168.05  158.06  190.84  167.74  206.96  222.82  169.47
Bank Sta=230.491,247.39
XS Rating Curve= 0 ,0
Exp/Cntr=0.3,0.1

Type RM Length L Ch R = 1 ,4412.231,44.996,44.89,44.785
XS GIS Cut Line= 4
528646.2315548524776857.63072926528799.2555599314776720.85743417
528856.2966781764776721.06112898528894.5758795864776712.74807498
#Sta/Elev= 30
       0 172.533   4.858 172.476   7.235 172.109  11.453 170.756  17.777 169.597
   21.42 168.689  62.536 166.524  68.675  165.98  72.731 166.098  79.915 165.842
  88.194  165.21  92.628 165.381 105.025 164.024 214.152 164.114   218.1  163.97
 219.427 163.681  221.44 162.631  226.38 162.417 227.912 162.708 230.978 162.825
  233.77  163.66 234.755   164.7 237.002 165.116 262.282 165.304 268.823 165.109
 280.319 165.342 284.345 165.101 287.821 165.597 297.245  166.25 301.453 166.154
#Mann= 7 ,-1 , 0
       0      .1       0   7.235     .04       0  79.915    .045       0
 214.152      .1       0 219.427    .036       0  233.77      .1       0
 237.002     .04       0
#XS Ineff= 2 , 0
          203.22   167.7
Permanent Ineff=
       T       T
#Block Obstruct= 1 ,-1
   95.29  203.22  166.69
Bank Sta=219.427,233.77
XS Rating Curve= 0 ,0
Exp/Cntr=0.3,0.1

Type RM Length L Ch R = 5 ,4411.703,,,
BEGIN DESCRIPTION:
E133
END DESCRIPTION:
IW Pilot Flow=0
#Inline Weir SE= 6
       0       0  204.95  163.02  218.95  163.02  226.61  163.13  234.36  163.15
  243.55  163.15
IW Dist,WD,Coef,Skew,MaxSub,Min_El,Is_Ogee,SpillHt,DesHd
0.1,1,1.7,0,0.98,, 0 ,,,0,0,