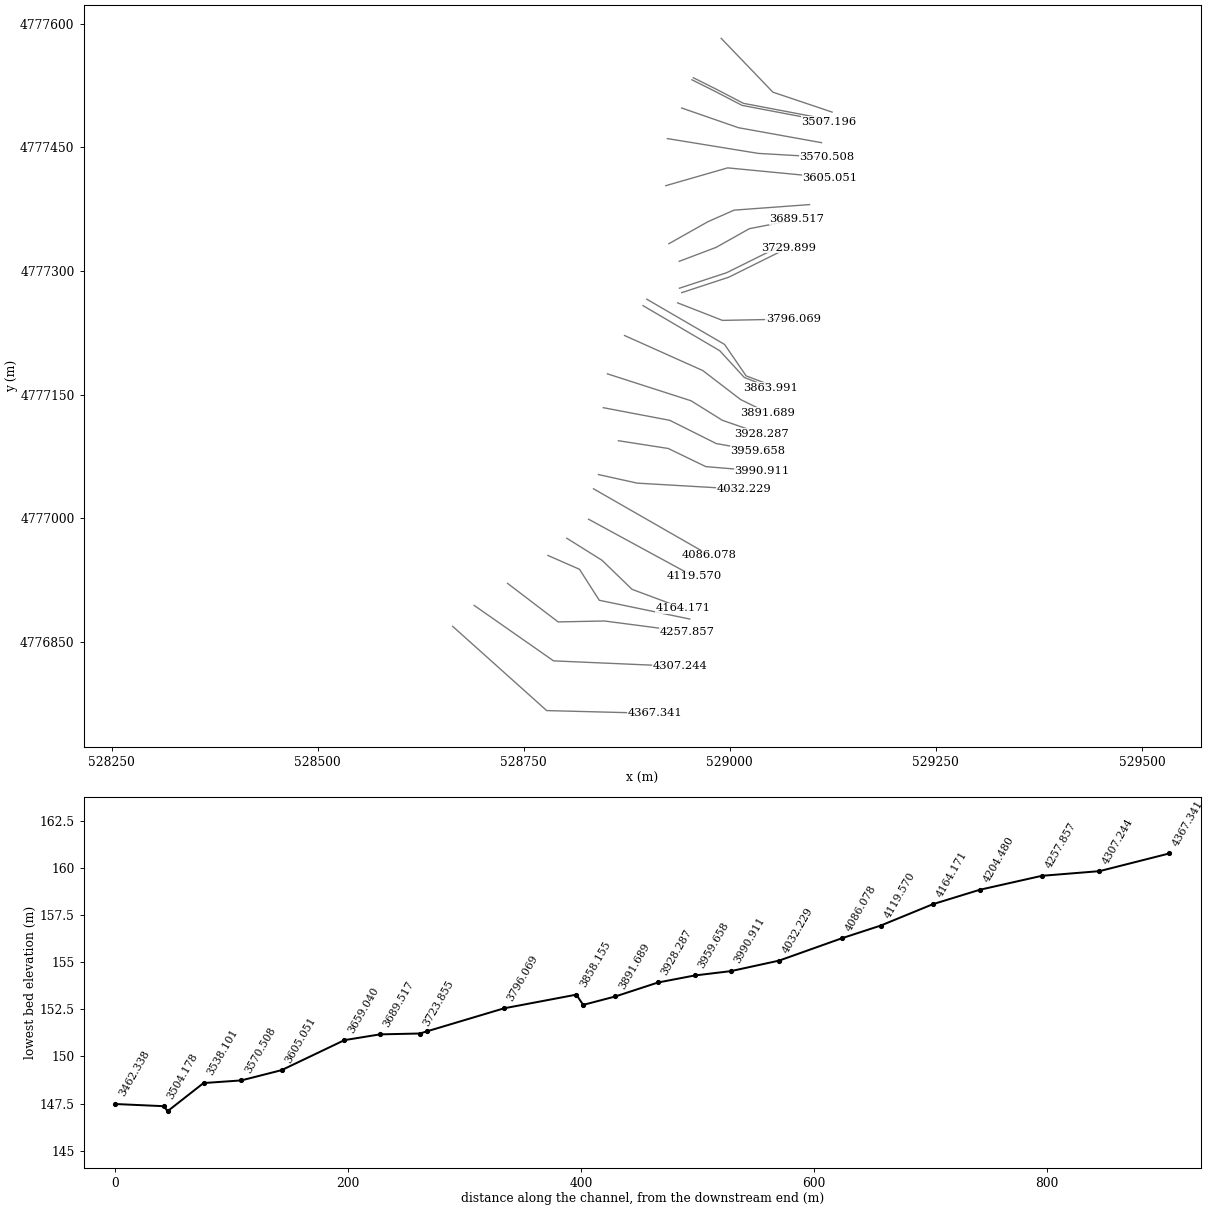
HEC-RAS study Durango.prj: Durango

--- Durango.g18 (geometry) --- (continued)

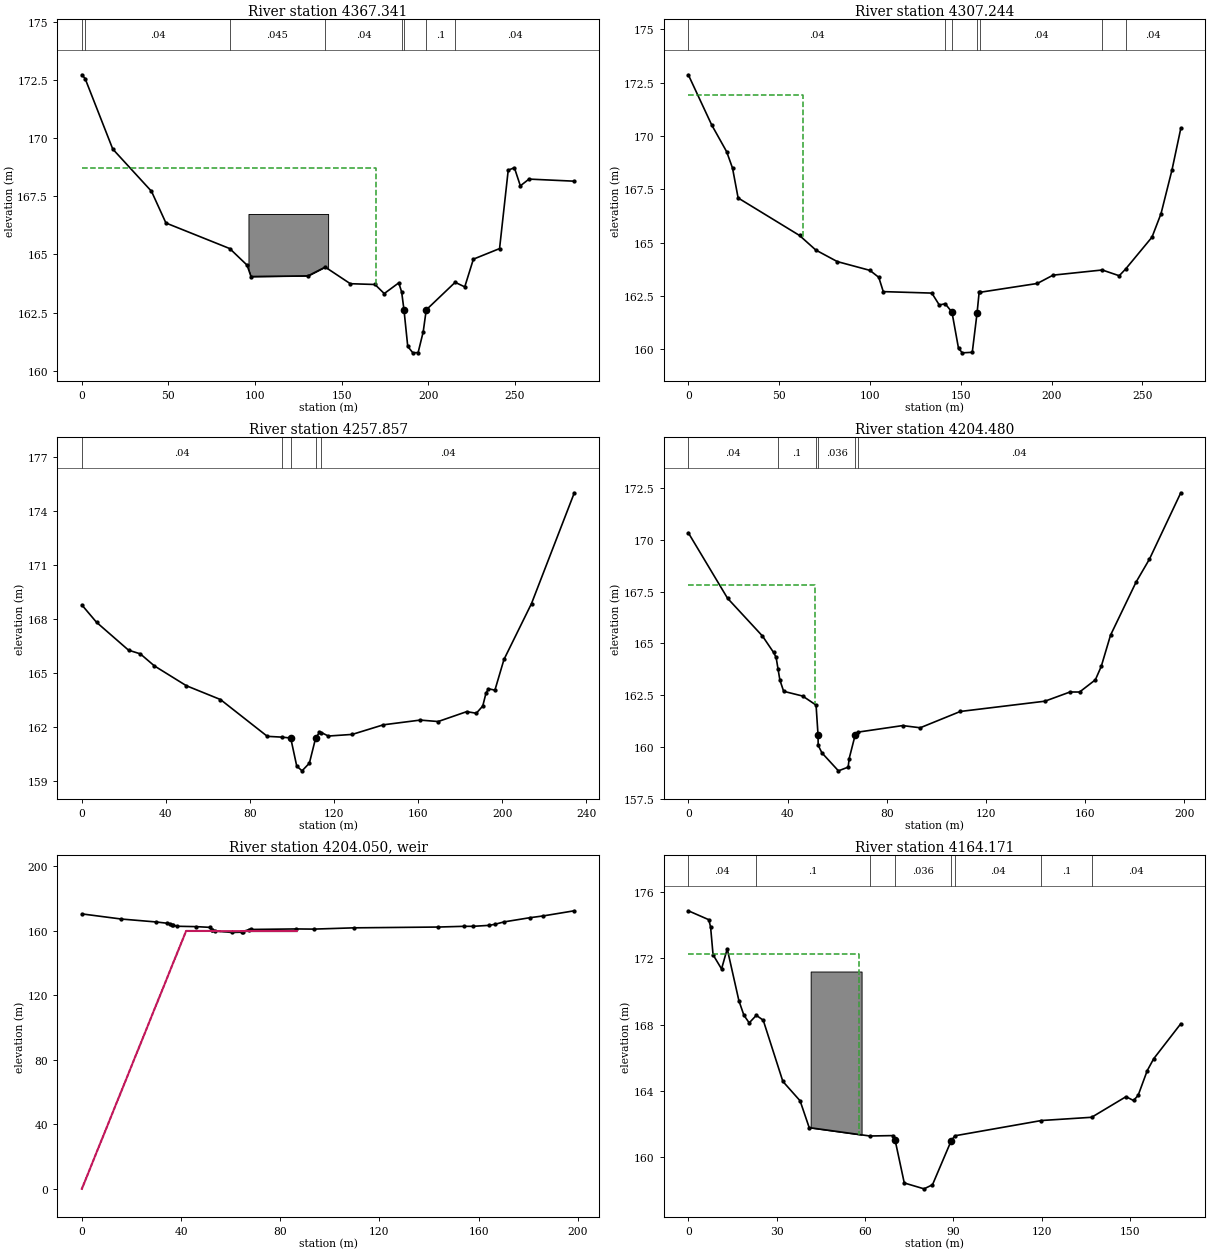
Type RM Length L Ch R = 1 ,4367.341,60.162,60.096,60.031
XS GIS Cut Line= 3
528663.7019176274776868.80760397528777.8028292374776766.57846351
528908.9291526114776763.19180846
#Sta/Elev= 30
       0 172.721   1.877  172.56  17.843 169.529  40.201 167.714  48.547 166.351
  85.396 165.252  95.395  164.54  97.657 164.049 130.626  164.08 140.507 164.458
 155.012 163.742 169.275 163.708 174.605 163.318 183.009 163.779 184.669 163.382
  186.02  162.61 188.179 161.048 191.138 160.771 194.181 160.785 197.117 161.677
 198.859 162.618 215.552 163.802 221.098 163.606  226.08 164.797 241.197 165.251
 246.198 168.621 249.755 168.728 253.201 167.948 258.202 168.238 284.369 168.148
#Mann= 8 ,-1 , 0
       0      .1       0   1.877     .04       0  85.396    .045       0
 140.507     .04       0 184.669      .1       0  186.02    .036       0
 198.859      .1       0 215.552     .04       0
#XS Ineff= 2 , 0
          169.96  168.72
Permanent Ineff=
       T       T
#Block Obstruct= 1 ,-1
   96.21   142.2  166.74
Bank Sta=186.02,198.859
XS Rating Curve= 0 ,0
Exp/Cntr=0.3,0.1

Type RM Length L Ch R = 1 ,4307.244,49.155,49.388,49.62
XS GIS Cut Line= 3
528689.8243933024776894.16360069528786.1175933034776826.89020069
528939.6075561984776820.19535318
#Sta/Elev= 30
       0 172.875  12.853 170.524   21.11 169.265  24.333 168.497  27.417 167.096
  61.225 165.336  70.187 164.652  82.008 164.111  99.965 163.699 104.844 163.372
  107.32 162.702 134.056 162.633 138.139 162.076 141.407 162.132 145.128 161.742
 148.743  160.04 150.862  159.83 156.315 159.855  158.97  161.71 160.095  162.67
 160.357 162.668 192.091 163.084 200.802 163.475 227.862 163.717 237.201 163.447
 240.685 163.758  255.25 165.257 260.227 166.362 266.261 168.412 271.102 170.359
#Mann= 7 ,-1 , 0
       0     .04       0 141.407      .1       0 145.128    .036       0
  158.97      .1       0 160.357     .04       0 227.862     .04       0
 240.685     .04       0
#XS Ineff= 2 , 0
           62.91  171.93
Permanent Ineff=
       T       T
Bank Sta=145.128,158.97
XS Rating Curve= 0 ,0
Exp/Cntr=0.3,0.1

Type RM Length L Ch R = 1 ,4257.857,57.152,53.377,49.617
XS GIS Cut Line= 4
528730.3157446364776920.91148846528791.6893308314776874.15802319
528847.9035775844776875.26343198528947.9648823894776862.21217555
#Sta/Elev= 30
       0 168.778   6.972 167.818  22.205 166.272  27.805 166.067  34.514 165.399
  49.752 164.299  65.941 163.535  88.237 161.495  95.378  161.45  99.364   161.4
 102.229 159.847 104.753 159.583  108.24 160.007   111.2  161.39 113.019 161.714
 113.981 161.705 117.242 161.512 128.616 161.602 143.437 162.134 160.954 162.396
   169.5 162.316 183.086 162.864  187.66 162.775 190.727 163.176 192.244 163.884
 193.455 164.134 196.504 164.053 200.812 165.755 213.922 168.857 234.287 174.995
#Mann= 5 ,-1 , 0
       0     .04       0  95.378      .1       0  99.364    .036       0
   111.2      .1       0 113.981     .04       0
Bank Sta=99.364,111.2
XS Rating Curve= 0 ,0
Exp/Cntr=0.3,0.1

Type RM Length L Ch R = 1 ,4204.480,39.479,40.31,41.125
XS GIS Cut Line= 4
528779.2828314074776954.78999053528817.5701410394776938.00435388
528841.5821311384776900.41534116528951.4235314074776877.62349053
#Sta/Elev= 30
       0 170.348  15.814 167.184  29.913 165.356  34.381 164.565  35.401 164.326
  36.163 163.777   36.92 163.233  38.438 162.686  46.102 162.457  51.514 162.021
    52.3  160.59  52.372 160.076  53.877 159.711  60.528 158.842  64.456 159.021
  64.865 159.437  67.324 160.592  68.236  160.71  86.409 161.029  93.519 160.924
 109.686 161.712 143.795 162.208 153.918 162.653 157.784 162.652 164.143 163.241
 166.518 163.891  170.26   165.4 180.562 167.966 185.964 169.078 198.591 172.282
#Mann= 6 ,-1 , 0
       0     .04       0  36.163      .1       0  51.514      .1       0
    52.3    .036       0  67.324      .1       0  68.236     .04       0
#XS Ineff= 2 , 0
           50.93  167.81
Permanent Ineff=
       T       T
Bank Sta=52.3,67.324
XS Rating Curve= 0 ,0
Exp/Cntr=0.3,0.1

Type RM Length L Ch R = 5 ,4204.050,,,
BEGIN DESCRIPTION:
E134
END DESCRIPTION:
IW Pilot Flow=0
#Inline Weir SE= 7
       0       0   42.04  159.77   52.66  159.77   55.43  159.66    62.2  159.62
   64.89  159.71   86.65  159.71
IW Dist,WD,Coef,Skew,MaxSub,Min_El,Is_Ogee,SpillHt,DesHd
0.1,0.75,1.7,0,0.98,, 0 ,,,0,0,

Type RM Length L Ch R = 1 ,4164.171,43.602,44.601,45.6
XS GIS Cut Line= 4
528802.2059143794776975.65354432528844.9780965744776948.87529752
 528881.35105538 4776913.6565172528943.3480824974776890.57251774
#Sta/Elev= 30
       0 174.868   6.949 174.329   7.562 173.892     8.4 172.213  11.285 171.355
  13.215  172.57  17.184 169.433  18.869 168.564  20.674 168.098  23.097 168.555
  25.443 168.258  32.109 164.563  37.959 163.392  41.051 161.773  61.664 161.267
  69.489 161.292  70.197 161.043   73.34  158.43  80.055 158.076  82.924 158.323
  89.285 160.985  90.515 161.279 119.934 162.202 136.976 162.397 148.639 163.641
 151.195 163.411  152.76  163.72  155.86 165.219  158.06 165.937 167.248 168.047
#Mann= 8 ,-1 , 0
       0     .04       0  23.097      .1       0  61.664      .1       0
  70.197    .036       0  89.285      .1       0  90.515     .04       0
 119.934      .1       0 136.976     .04       0
#XS Ineff= 2 , 0
           58.04  172.26
Permanent Ineff=
       T       T
#Block Obstruct= 1 ,-1
   41.55   58.84   171.2
Bank Sta=70.197,89.285
XS Rating Curve= 0 ,0
Exp/Cntr=0.3,0.1

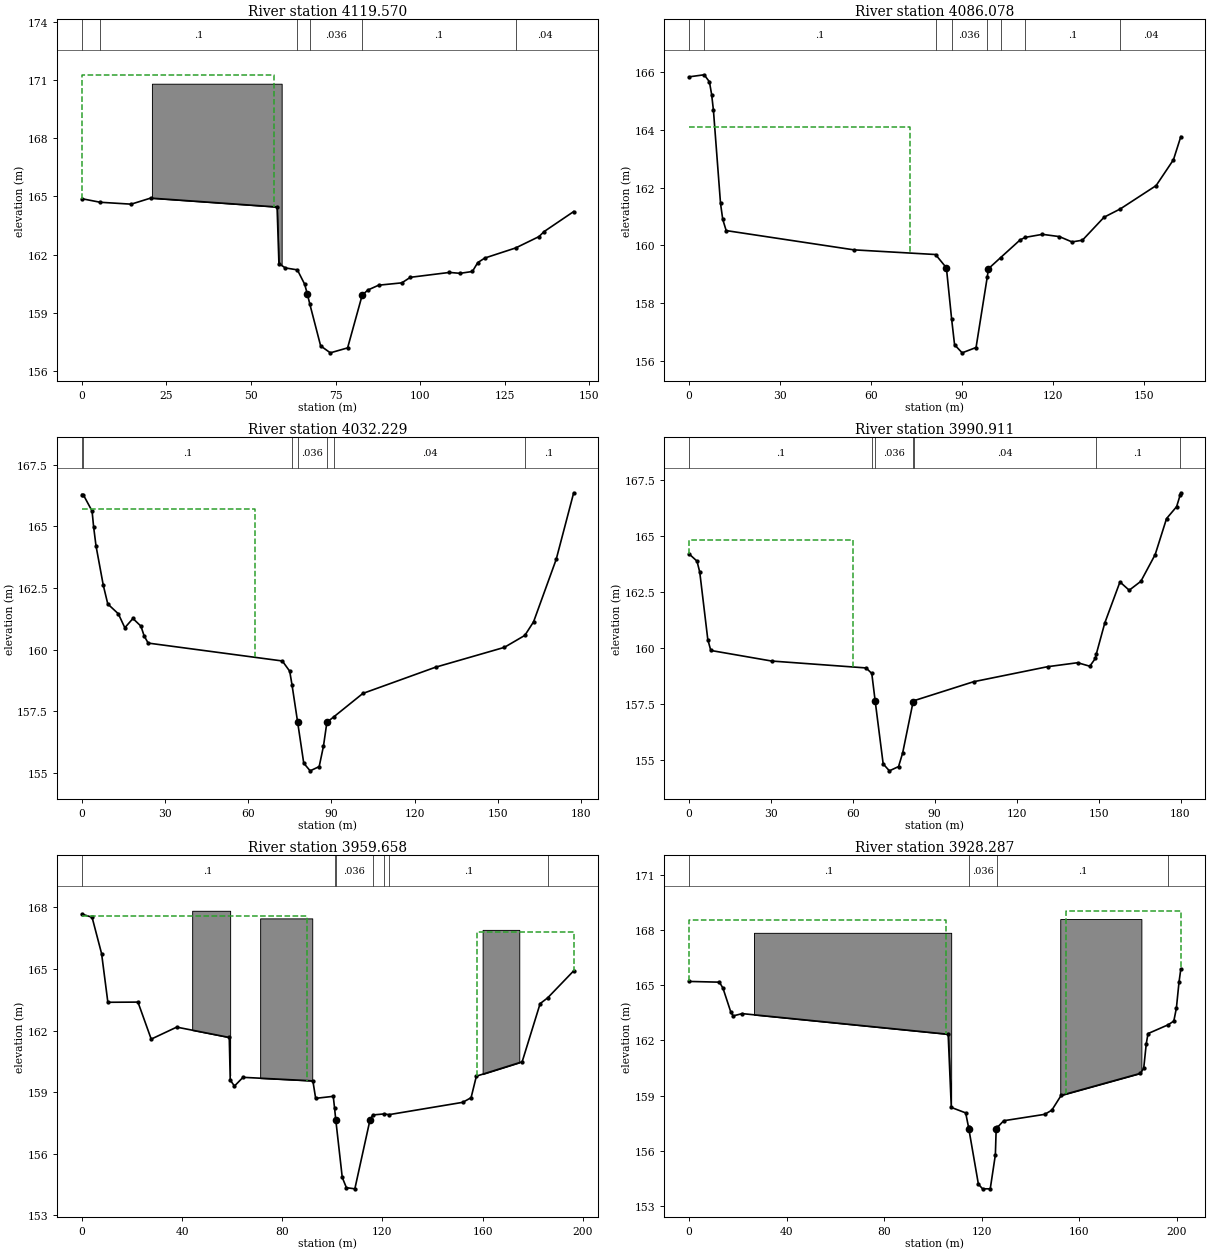
Type RM Length L Ch R = 1 ,4119.570,33.578,33.492,33.406
XS GIS Cut Line= 2
528828.5875944674776998.73749951528956.3129427054776929.28140102
#Sta/Elev= 28
       0 164.886   5.423 164.703  14.582 164.605  20.343 164.917  57.718 164.459
  58.261 161.544  60.145 161.321  63.709  161.22  65.872 160.481   66.68  159.96
  67.367 159.475  70.593 157.304  73.455 156.946  78.562 157.201  82.868 159.915
  84.532  160.18  87.735 160.431  94.585 160.551  97.116 160.837  108.66 161.088
 111.811 161.042 115.445 161.137 117.038 161.596 119.135 161.831 128.233 162.349
 135.138 162.935 136.645 163.193 145.389 164.224
#Mann= 6 ,-1 , 0
       0     .04       0   5.423      .1       0  63.709      .1       0
  67.367    .036       0  82.868      .1       0 128.233     .04       0
#XS Ineff= 2 , 0
           56.81  171.27
Permanent Ineff=
       T       T
#Block Obstruct= 1 ,-1
   20.72   59.07  170.81
Bank Sta=66.68,82.868
XS Rating Curve= 0 ,0
Exp/Cntr=0.3,0.1

Type RM Length L Ch R = 1 ,4086.078,52.129,53.849,55.569
XS GIS Cut Line= 2
528834.5701333094777035.65986116 528975.36432115 4776954.9132778
#Sta/Elev= 29
       0 165.842   5.031 165.914   6.755  165.67   7.487 165.228   8.079 164.681
  10.418 161.451  11.151 160.898  12.283  160.51  54.413 159.842  81.364  159.68
   84.95  159.22   86.69 157.429  87.647  156.55  90.149  156.27  94.735 156.455
  98.416 158.888  98.827 159.188  102.82 159.571 109.303 160.189 110.968 160.275
 116.648  160.38 122.254 160.301 126.389 160.117 129.835 160.176 136.976 160.974
 142.358 161.263 154.151  162.07 159.873 162.967 162.305  163.77
#Mann= 8 ,-1 , 0
       0     .04       0   5.031      .1       0  81.364      .1       0
   86.69    .036       0  98.416      .1       0  102.82     .04       0
 110.968      .1       0 142.358     .04       0
#XS Ineff= 2 , 0
           72.95  164.09
Permanent Ineff=
       T       T
Bank Sta=84.95,98.827
XS Rating Curve= 0 ,0
Exp/Cntr=0.3,0.1

Type RM Length L Ch R = 1 ,4032.229,42.759,41.318,39.877
XS GIS Cut Line= 3
528840.6242944674777052.90249951528887.6166944674777042.51469951
529016.6893767994777035.00748512
#Sta/Elev= 30
       0 166.285    .568 166.268   3.697 165.615   4.247 164.983   5.108 164.208
   7.738 162.608   9.368 161.847  13.167  161.45  15.513 160.884  18.437  161.26
  21.319 160.949  22.491  160.55  23.937 160.263  72.322 159.538  74.984 159.124
  75.819 158.568   77.83  157.07  80.047 155.397  82.352 155.085  85.616 155.257
  87.162 156.086  88.396 157.052  90.997 157.283 101.371 158.222 127.577 159.285
 152.397 160.089   159.8 160.575 162.946 161.125 171.111 163.657 177.418 166.355
#Mann= 7 ,-1 , 0
       0     .04       0    .568      .1       0  75.819      .1       0
   77.83    .036       0  88.396      .1       0  90.997     .04       0
   159.8      .1       0
#XS Ineff= 2 , 0
           62.56   165.7
Permanent Ineff=
       T       T
Bank Sta=77.83,88.396
XS Rating Curve= 0 ,0
Exp/Cntr=0.3,0.1

Type RM Length L Ch R = 1 ,3990.911,31.304,31.253,31.201
XS GIS Cut Line= 4
528864.8624843384777093.95904155528925.2106543514777084.56055605
528970.8168880344777062.54995754 529038.98179454 4777056.8597567
#Sta/Elev= 30
       0 164.203   2.944 163.876   3.956 163.384   6.906 160.377   8.004 159.894
   30.27 159.423  64.857 159.115   66.95 158.869   68.18  157.65  71.122 154.837
  73.397 154.528  76.753 154.718  78.252 155.323  82.101 157.617  82.242 157.649
 104.217   158.5 131.315  159.17 142.339 159.348 146.792 159.191 148.799 159.538
 149.156 159.729 152.276 161.121  157.83 162.948 161.216 162.579 165.481 162.976
 170.727 164.168 174.889 165.773 178.576 166.304  179.83 166.805 180.118 166.923
#Mann= 7 ,-1 , 0
       0      .1       0   66.95      .1       0   68.18    .036       0
  82.101      .1       0  82.242     .04       0 149.156      .1       0
  179.83     .08       0
#XS Ineff= 2 , 0
           60.09  164.81
Permanent Ineff=
       T       T
Bank Sta=68.18,82.101
XS Rating Curve= 0 ,0
Exp/Cntr=0.3,0.1

Type RM Length L Ch R = 1 ,3959.658,31.716,31.371,31.027
XS GIS Cut Line= 4
528846.5601944674777134.02629951528927.1892944674777118.69189951
528983.5801944674777090.49639951529034.0351944674777081.59259951
#Sta/Elev= 30
       0 167.669   4.093 167.514   7.895 165.742  10.394 163.376  22.406 163.385
  27.699 161.583  37.878 162.167  58.859 161.664  59.254 159.586  60.938 159.298
  64.344 159.723  92.236  159.55  93.351   158.7 100.375 158.798 100.907 158.211
  101.38  157.65 103.968 154.849 105.622 154.352 108.991 154.295 115.003  157.63
 116.159 157.891 120.543  157.94 122.664 157.907 152.066 158.506   155.4 158.732
 157.501 159.779 175.779 160.479 182.958 163.311 185.969 163.591 196.356 164.907
#Mann= 7 ,-1 , 0
       0      .1       0 100.907      .1       0  101.38    .036       0
 116.159      .1       0 120.543     .04       0 122.664      .1       0
 185.969      .1       0
#XS Ineff= 2 , 0
           90.04  167.59  157.71          166.79
Permanent Ineff=
       T       T
#Block Obstruct= 3 ,-1
   44.05   59.21  167.83   71.19   91.98  167.46     160  174.63   166.9
Bank Sta=101.38,115.003
XS Rating Curve= 0 ,0
Exp/Cntr=0.3,0.1

Type RM Length L Ch R = 1 ,3928.287,36.953,36.598,36.242
XS GIS Cut Line= 4
528851.5067417944777175.08281107528952.9114537024777142.43544041
528991.0000528094777118.69189811529038.4871374094777102.36821278
#Sta/Elev= 30
       0 165.214  12.482 165.174  13.935  164.85  17.086 163.576    18.1 163.337
  21.822 163.462 106.256 162.339 107.543 158.355 113.435 158.058 114.614 157.276
  114.71   157.2 118.646 154.181 120.353 153.926 123.503 153.924 125.606 155.773
 125.939   157.2 126.421 157.268  129.03 157.631 145.839 157.979 148.754 158.207
 152.573 159.012 185.009 160.208 186.411 160.484 187.472 161.828 188.182 162.375
 196.507 162.858 198.756 163.059 199.813 163.761 200.871  165.16 201.628 165.893
#Mann= 4 ,-1 , 0
       0      .1       0 114.614    .036       0 126.421      .1       0
 196.507     .08       0
#XS Ineff= 2 , 0
          105.51  168.54  154.41          169.06
Permanent Ineff=
       T       T
#Block Obstruct= 2 ,-1
   26.65  107.49  167.86   152.2  185.46  168.61
Bank Sta=114.71,125.939
XS Rating Curve= 0 ,0
Exp/Cntr=0.3,0.1

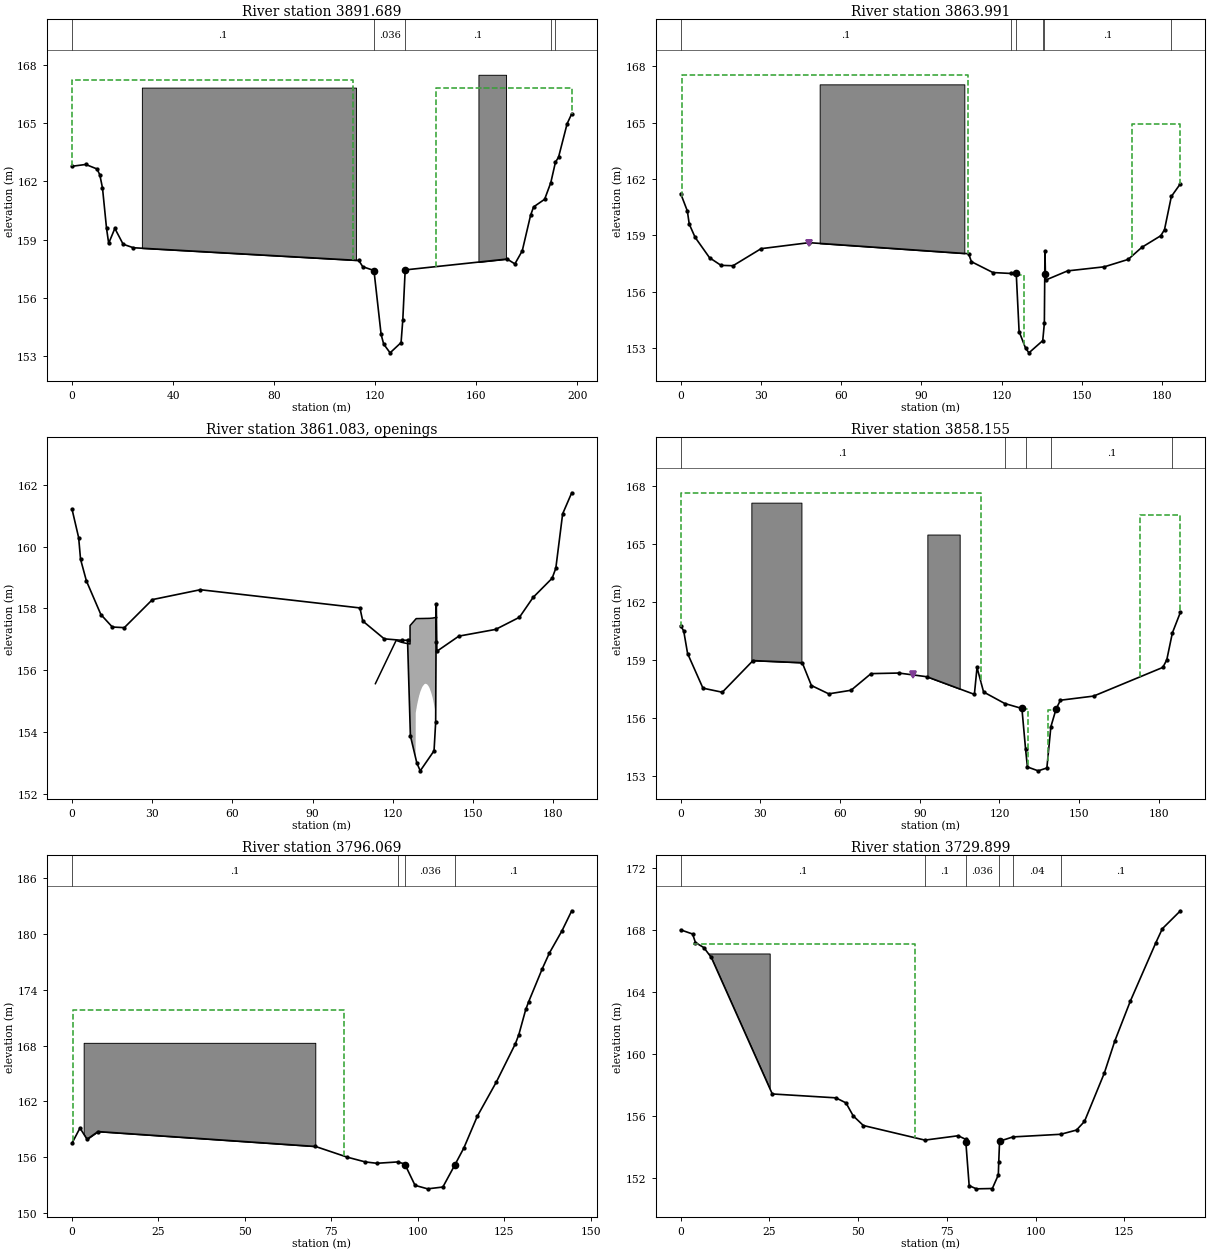
Type RM Length L Ch R = 1 ,3891.689,28.338,27.698,27.058
XS GIS Cut Line= 4
528872.2822944674777221.58059951528967.2564944674777179.04009951
529013.1648074854777143.83698486529045.4122944674777128.09039951
#Sta/Elev= 30
       0 162.782    5.45 162.876   9.911 162.645  11.015 162.346  12.084 161.666
  13.685 159.584  14.531  158.82  16.972 159.586  20.259 158.771  24.316 158.591
 113.536 157.936 115.089 157.615  119.53  157.42 122.358 154.132  123.37 153.636
 125.907 153.184 130.257 153.711 130.947 154.891 131.886 157.451 172.239  158.01
 175.301  157.76 178.221 158.432 181.512 160.259 182.707 160.692 187.076 161.084
 189.517 161.939 191.377 163.002  192.57 163.242 195.979 164.971 197.805 165.484
#Mann= 5 ,-1 , 0
       0      .1       0  119.53    .036       0 131.886      .1       0
 189.517      .1       0 191.377     .08       0
#XS Ineff= 2 , 0
          111.19  167.21  143.96          166.81
Permanent Ineff=
       T       T
#Block Obstruct= 2 ,-1
   27.67  112.42  166.83  160.88  171.81  167.49
Bank Sta=119.53,131.886
XS Rating Curve= 0 ,0
Exp/Cntr=0.5,0.3

Type RM Length L Ch R = 1 ,3863.991,6.359,5.836,5.314
XS GIS Cut Line= 4
 528894.61102716 4777257.8753192528987.7197072144777203.18986471
529017.5347672494777170.70592722529049.9333663754777157.95457868
#Sta/Elev= 30
       0 161.223   2.505 160.291    3.21 159.593   5.402  158.89  10.808 157.801
   15.09 157.396  19.577 157.376  30.081 158.285  48.002 158.605 107.688 158.015
 108.725 157.592 116.776 157.013 123.498 156.964  125.49 156.969 126.561 153.871
 128.964  152.99 130.239 152.735 135.402 153.385 136.007  154.31 136.155 156.911
 136.224 158.141 136.459  156.61 144.679 157.101  158.44 157.319 167.336 157.712
 172.439 158.355 179.552 158.976 180.937 159.301 183.492 161.065  186.89 161.747
#Mann= 6 ,-1 , 0
       0      .1       0 123.498      .1       0  125.49    .036       0
 135.402      .1       0 136.007      .1       0 183.492      .1       0
Levee=-1,48.11,158.61,0,,,Levee 24,
#XS Ineff= 3 ,-1
     .53  107.49  167.55  125.49  128.57  156.86  168.81  188.02  164.91
Permanent Ineff=
       T       T       T
#Block Obstruct= 1 ,-1
   51.98  106.08  167.04
Bank Sta=125.49,136.155
XS Rating Curve= 0 ,0
Exp/Cntr=0.5,0.3

Type RM Length L Ch R = 4 ,3861.083,,,
BEGIN DESCRIPTION:
E135
END DESCRIPTION:
Bridge Culvert--1,0,-1,-1, 0
Deck Dist Width WeirC Skew NumUp NumDn MinLoCord MaxHiCord MaxSubmerge Is_Ogee
0.01,5.64,1.44,0, 29, 29, , , 0.95, 0, ,,,
 113.465 113.479 121.223 123.214 124.723 126.417 126.423 127.649   128.5 128.569
 128.716 129.109 129.795 130.268 131.012 131.766 132.175 132.397 132.861 133.292
 133.647 133.731 134.414 134.845 134.847 135.208 135.671   135.9 136.402
  155.56 155.563 156.962 156.901 156.872 156.847 157.442 157.563 157.648 157.655
 157.669  157.67 157.671 157.672 157.673 157.674 157.675 157.676 157.676 157.677
 157.678 157.678 157.683 157.686 157.686 157.692   157.7 157.704 157.704
  155.56 114.464  114.42 114.409 114.401 114.391 114.391 114.385  114.38 154.626
 154.698 154.891 155.157 155.298 155.457 155.542 155.556 155.556 155.533 155.487
 155.429 155.415  155.25 155.112 155.111 154.973 154.764 154.647 154.626
 115.643 115.657  124.48 126.901 128.595 128.601 129.827 130.678 130.747 130.894
 131.287 131.973 132.446  133.19 133.944 134.353 134.575 135.039  135.47 135.825
 135.909 136.592 137.023 137.025 137.386 137.849 138.078 138.225  142.32
  155.56 155.563 156.778 156.872 156.847 157.442 157.563 157.648 157.655 157.669
  157.67 157.671 157.672 157.673 157.674 157.675 157.676 157.676 157.677 157.678
 157.678 157.683 157.686 157.686 157.692   157.7 157.704   156.8  156.84
  155.56 114.464  114.42 114.401 114.391 114.391 114.385  114.38 154.626 154.698
 154.891 155.157 155.298 155.457 155.542 155.556 155.556 155.533 155.487 155.429
 155.415  155.25 155.112 155.111 154.973 154.764 154.647 114.301 114.319
BR Coef=-1 , 0 , 0 ,, 0 ,,,0.8,0,,0,
WSPro=,,,, 1 ,,,, 0 ,,,, 0 ,,,,-1 ,-1 ,-1 , 0 , 0 , 0 , 0 , 0
BC Mult= 1 ,0,125.5,0,126
BC Mult= 3 ,125.5,136.5,126,143
BC Mult= 1 ,136.5,200,143,200
BC Design=,, 0 ,, 0 ,,,,,,
BC Use User HTab Curves=0
BC User HTab FreeFlow(D)= 0

Type RM Length L Ch R = 1 ,3858.155,58.444,62.086,65.729
XS GIS Cut Line= 4
528899.2290250894777265.66439205528993.6088903074777210.77983867
529019.7497889974777172.61687225529050.3263897554777161.08316613
#Sta/Elev= 30
       0 160.782   1.145 160.516   2.608 159.346   8.389 157.555  15.671 157.344
  27.233 158.981  45.763 158.871  49.212 157.692  55.745 157.261  64.127 157.446
  71.659 158.307  82.126 158.337  92.657 158.146 110.559 157.234 111.553 158.625
 114.018 157.357 122.011  156.76 128.448 156.505 129.825 154.401 130.523  153.48
 134.572 153.279 137.842 153.427  139.35  155.56 141.317 156.479 142.946 156.931
 155.436 157.145 181.482 158.628 182.971 159.016 185.086 160.414 188.115 161.482
#Mann= 5 ,-1 , 0
       0      .1       0 122.011      .1       0 129.825    .036       0
  139.35      .1       0 185.086      .1       0
Levee=-1,87.4,158.31,0,,,Levee 24,
#XS Ineff= 4 ,-1
     .18  113.13  167.66  128.45  130.75   156.5  138.08     141   156.4
  173.04  189.96  166.49
Permanent Ineff=
       T       T       T       T
#Block Obstruct= 2 ,-1
   26.61   45.46  167.15   92.86  105.02   165.5
Bank Sta=128.448,141.317
XS Rating Curve= 0 ,0
Exp/Cntr=0.5,0.3

Type RM Length L Ch R = 1 ,3796.069,64.543,66.169,67.796
XS GIS Cut Line= 3
528936.6153566254777261.22623324528991.0276566254777239.95603324
 529077.061078274777241.61214259
#Sta/Elev= 26
       0 157.462   2.315 159.108   4.355 157.898    7.52 158.725  70.395 157.121
  79.558  155.97  84.792 155.454  88.126 155.308  94.123 155.452  96.173 155.241
  96.293 155.156  99.173 152.931 102.808 152.554 107.215 152.748  110.71  155.15
   113.3 156.969 117.176 160.379 122.694 164.078 128.178 168.189 129.179 169.176
 131.179 171.886 132.045 172.742 135.969 176.286 138.027 177.978  141.66 180.367
 144.471  182.52
#Mann= 4 ,-1 , 0
       0      .1       0  94.123      .1       0  96.293    .036       0
  110.71      .1       0
#XS Ineff= 1 ,-1
     .42   78.52  171.79
Permanent Ineff=
       T
#Block Obstruct= 1 ,-1
    3.38   70.34  168.29
Bank Sta=96.293,110.71
XS Rating Curve= 0 ,0
Exp/Cntr=0.5,0.3

Type RM Length L Ch R = 1 ,3729.899,6.045,6.045,6.045
XS GIS Cut Line= 3
528941.5619589724777273.59269966528998.773776361 4777292.3643881
 529070.984956584777328.20444603
#Sta/Elev= 30
       0     168   3.362 167.733   4.166 167.183   6.518 166.861   8.639 166.222
  25.816 157.439  43.743 157.189  46.582 156.864  48.633 156.026  51.477 155.409
  68.823 154.469  78.197  154.75  80.305  154.52   80.35  154.37  81.299 151.537
  83.328 151.333  87.827 151.354  89.515 152.229  89.635 153.073  89.868   154.4
  93.651 154.675   107.1 154.844 111.544 155.116 113.797 155.673 119.363  158.77
 122.343 160.851 126.686   163.4 133.915  167.18 135.733 168.074 140.829 169.228
#Mann= 6 ,-1 , 0
       0      .1       0  68.823      .1       0  80.305    .036       0
  89.635      .1       0  93.651     .04       0   107.1      .1       0
#XS Ineff= 1 ,-1
    3.38   66.11  167.07
Permanent Ineff=
       T
#Block Obstruct= 1 ,-1
    4.79   25.09  166.48
Bank Sta=80.35,89.868
XS Rating Curve= 0 ,0
Exp/Cntr=0.5,0.3

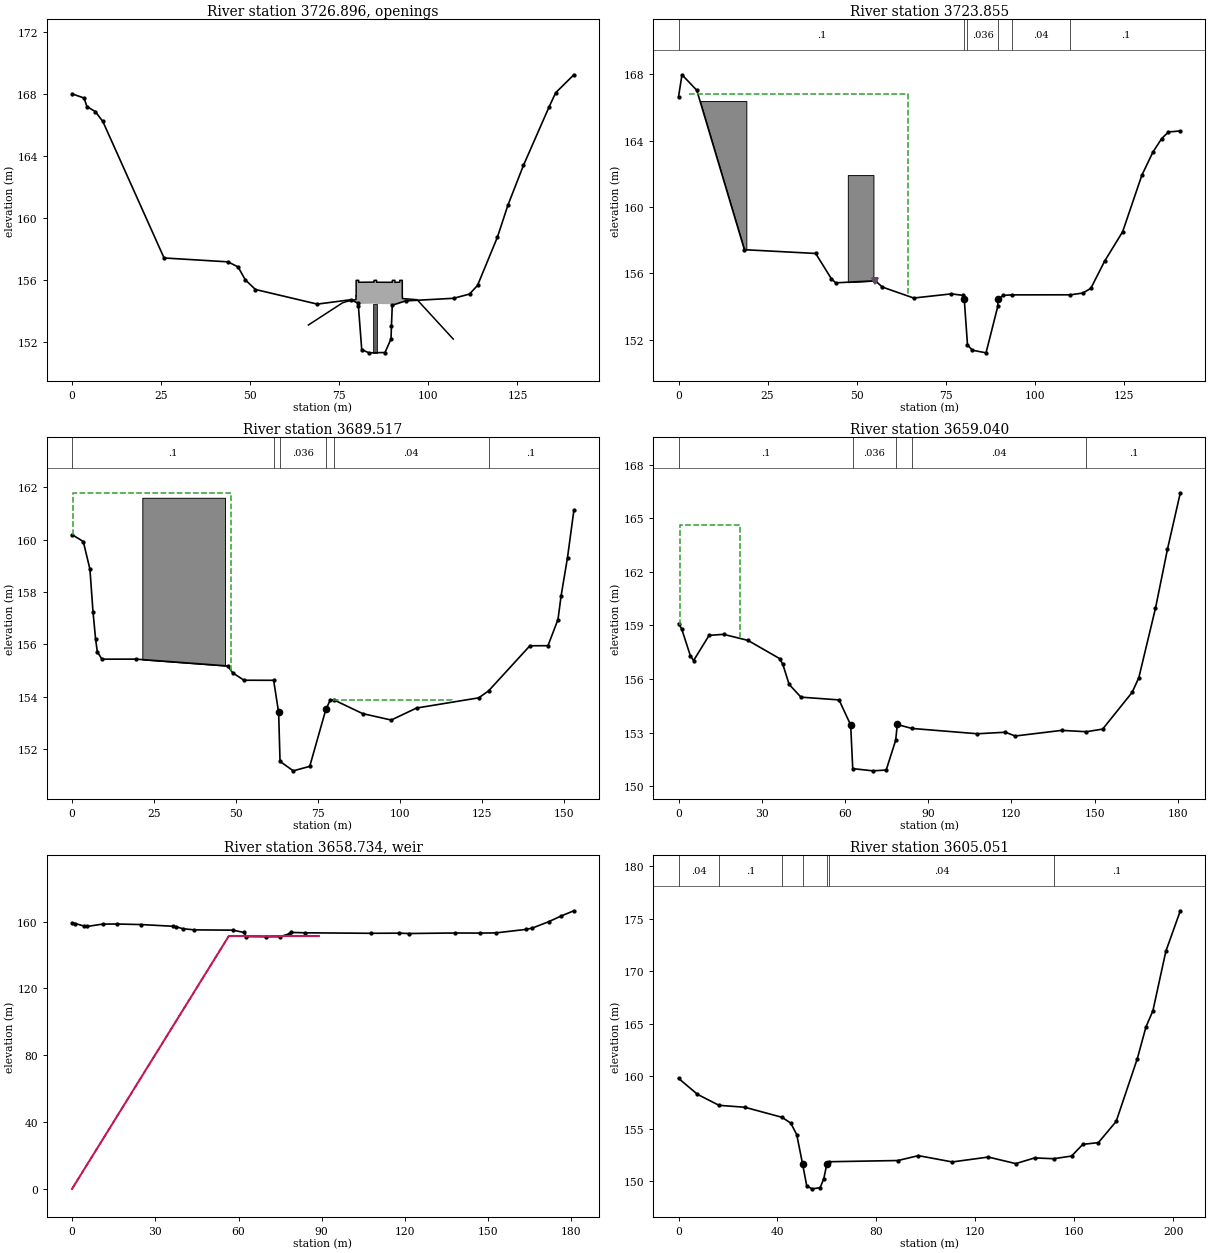
Type RM Length L Ch R = 4 ,3726.896,,,
BEGIN DESCRIPTION:
E136
END DESCRIPTION:
Bridge Culvert--1,0,-1,-1, 0
Deck Dist Width WeirC Skew NumUp NumDn MinLoCord MaxHiCord MaxSubmerge Is_Ogee
0.01,5.84,1.44,0, 37, 37, , , 0.95, 0, ,,,
  66.317  66.472  75.893  77.002  78.691  79.675  79.677  79.725  79.728  80.207
  80.326  80.435  80.436  84.624  84.748   84.75  85.404  85.458  85.459  89.873
  89.892  89.893   89.93  90.602  90.603  91.967   91.97  92.677  92.682   92.72
  92.721  93.545  94.785  96.517  96.831 106.902 106.983
 153.123 153.146  154.55 154.632  154.72 154.759 154.988 154.988 155.999     156
 156.001 156.001 155.874 155.885 155.885 155.999 156.001 156.001 155.877 155.873
 155.873 155.999 155.999 156.001 155.871 155.878 155.999 156.001 154.944 154.944
 154.828 154.813 154.791 154.759 154.754 152.238 152.218
 153.123 117.997 117.898 117.886 117.868 117.858 117.858 117.857 117.857 117.852
 154.475 154.476 154.476 154.502 154.499 154.499 154.481 154.481 154.481 154.458
 141.847 141.334 117.609 117.607 117.607 117.604 117.604 117.602 117.602 117.602
 117.602   117.6 117.597 117.592 117.592 117.566 152.218
  66.095   66.25  75.671   76.78  78.469  79.453  79.455  79.503  79.506  79.985
  80.104  80.213  80.214  84.402  84.526  84.528  85.182  85.236  85.237  89.651
   89.67  89.671  89.708   90.38  90.381  91.745  91.748  92.455   92.46  92.498
  92.499  93.323  94.563  96.295  96.609  106.68 106.761
 153.123 153.146  154.55 154.632  154.72 154.759 154.988 154.988 155.999     156
 156.001 156.001 155.874 155.885 155.885 155.999 156.001 156.001 155.877 155.873
 155.873 155.999 155.999 156.001 155.871 155.878 155.999 156.001 154.944 154.944
 154.828 154.813 154.791 154.759 154.754 152.238 152.218
 153.123 117.997 117.898 117.886 117.868 117.858 117.858 117.857 117.857 117.852
 154.475 154.476 154.476 154.502 154.499 154.499 154.481 154.481 154.481 154.458
 141.847 141.334 117.609 117.607 117.607 117.604 117.604 117.602 117.602 117.602
 117.602   117.6 117.597 117.592 117.592 117.566 152.218
Pier Skew, UpSta & Num, DnSta & Num=  ,85.02, 5 ,84.8, 5 , 0 , 0 , 0 ,,
    1.26    1.26   1.014     .78     .78
     150  152.73  152.73 154.493   155.5
    1.26    1.26   1.014     .78     .78
     150  152.73  152.73 154.493   155.5
BR Coef=-1 , 1 , 0 ,, 0 ,,,0.8,-1,1.6,0,
WSPro=,,,, 1 ,,,, 0 ,,,, 0 ,,,,-1 ,-1 ,-1 , 0 , 0 , 0 , 0 , 0
BC Mult= 1 ,0,79,0,79
BC Mult= 3 ,79,92,79,93
BC Mult= 1 ,92,150,93,150
BC Design=,, 0 ,, 0 ,,,,,,
BC Use User HTab Curves=0
BC User HTab FreeFlow(D)= 0

Type RM Length L Ch R = 1 ,3723.855,34.15,34.338,34.526
XS GIS Cut Line= 3
528938.8513493214777278.99415353528996.0631667094777297.76584196
529068.274346929 4777333.6058999
#Sta/Elev= 30
       0 166.655    .968 167.975   5.126 167.042  18.489 157.434  38.487 157.207
  42.927 155.673  44.119 155.437  55.252 155.559   57.18 155.183  66.003 154.521
  76.577 154.772  79.791 154.682  80.188 154.456  81.098 151.696  82.426 151.378
  86.299 151.218  89.593 154.016  89.648 154.455  91.201 154.681  93.496 154.711
 110.002 154.715 113.474 154.822 115.707 155.104 119.589 156.745 124.638 158.515
 130.035 161.924 133.149  163.32 135.601 164.132 137.496 164.529 140.829 164.591
#Mann= 6 ,-1 , 0
       0      .1       0  80.188      .1       0  81.098    .036       0
  89.593      .1       0  93.496     .04       0 110.002      .1       0
Levee=-1,55.12,155.57,0,,,Levee 25,
#XS Ineff= 1 ,-1
    2.82   64.42   166.8
Permanent Ineff=
       T
#Block Obstruct= 2 ,-1
    2.54   19.03  166.39   47.51    54.7  161.93
Bank Sta=80.188,89.648
XS Rating Curve= 0 ,0
Exp/Cntr=0.5,0.3

Type RM Length L Ch R = 1 ,3689.517,30.829,30.477,30.125
XS GIS Cut Line= 4
528938.5663944674777311.60819951528983.3678034344777328.54319624
529023.6473944674777351.18079951529081.5222944674777362.55789951
#Sta/Elev= 30
       0  160.19   3.427 159.929   5.452 158.869   6.391  157.24    7.17  156.21
   7.703 155.716   9.118 155.436  19.462 155.438  47.509 155.177  48.998 154.913
  52.459 154.632  61.494 154.629   63.02   153.4  63.445 151.533  67.472 151.172
  72.506 151.343  77.444 153.524  78.712 153.859  79.925 153.878  88.655 153.357
  97.371 153.112 105.091  153.57 124.078  153.96  127.09 154.228 139.662 155.947
 145.184 155.951 148.241 156.951 149.177 157.845 151.144 159.317 153.083 161.115
#Mann= 6 ,-1 , 0
       0      .1       0  61.494      .1       0  63.445    .036       0
  77.444      .1       0  79.925     .04       0  127.09      .1       0
#XS Ineff= 2 ,-1
     .14   48.63  161.79   79.65  116.02  153.86
Permanent Ineff=
       T       T
#Block Obstruct= 1 ,-1
   21.43   46.66   161.6
Bank Sta=63.02,77.444
XS Rating Curve= 0 ,0
Exp/Cntr=0.3,0.1

Type RM Length L Ch R = 1 ,3659.040,54.492,53.989,53.486
XS GIS Cut Line= 4
  528926.03977484777332.95657545528973.2295996634777359.58434053
529005.1234127774777373.68867318529096.6964850834777380.44366005
#Sta/Elev= 30
       0 159.101   1.132 158.804   4.284 157.294   5.432 157.036  11.018 158.444
  16.222 158.501  24.998 158.164  36.434 157.145  37.582 156.827  39.878 155.699
  44.125 154.988  57.865 154.833   62.05  153.43  62.796  150.99  70.084 150.866
  74.854 150.911  78.274 152.577  78.856 153.458   84.09 153.238 107.755  152.94
 117.783 153.025 121.367 152.815 138.109 153.129     147 153.054 152.878   153.2
 163.511 155.255 165.913 156.074 171.929 159.965 176.249 163.267 180.879 166.419
#Mann= 5 ,-1 , 0
       0      .1       0  62.796    .036       0  78.274      .1       0
   84.09     .04       0     147      .1       0
#XS Ineff= 2 ,-1
     .35   22.03  164.64    79.3  181.67  153.43
Permanent Ineff=
       T       T
Bank Sta=62.05,78.856
XS Rating Curve= 0 ,0
Exp/Cntr=0.3,0.1

Type RM Length L Ch R = 5 ,3658.734,,,
BEGIN DESCRIPTION:
E137
END DESCRIPTION:
IW Pilot Flow=0
#Inline Weir SE= 11
       0       0    56.5  151.29    61.9  151.29   67.75   151.3   68.39  151.21
   73.18  151.27    73.2  151.31   73.69  151.28    73.7  151.28   78.96   151.3
   88.96   151.3
IW Dist,WD,Coef,Skew,MaxSub,Min_El,Is_Ogee,SpillHt,DesHd
0.1,0.8,1.7,0,0.98,, 0 ,,,0,0,

Type RM Length L Ch R = 1 ,3605.051,36.169,34.543,32.917
XS GIS Cut Line= 3
528922.3388332654777403.38783938528997.3372196054777424.98047328
529121.5894944674777413.01289951
#Sta/Elev= 30
       0 159.788   7.665 158.265  16.372 157.221   26.81 157.038  41.832  156.08
  45.349 155.533  47.776 154.443   50.19  151.59  51.851  149.53  54.061 149.273
  57.254 149.385  58.716 150.234  59.972 151.641  60.922 151.853  88.708 151.968
  96.975 152.433 110.659 151.833 125.239 152.297 136.332 151.674 143.986 152.216
 151.667  152.14 158.909 152.394 163.448 153.508  169.75 153.671 176.934 155.689
 185.492 161.669 188.989 164.688 191.785 166.221 197.026 171.889 202.871 175.736
#Mann= 7 ,-1 , 0
       0     .04       0  16.372      .1       0  41.832      .1       0
   50.19    .036       0  59.972      .1       0  60.922     .04       0
 151.667      .1       0
Bank Sta=50.19,59.972
XS Rating Curve= 0 ,0
Exp/Cntr=0.3,0.1

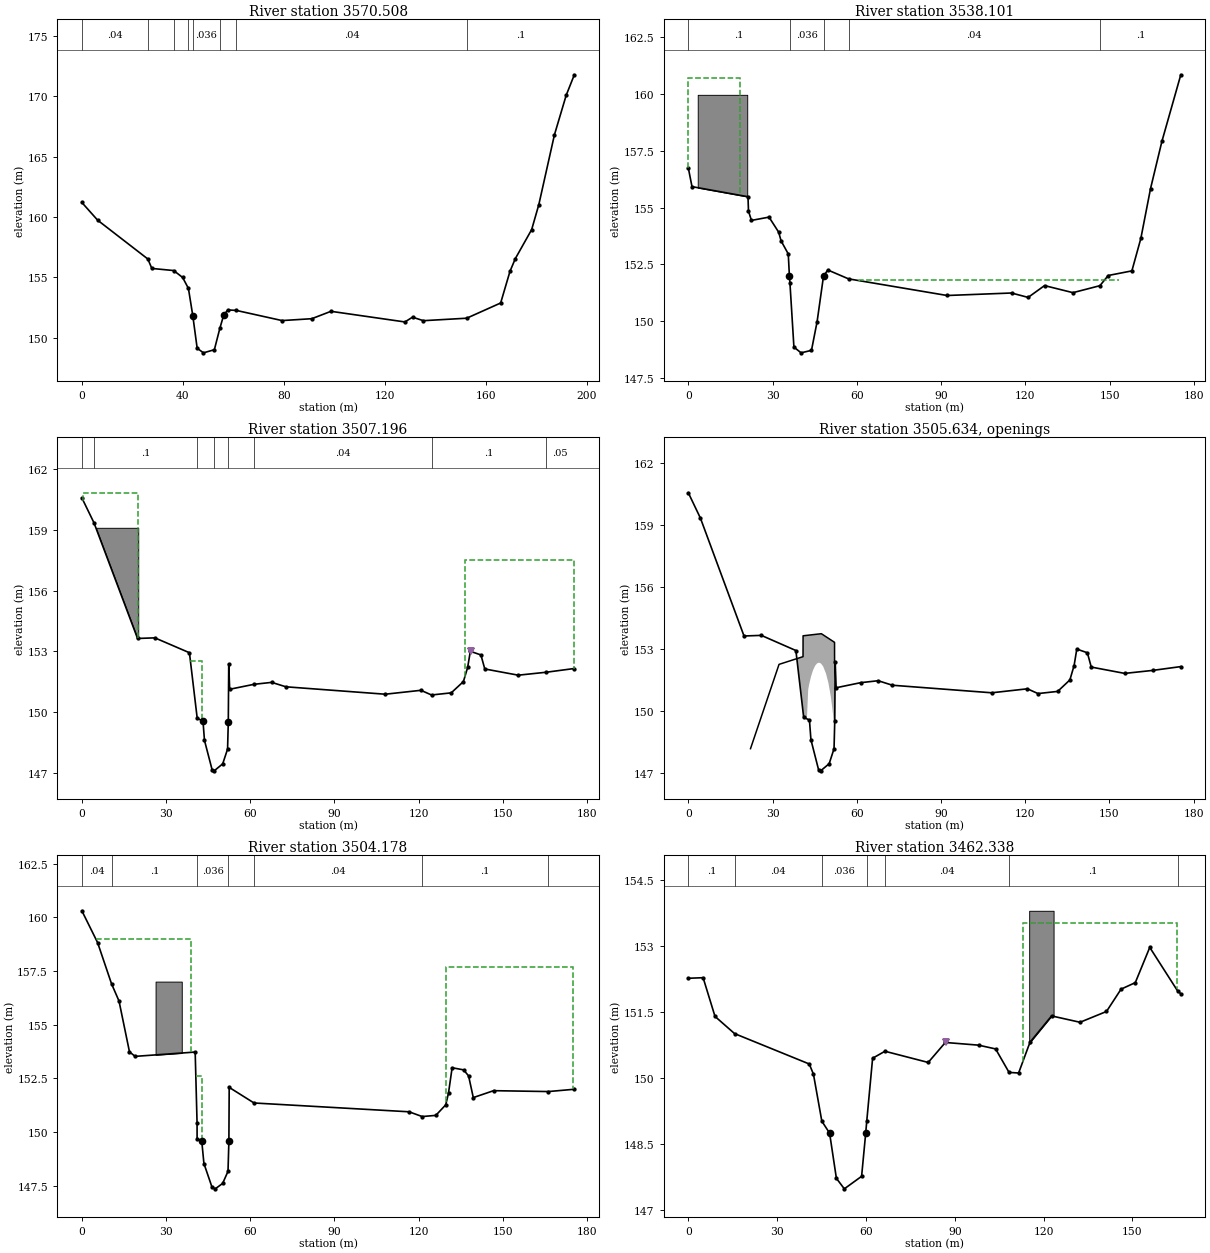
Type RM Length L Ch R = 1 ,3570.508,33.039,32.406,31.774
XS GIS Cut Line= 3
528924.2213400894777460.49997581529034.5123310034777442.53465838
 529117.632278414777437.74574777
#Sta/Elev= 30
       0 161.192   6.276 159.719   26.13 156.507  27.711 155.725  36.368  155.55
  39.903 154.977  42.199  154.07  43.919 151.819  45.662 149.111  48.147  148.73
  52.472 148.989  54.652 150.771  56.185 151.866  57.779 152.285  61.133 152.247
  79.285 151.404   91.04 151.559  98.643 152.171  127.92  151.29  130.93 151.686
 135.229 151.395 152.375   151.6 165.832 152.861 169.529  155.49 171.655 156.545
 178.114 158.947 180.945 161.018 187.128 166.803 191.781 170.077 195.002 171.776
#Mann= 8 ,-1 , 0
       0     .04       0   26.13      .1       0  36.368     .04       0
  42.199      .1       0  43.919    .036       0  54.652      .1       0
  61.133     .04       0 152.375      .1       0
#XS Ineff= 1 ,-1
   60.97   99.74     152
Permanent Ineff=
       T
Bank Sta=43.919,56.185
XS Rating Curve= 0 ,0
Exp/Cntr=0.3,0.1

Type RM Length L Ch R = 1 ,3538.101,31.438,30.905,30.373
XS GIS Cut Line= 3
528941.5342944674777497.59929951529010.4350615764777473.71012753
529111.2016944674777455.55339951
#Sta/Elev= 30
       0 156.745   1.309  155.92  21.241 155.475  21.419  154.84  22.477 154.431
  28.725 154.576  32.178  153.91   33.01 153.532  35.583 152.951   35.99  151.96
  36.185 151.657  37.591 148.844  40.141  148.59  43.846   148.7   45.85 149.968
  48.133 151.979  49.666 152.244   57.03 151.853  92.118 151.119 115.049 151.229
 120.966 151.035 126.811 151.556 136.925 151.244 146.528 151.552 149.474 152.001
 157.903 152.205 161.092 153.634 164.537 155.831 168.598  157.92 175.315 160.854
#Mann= 5 ,-1 , 0
       0      .1       0  36.185    .036       0  48.133      .1       0
   57.03     .04       0 146.528      .1       0
#XS Ineff= 2 ,-1
       0    18.5  160.71   60.79  153.48  151.81
Permanent Ineff=
       T       T
#Block Obstruct= 1 ,-1
    3.35   20.97  159.97
Bank Sta=35.99,48.133
XS Rating Curve= 0 ,0
Exp/Cntr=0.5,0.3

Type RM Length L Ch R = 1 ,3507.196,3.018,3.018,3.018
XS GIS Cut Line= 4
528954.0238451244777531.83940923528982.5225673084777517.58912654
529014.8231287674777500.79734381529120.1055640664777480.78091819
#Sta/Elev= 30
       0 160.579   4.316 159.349  19.842 153.634  26.006 153.664  38.323 152.929
  41.099 149.685   43.15  149.56  43.679 148.602  46.415 147.142   47.14 147.095
  50.176 147.441  51.911 148.171   52.17  149.53  52.323 152.379  52.656 151.124
  61.368  151.37  67.634 151.465    72.7 151.246 108.082  150.88 120.794 151.073
  124.56 150.842 131.582 150.947 135.925 151.504 137.433 152.203 138.391     153
 142.161  152.82  143.54 152.127  155.46  151.82 165.419 151.965 175.437  152.15
#Mann= 8 ,-1 , 0
       0     .04       0   4.316      .1       0  41.099    .036       0
   47.14      .1       0   52.17      .1       0  61.368     .04       0
  124.56      .1       0 165.419     .05       0
Levee=0,,,-1,138.5,153.02,,Levee 26
#XS Ineff= 3 ,-1
     .53   20.09  160.83   38.66   42.71   152.5  136.39  177.97   157.5
Permanent Ineff=
       T       T       T
#Block Obstruct= 1 ,-1
    3.35   20.09   159.1
Bank Sta=43.15,52.17
XS Rating Curve= 0 ,0
Exp/Cntr=0.5,0.3

Type RM Length L Ch R = 4 ,3505.634,,,
BEGIN DESCRIPTION:
E138
END DESCRIPTION:
Bridge Culvert--1,0,-1,-1, 0
Deck Dist Width WeirC Skew NumUp NumDn MinLoCord MaxHiCord MaxSubmerge Is_Ogee
0.01,2.82,1.44,0, 29, 33, , , 0.95, 0, ,,,
  22.153  22.515  32.317  40.864   40.88  42.245  42.707  43.101  43.718  44.411
  44.781  45.155   45.77  46.275   46.84   46.84  47.321  47.398  48.028  49.059
  49.745  49.912  50.813  51.511  51.883  52.092    52.1  52.478   52.61
  148.17 148.316 152.258 152.632 153.644 153.665 153.672 153.679 153.688 153.699
 153.705  153.71  153.72 153.728 153.736 153.736 153.744 153.745 153.689 153.597
 153.536 153.521 153.441 153.379 153.346 153.327 152.382 152.338  152.38
  148.17 107.191 107.236 107.276 107.276 107.282 151.039 151.318 151.672 151.969
 152.077 152.186 152.292 152.333 152.331 152.331 152.289 152.275 152.159 151.809
 151.442 151.353 150.656 149.889  149.35 148.984 148.093 107.109 107.074
   22.31  22.672  32.474  41.021  41.037  42.402  42.864  43.258  43.875  44.568
  44.938  45.312  45.927  46.432  46.997  46.997  47.478  47.555  48.185  49.216
  49.902  50.069   50.97  51.668   52.04  52.249  52.257  52.635  55.384   60.46
  61.083  73.349  73.692
  148.17 148.316 152.258 152.632 153.644 153.665 153.672 153.679 153.688 153.699
 153.705  153.71  153.72 153.728 153.736 153.736 153.744 153.745 153.689 153.597
 153.536 153.521 153.441 153.379 153.346 153.327 152.382 152.338 152.015  151.43
  151.36 148.317 148.232
  148.17 107.191 107.236 107.276 107.276 107.282 151.039 151.318 151.672 151.969
 152.077 152.186 152.292 152.333 152.331 152.331 152.289 152.275 152.159 151.809
 151.442 151.353 150.656 149.889  149.35 148.984 148.093 107.109 107.074 107.011
 107.003 106.849 148.232
BR Coef=-1 , 0 , 0 ,, 0 ,,,0.8,-1,,0,
WSPro=,,,, 1 ,,,, 0 ,,,, 0 ,,,,-1 ,-1 ,-1 , 0 , 0 , 0 , 0 , 0
BC Mult= 1 ,0,38,0,40.6
BC Mult= 3 ,38,52.5,40.6,57.8
BC Mult= 1 ,52.5,200,57.8,180
BC Design=,, 0 ,, 0 ,,,,,,
BC Use User HTab Curves=0
BC User HTab FreeFlow(D)= 0

Type RM Length L Ch R = 1 ,3504.178,43.044,41.84,40.635
XS GIS Cut Line= 4
 528955.697547434777534.32824655528984.1962696144777520.07796387
529016.4968310734777503.28618114529121.7792663734777483.26975552
#Sta/Elev= 30
       0 160.307   5.605 158.827  10.579 156.906  13.238 156.106  16.964  153.74
  18.977 153.529   40.37  153.73  41.041 150.432  41.055 149.699  42.706 149.592
  43.486 148.541  46.383 147.432  47.508 147.362  50.154 147.614  52.067 148.179
   52.38  149.59   52.49 152.085  61.332 151.359 116.566 150.949 121.243 150.727
 126.093 150.782 129.621 151.272 130.616 151.825 131.901     153  135.97 152.901
 137.764 152.623 139.443  151.61 146.678 151.932 166.172 151.891 175.435 151.998
#Mann= 7 ,-1 , 0
       0     .04       0  10.579      .1       0  41.055    .036       0
  52.067      .1       0  61.332     .04       0 121.243      .1       0
 166.172     .05       0
#XS Ineff= 3 ,-1
    4.93   38.94  158.99    40.6   42.86   152.6  129.87  174.98  157.71
Permanent Ineff=
       T       T       T
#Block Obstruct= 1 ,-1
   26.26   35.59  157.01
Bank Sta=42.706,52.38
XS Rating Curve= 0 ,0
Exp/Cntr=0.5,0.3

Type RM Length L Ch R = 1 ,3462.338,36.828,36.598,36.368
XS GIS Cut Line= 3
528989.4915085584777582.12791793529052.2115168364777516.82110216
529124.0627944674777492.65269951
#Sta/Elev= 30
       0 152.273   4.997 152.286   9.017 151.404  15.621 151.013  40.855 150.321
   42.27 150.088  45.099 149.019  47.725 148.746  50.019 147.717  52.699 147.478
  58.536 147.763   59.91  148.74  60.294 149.034  62.252 150.452  66.425 150.611
  81.028 150.356  86.826 150.811  98.048  150.75 103.798 150.664 108.346 150.129
 111.572 150.116 115.404 150.815 122.711 151.416  132.32 151.271 141.256 151.517
 146.176 152.025 150.988 152.174 155.869 152.976 165.256 151.987 166.354  151.92
#Mann= 7 ,-1 , 0
       0      .1       0  15.621     .04       0  45.099    .036       0
  60.294      .1       0  66.425     .04       0 108.346      .1       0
 165.256     .05       0
Levee=0,,,-1,86.91,150.83,,Levee 27
#XS Ineff= 1 ,-1
  112.92  164.93  153.54
Permanent Ineff=
       T
#Block Obstruct= 1 ,-1
  115.14  123.38  153.81
Bank Sta=47.725,59.91
XS Rating Curve= 0 ,0
Exp/Cntr=0.3,0.1