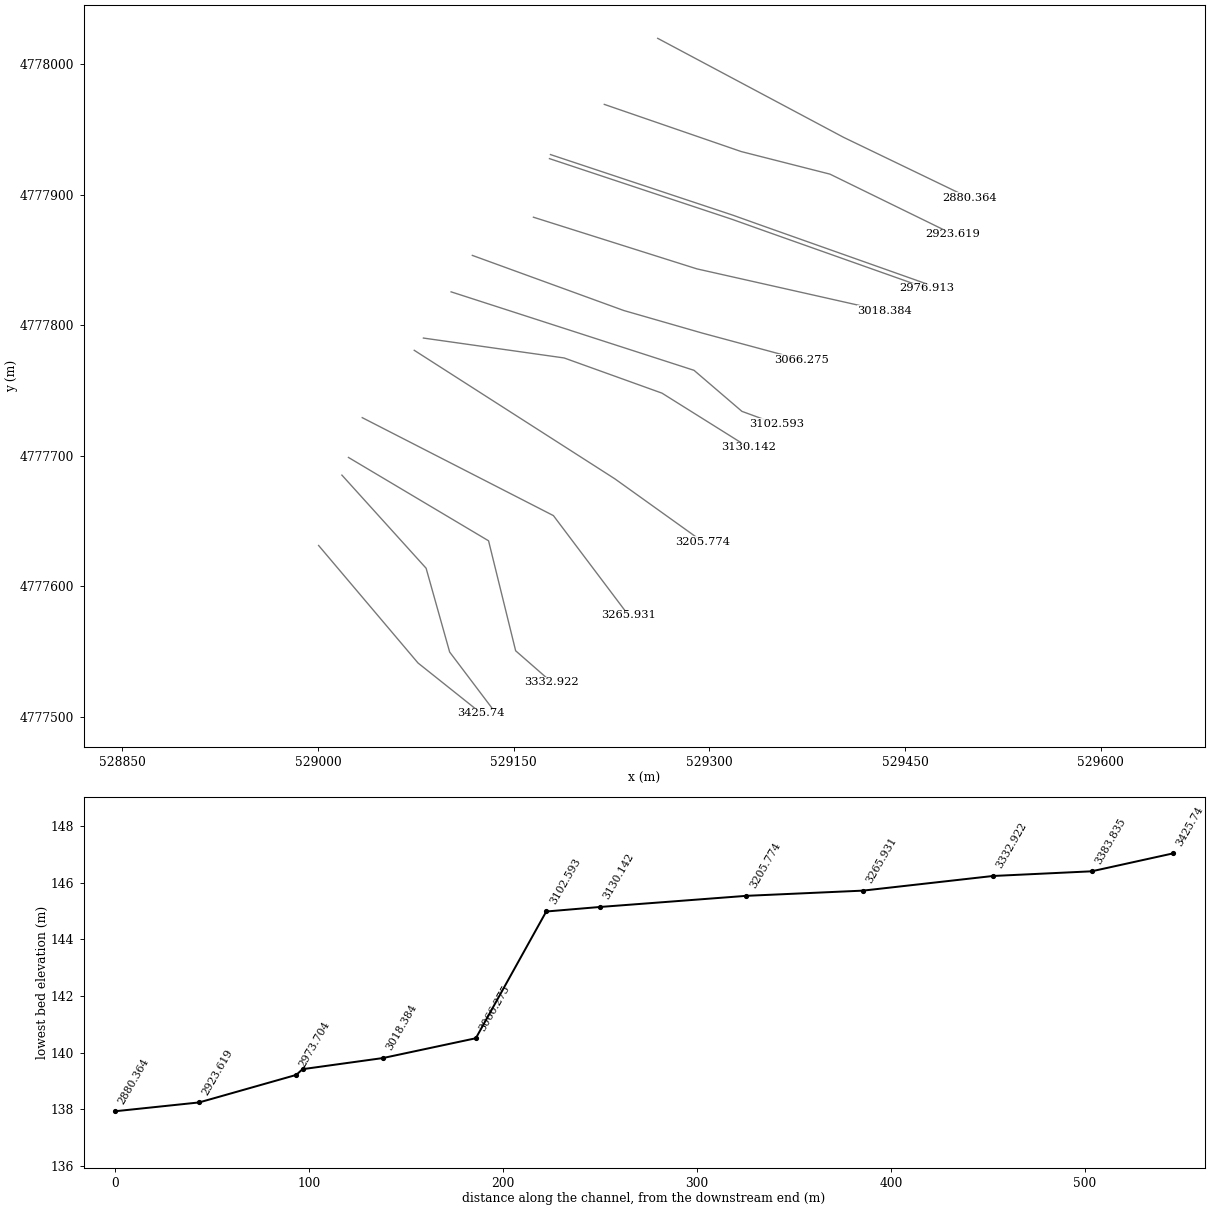
HEC-RAS study Durango.prj: Durango

--- Durango.g18 (geometry) --- (continued)

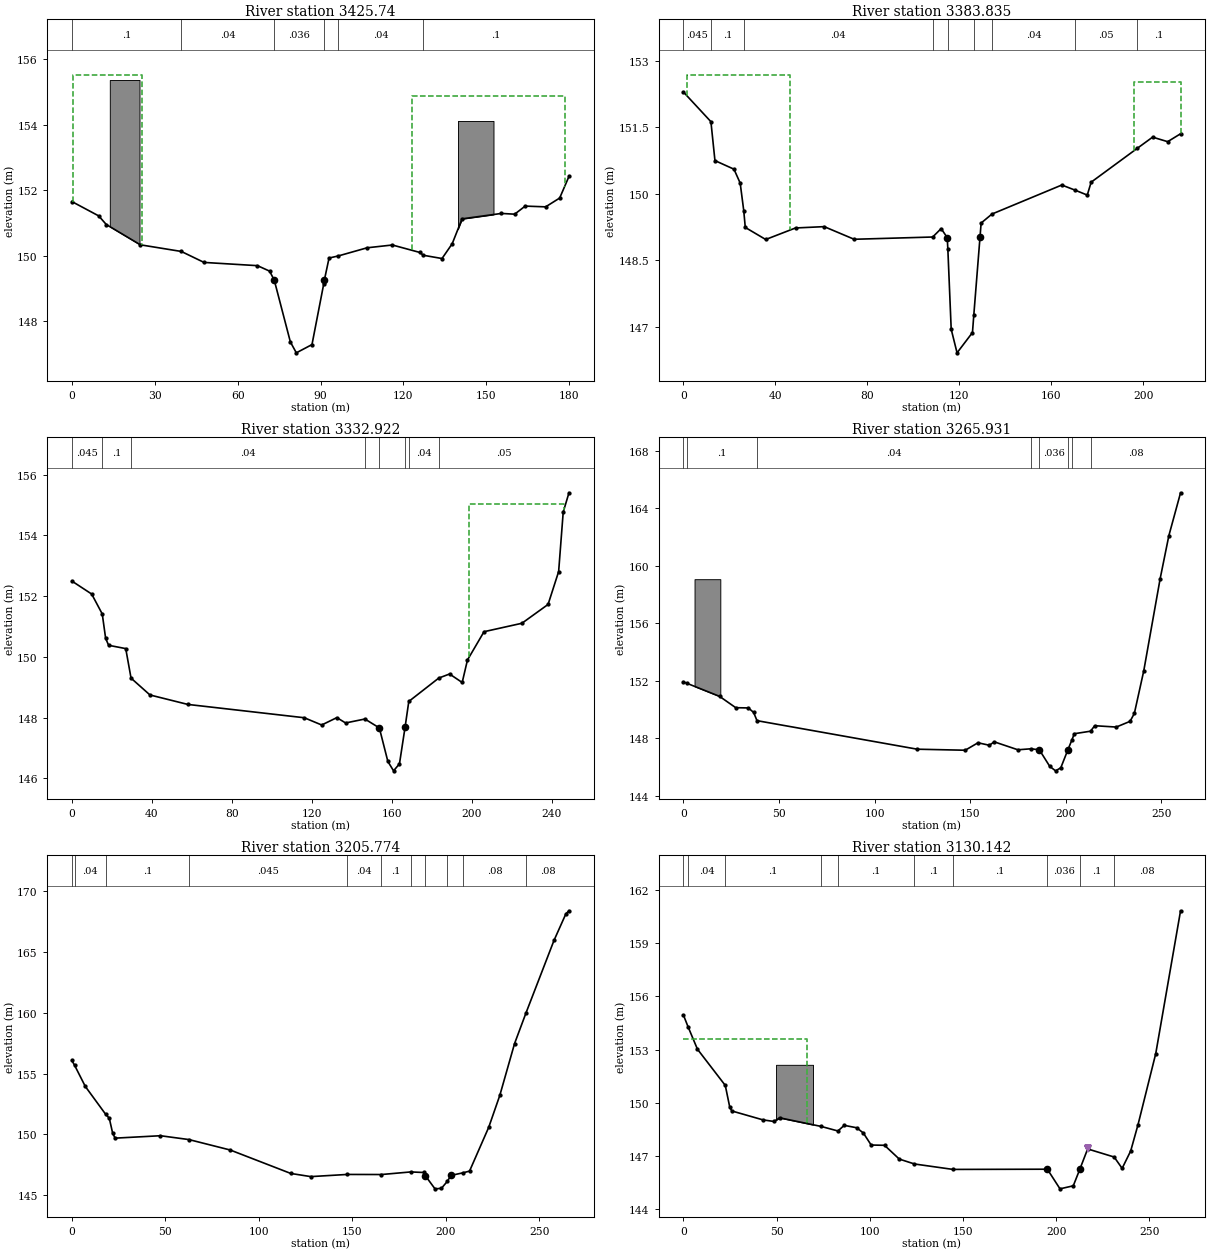
Type RM Length L Ch R = 1 ,3425.74 ,43.481,41.904,40.328
XS GIS Cut Line= 3
529000.355604057 4777631.1562695529076.575736516 4777541.1290882
529125.0521353794777502.54583197
#Sta/Elev= 29
       0 151.659   9.722 151.221  12.467 150.958  24.784 150.338  39.617 150.135
  47.844   149.8   67.19 149.701  71.574 149.534  73.261 149.258  79.089 147.372
  81.241 147.039  86.912 147.291  91.143 149.136   91.39  149.26  93.089 149.934
  96.435 149.998 106.872 150.247 116.003 150.332 125.877 150.106 127.236 150.018
 133.969 149.919  137.66 150.371 141.214  151.13 155.468 151.296 160.262 151.273
 164.072  151.52 171.474 151.497 176.551 151.766 179.915 152.426
#Mann= 6 ,-1 , 0
       0      .1       0  39.617     .04       0  73.261    .036       0
  91.143      .1       0  96.435     .04       0 127.236      .1       0
#XS Ineff= 2 ,-1
     .53   25.55  155.53     123  178.33  154.89
Permanent Ineff=
       T       T
#Block Obstruct= 2 ,-1
   13.74   24.49  155.37  139.74   152.6  154.12
Bank Sta=73.261,91.39
XS Rating Curve= 0 ,0
Exp/Cntr=0.3,0.1

Type RM Length L Ch R = 1 ,3383.835,51.033,50.913,50.794
XS GIS Cut Line= 4
529018.2061944674777685.07429951529082.7609050134777613.74018904
529100.8138944674777549.53829951529132.9666944674777506.99769951
#Sta/Elev= 30
       0 152.291  11.957 151.622  13.709 150.744  21.987  150.55  24.687 150.236
  26.228 149.618  26.902 149.236  35.788 148.964  48.747 149.224  61.234 149.254
  74.252 148.969 108.415  149.02 112.094  149.21 114.742 149.007 115.001 148.756
 116.465 146.939 119.014 146.407 125.717 146.865 126.295 147.258 128.985  149.01
 129.485 149.335 134.188 149.538 164.571 150.193 170.363 150.077 175.646 149.966
 177.341 150.257 197.455 151.023 204.062 151.273  210.62 151.171 216.224 151.349
#Mann= 9 ,-1 , 0
       0    .045       0  11.957      .1       0  26.228     .04       0
 108.415      .1       0 115.001    .036       0 126.295      .1       0
 134.188     .04       0 170.363     .05       0 197.455      .1       0
#XS Ineff= 2 ,-1
    1.76   46.26  152.68  195.81  217.18  152.52
Permanent Ineff=
       T       T
Bank Sta=114.742,128.985
XS Rating Curve= 0 ,0
Exp/Cntr=0.3,0.1

Type RM Length L Ch R = 1 ,3332.922,65.506,66.991,68.476
XS GIS Cut Line= 4
529023.2443695134777698.60410197529130.6419805814777634.74670408
529151.4115582744777550.49271408  529179.18961034777526.24357268
#Sta/Elev= 30
       0 152.498   9.925 152.069  15.214 151.412  16.901 150.609  18.392  150.38
  26.954 150.271  29.608 149.298  39.062 148.743  57.998 148.431 116.243 147.992
 124.948 147.753 132.522 147.996 136.893  147.82 146.548  147.95 153.777 147.657
 158.036  146.55 160.887 146.242 163.839 146.474  166.64  147.68 168.499 148.529
  183.49   149.3 188.891 149.434 195.201 149.154  197.83 149.894 206.115 150.828
 225.067 151.106 238.152 151.727 243.432  152.81 245.717 154.769 248.598 155.407
#Mann= 8 ,-1 , 0
       0    .045       0  15.214      .1       0  29.608     .04       0
 146.548      .1       0 153.777    .036       0  166.64      .1       0
 168.499     .04       0  183.49     .05       0
#XS Ineff= 1 ,-1
  198.68  246.04  155.03
Permanent Ineff=
       T
Bank Sta=153.777,166.64
XS Rating Curve= 0 ,0
Exp/Cntr=0.3,0.1

Type RM Length L Ch R = 1 ,3265.931,59.039,60.157,61.274
XS GIS Cut Line= 3
529033.7970944674777729.08959951529180.3620944674777654.04829951
529237.8155944674777577.83449951
#Sta/Elev= 30
       0 151.923   1.743 151.825   18.89 150.912  27.372 150.122  33.988 150.105
  36.722 149.792  38.495 149.219 122.324 147.232 147.433  147.16  154.12 147.679
 160.064 147.506 162.619 147.745 174.993 147.191 181.786  147.26 186.212 147.192
 191.661 146.036 194.714 145.725 197.444 145.937 201.141 147.187 203.271 147.881
 204.514  148.31 213.024 148.486 215.175 148.867  226.47 148.774 233.687 149.172
 235.931 149.726 240.835 152.679 249.413 159.098 253.992 162.108 260.103 165.087
#Mann= 8 ,-1 , 0
       0    .045       0   1.743      .1       0  38.495     .04       0
 181.786      .1       0 186.212    .036       0 201.141      .1       0
 203.271     .05       0 213.024     .08       0
#Block Obstruct= 1 ,-1
    5.81    19.3  159.07
Bank Sta=186.212,201.141
XS Rating Curve= 0 ,0
Exp/Cntr=0.3,0.1

Type RM Length L Ch R = 1 ,3205.774,75.406,75.633,75.86
XS GIS Cut Line= 3
529073.6627556324777780.68054449529227.3640310624777682.29100258
 529295.12973532  4777633.834826
#Sta/Elev= 30
       0 156.072   1.488 155.673   7.187 153.945  18.154 151.642  20.024 151.336
  21.825 150.105  23.136   149.7  47.382 149.898  62.597 149.583  84.688 148.726
 117.072 146.803 127.754 146.544 147.282 146.722 165.542 146.715 181.198 146.928
 188.139 146.882  188.94  146.63 194.167 145.541 197.604  145.58 200.805 146.164
 202.721 146.643 209.054 146.852 212.642 146.996 222.894 150.589 228.824 153.206
 236.714 157.458 242.811 159.965   257.8  165.92 264.133 168.095 265.803 168.352
#Mann= 11 ,-1 , 0
       0      .1       0   1.488     .04       0  18.154      .1       0
  62.597    .045       0 147.282     .04       0 165.542      .1       0
 181.198      .1       0  188.94    .038       0 200.805      .1       0
 209.054     .08       0 242.811     .08       0
Bank Sta=188.94,202.721
XS Rating Curve= 0 ,0
Exp/Cntr=0.3,0.1

Type RM Length L Ch R = 1 ,3130.142,28.097,27.548,27
XS GIS Cut Line= 4
529080.6978944674777790.06069951529188.5697944674777774.81789951
529263.6110944674777747.84999951529329.7744882614777706.44727519
#Sta/Elev= 30
       0 154.946   2.454 154.292   7.515 153.021  22.459 150.978  24.792 149.784
  25.925 149.539  42.682 149.035  48.627 148.945   51.58 149.153  73.965 148.664
  82.901 148.409  86.271 148.727  92.988  148.59  96.545 148.293 100.727 147.617
 107.891 147.602 115.815 146.825 123.978 146.548 144.623 146.242 195.254 146.254
 202.046 145.147 209.172 145.318  212.68  146.25 216.888 147.397 231.098 146.941
  235.39 146.302 239.986 147.285 243.926 148.771  253.43 152.777 266.733 160.825
#Mann= 10 ,-1 , 0
       0      .1       0   2.454     .04       0  22.459      .1       0
  73.965    .045       0  82.901      .1       0 123.978      .1       0
 144.623      .1       0 195.254    .036       0  212.68      .1       0
 231.098     .08       0
Levee=0,,,-1,217.27,147.43,,Levee 28
#XS Ineff= 2 , 0
           66.34  153.58
Permanent Ineff=
       T       T
#Block Obstruct= 1 ,-1
   49.69   69.52  152.14
Bank Sta=195.254,212.68
XS Rating Curve= 0 ,0
Exp/Cntr=0.3,0.1

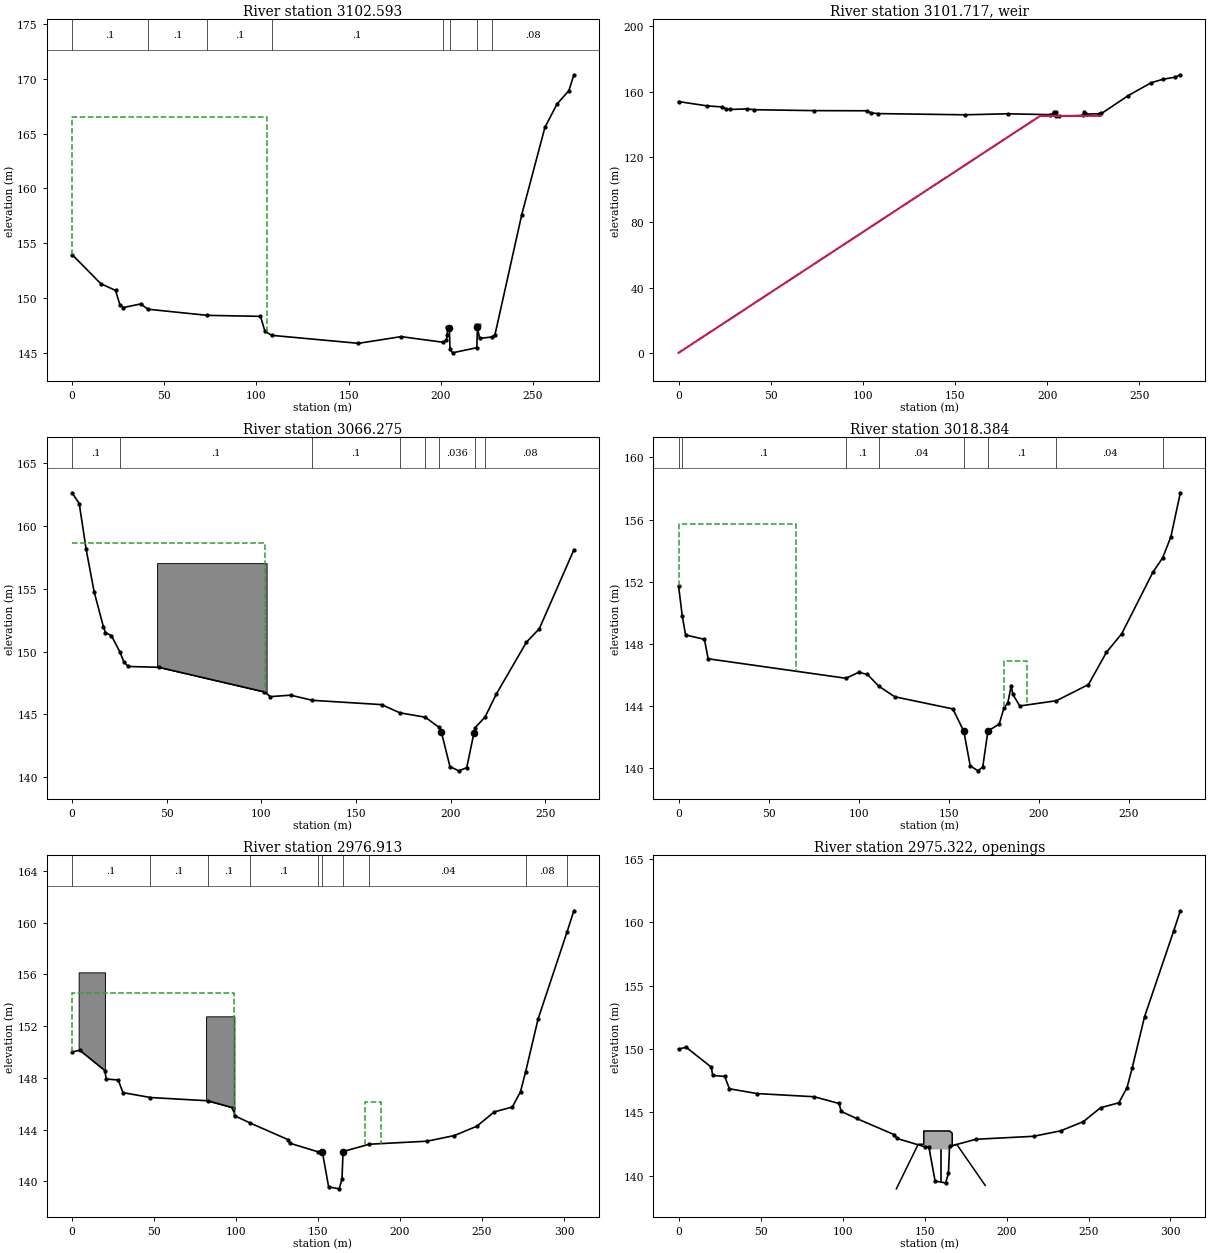
Type RM Length L Ch R = 1 ,3102.593,34.668,36.318,37.969
XS GIS Cut Line= 4
529101.9315764144777825.45706836529288.1494769284777765.34715406
529324.8800304424777733.90309871 529351.315020484777724.25330749
#Sta/Elev= 30
       0 153.961  15.593   151.3  23.557 150.686   25.94 149.384  27.819 149.127
  37.276 149.453  41.098 148.971  73.405  148.41 102.202  148.32 104.585 146.974
 108.215 146.587  155.35 145.856 178.458 146.468 201.216 145.952 203.078 146.173
 203.553 146.634 203.573 147.302 204.636 147.295 204.983 145.314 206.352 144.988
 219.546  145.46  219.86  147.32 221.043 146.302 227.832  146.44 229.406 146.656
 243.911 157.607  256.46 165.565 263.043 167.705 269.463 168.923 272.171 170.374
#Mann= 8 ,-1 , 0
       0      .1       0  41.098      .1       0  73.405      .1       0
 108.215      .1       0 201.216      .1       0 204.983    .036       0
 219.546      .1       0 227.832     .08       0
Levee=0,,,-1,219.96,147.32,,Levee 28
#XS Ineff= 2 , 0
          105.73  166.51
Permanent Ineff=
       T       T
Bank Sta=204.636,219.86
XS Rating Curve= 0 ,0
Exp/Cntr=0.3,0.1

Type RM Length L Ch R = 5 ,3101.717,,,
BEGIN DESCRIPTION:
E139
END DESCRIPTION:
IW Pilot Flow=0
#Inline Weir SE= 9
       0       0  196.15  145.19   205.7  145.19  208.73  145.18  209.31  145.17
  213.12  145.17  217.81  145.16  220.44  145.21  229.01  145.21
IW Dist,WD,Coef,Skew,MaxSub,Min_El,Is_Ogee,SpillHt,DesHd
0.1,1.9,1.7,0,0.98,, 0 ,,,0,0,

Type RM Length L Ch R = 1 ,3066.275,47.738,47.891,48.045
XS GIS Cut Line= 4
529118.2185387144777853.37682215529234.2980788494777811.16608028
529294.5803395544777793.83863527529370.8234470754777773.31564942
#Sta/Elev= 30
       0 162.625    3.78 161.771   7.407 158.156  11.633  154.77  16.549 151.971
  17.612 151.511  20.805  151.26    25.3 149.962  27.389 149.168  29.735 148.811
  45.846 148.748 101.643  146.79 104.808 146.415 115.506  146.53 127.055  146.12
 163.547 145.779 173.199 145.129 186.671 144.778 193.899 143.975 195.157 143.613
 199.697 140.854 204.322 140.513 208.587 140.765  212.43  143.56 213.013 143.944
 218.256  144.79 224.267 146.633 240.122 150.741 246.937 151.817 265.195  158.08
#Mann= 8 ,-1 , 0
       0      .1       0    25.3      .1       0 127.055      .1       0
 173.199     .04       0 186.671      .1       0 193.899    .036       0
 213.013      .1       0 218.256     .08       0
#XS Ineff= 2 , 0
          102.03  158.67
Permanent Ineff=
       T       T
#Block Obstruct= 1 ,-1
   44.93  102.82  157.03
Bank Sta=195.157,212.43
XS Rating Curve= 0 ,0
Exp/Cntr=0.3,0.1

Type RM Length L Ch R = 1 ,3018.384,41.917,41.47,41.023
XS GIS Cut Line= 3
529165.0460944674777882.63489951529290.3591944674777843.06229951
529434.1395944674777810.74469951
#Sta/Elev= 30
       0 151.745   2.063 149.795   3.906 148.566  14.393 148.283  16.448 147.031
  93.057 145.775 100.086 146.163 104.979 146.019 111.234  145.27 120.122 144.585
 152.425 143.801 158.515 142.353 162.039 140.143 166.331 139.814 169.019 140.063
  171.88  142.38 178.137 142.821 180.759 143.847 182.964 144.199 184.832  145.31
 185.669 144.754 189.574 143.992  209.95  144.33 227.737 145.372 237.708 147.442
 246.266 148.652 263.524 152.602 268.996 153.541 273.532 154.887 278.781 157.723
#Mann= 8 ,-1 , 0
       0      .1       0   2.063      .1       0  93.057      .1       0
 111.234     .04       0 158.515    .036       0  171.88      .1       0
  209.95     .04       0 268.996     .08       0
#XS Ineff= 2 ,-1
       0   65.02  155.73  181.06  193.48   146.9
Permanent Ineff=
       T       T
Bank Sta=158.515,171.88
XS Rating Curve= 0 ,0
Exp/Cntr=0.5,0.3

Type RM Length L Ch R = 1 ,2976.913,3.21,3.21,3.21
XS GIS Cut Line= 4
529177.3330548364777927.51484068529317.3210229834777881.01707034
529342.6262338524777871.99655085529466.707476623 4777828.0887573
#Sta/Elev= 30
       0     150   4.676 150.139  20.022 148.564  20.812 147.916  28.151 147.834
  31.019  146.86  47.827 146.482  82.652 146.231  97.943 145.697   99.12 145.073
 108.567 144.513 131.551 143.234 133.133 142.937 150.059  142.28  152.63 142.271
 156.456 139.572 162.877 139.421  164.59 140.171 165.256 142.305 181.301 142.871
 216.469 143.105 233.045 143.539 246.848 144.264 257.382 145.365 268.513 145.752
 273.488 146.945 276.621 148.492 284.172  152.55 301.863 159.294 305.994 160.921
#Mann= 10 ,-1 , 0
       0      .1       0  47.827      .1       0  82.652      .1       0
 108.567      .1       0 150.059      .1       0  152.63    .036       0
 165.256      .1       0 181.301     .04       0 276.621     .08       0
 301.863     .08       0
#XS Ineff= 2 ,-1
       0   98.99  154.56  178.85  188.41  146.16
Permanent Ineff=
       T       T
#Block Obstruct= 2 ,-1
    4.01   20.04  156.16   81.72   98.99  152.76
Bank Sta=152.63,165.256
XS Rating Curve= 0 ,0
Exp/Cntr=0.5,0.3

Type RM Length L Ch R = 4 ,2975.322,,,
BEGIN DESCRIPTION:
E140
END DESCRIPTION:
Bridge Culvert--1,0,-1,-1, 0
Deck Dist Width WeirC Skew NumUp NumDn MinLoCord MaxHiCord MaxSubmerge Is_Ogee
0.01,3.01,1.44,0, 26, 26, , , 0.95, 0, ,,,
 132.816  133.21 146.171 149.553 149.574 153.741 153.968  154.99 155.878  157.59
 159.128 159.762  159.79 163.262  163.39  164.59 165.049 165.266 165.295 165.785
 166.898 166.901 168.741 169.666  186.83 187.004
 138.955 139.059  142.48 142.486 143.527 143.527 143.527 143.527 143.527 143.527
 143.527 143.527 143.527 143.527 143.527 143.527 143.527 143.527 143.527 143.473
 143.351 142.344 142.426 142.467 139.257 139.224
 138.955  78.951   79.02  79.038  79.038  79.061 142.052 142.056 142.059 142.065
  142.07 142.081 142.081 142.062 142.062 142.055 142.053  79.272  79.271  79.258
  79.229  79.229   79.18  79.156  78.704 139.224
 132.797 133.191 146.152 149.534 149.555 153.722 153.949 154.971 155.859 157.571
 159.109 159.743 159.771 163.243 163.371 164.571  165.03 165.247 165.276 165.766
 166.879 166.882 168.722 169.647 186.811 186.985
 138.955 139.059  142.48 142.486 143.527 143.527 143.527 143.527 143.527 143.527
 143.527 143.527 143.527 143.527 143.527 143.527 143.527 143.527 143.527 143.473
 143.351 142.344 142.426 142.467 139.257 139.224
 138.955  78.951   79.02  79.038  79.038  79.061 142.052 142.056 142.059 142.065
  142.07 142.081 142.081 142.062 142.062 142.055 142.053  79.272  79.271  79.258
  79.229  79.229   79.18  79.156  78.704 139.224
Pier Skew, UpSta & Num, DnSta & Num=  ,159.455, 2 ,159.435, 2 , 0 , 0 , 0 ,,
    .634    .634
     138     143
    .634    .634
     138     143
BR Coef=-1 , 1 , 0 ,, 0 ,,,0.8,-1,1.4,0,
WSPro=,,,, 1 ,,,, 0 ,,,, 0 ,,,,-1 ,-1 ,-1 , 0 , 0 , 0 , 0 , 0
BC Mult= 1 ,0,149,0,149
BC Mult= 3 ,149,166,149,167
BC Mult= 1 ,166,320,167,320
BC Design=,, 0 ,, 0 ,,,,,,
BC Use User HTab Curves=0
BC User HTab FreeFlow(D)= 0

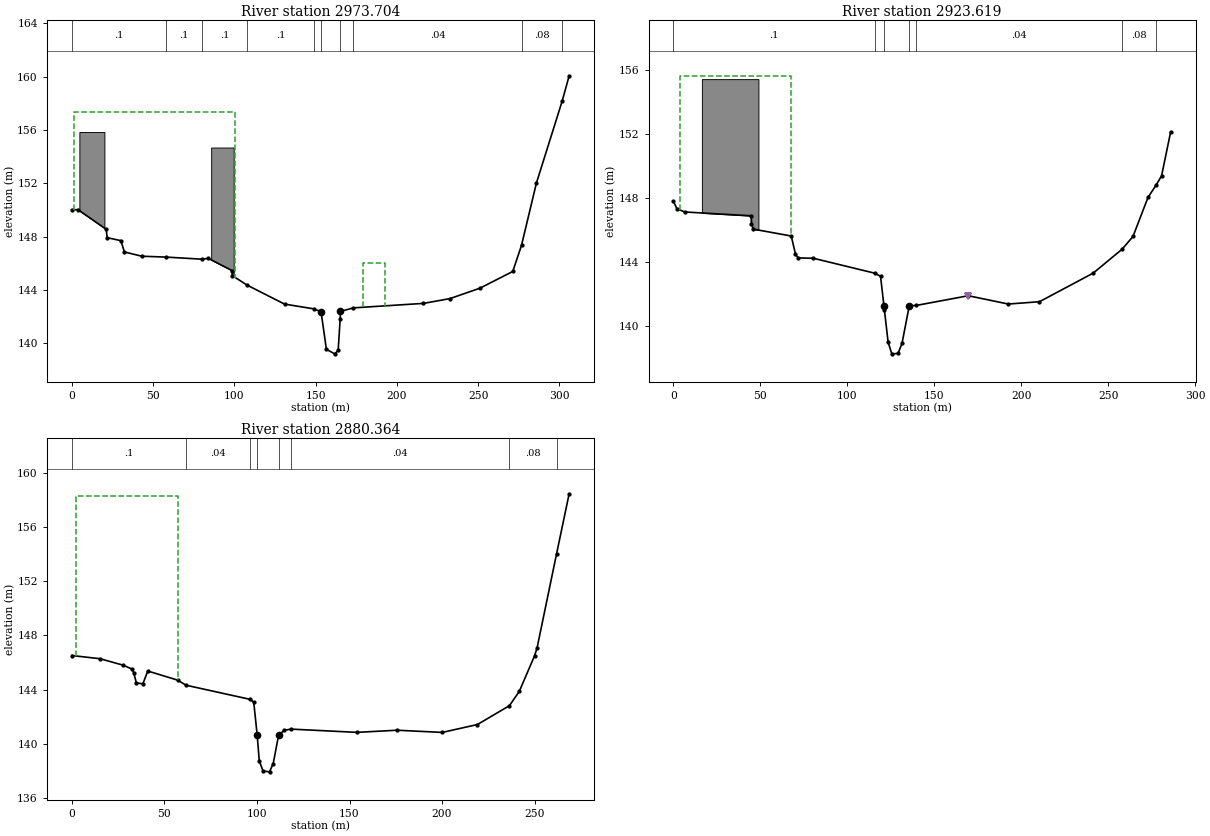
Type RM Length L Ch R = 1 ,2973.704,49.741,50.085,50.429
XS GIS Cut Line= 4
529178.104369453 4777930.6292145  529318.09233764777884.13144416
529343.3975484694777875.11092466 529467.478791244777831.20313111
#Sta/Elev= 30
       0     150   3.682 150.031  21.084 148.558  21.777 147.924  30.207   147.7
  32.314 146.854  43.069 146.534  58.078 146.469  80.048 146.312  83.947 146.377
  98.601 145.456  98.699 145.082 107.894 144.366 130.865 142.947 148.713 142.593
  153.34  142.38 156.622 139.561 161.695 139.219  163.86  139.47 165.096 141.817
 165.282   142.4 173.285 142.665 216.355 142.999 232.668 143.359  251.09 144.139
 271.299 145.393  276.68 147.349 285.845 152.015 301.772 158.187 305.995 160.057
#Mann= 10 ,-1 , 0
       0      .1       0  58.078      .1       0  80.048      .1       0
 107.894      .1       0 148.713      .1       0  153.34    .036       0
 165.096      .1       0 173.285     .04       0  276.68     .08       0
 301.772     .08       0
#XS Ineff= 2 ,-1
    1.54  100.53  157.36  179.16  192.42  146.04
Permanent Ineff=
       T       T
#Block Obstruct= 2 ,-1
    4.63   20.04  155.84   85.73    99.6  154.68
Bank Sta=153.34,165.282
XS Rating Curve= 0 ,0
Exp/Cntr=0.5,0.3

Type RM Length L Ch R = 1 ,2923.619,44.139,43.254,42.37
XS GIS Cut Line= 4
529219.3789109934777969.06603971529324.3228155614777932.93277426
529392.3619316624777915.63507373529486.4937618744777869.63995633
#Sta/Elev= 30
       0  147.79   2.009 147.337   6.399 147.122    44.7 146.882  44.834 146.391
  45.892 146.049  67.766 145.617  70.217 144.484  71.815 144.248  80.546 144.224
 115.687 143.294 119.123 143.099  121.09  141.24  121.35 140.988 123.477 138.977
 125.602 138.247 129.168 138.269 131.459 138.897 135.646 141.252 139.492 141.271
  169.61 141.882  192.57 141.362  210.52 141.508 241.403 143.297 258.081 144.796
 264.295 145.591 272.914  148.03 277.469 148.785 280.705 149.375 285.962 152.141
#Mann= 7 ,-1 , 0
       0      .1       0 115.687      .1       0  121.35    .036       0
 135.646      .1       0 139.492     .04       0 258.081     .08       0
 277.469     .08       0
Levee=0,,,-1,169.69,141.89,,Levee 38
#XS Ineff= 1 ,-1
     3.7    67.4  155.64
Permanent Ineff=
       T
#Block Obstruct= 1 ,-1
   16.39    48.9  155.43
Bank Sta=121.09,135.646
XS Rating Curve= 0 ,0
Exp/Cntr=0.3,0.1

Type RM Length L Ch R = 1 ,2880.364,65.162,62.878,60.594
XS GIS Cut Line= 3
529260.3085378574778019.66673977   529402.8081164777943.82674592
529499.4342944674777897.30969951
#Sta/Elev= 30
       0  146.52   15.25 146.282  27.725 145.806  32.518 145.519  33.375  145.26
  34.872 144.501  38.367 144.432  41.024 145.375  57.113 144.705  61.712 144.327
  96.473  143.28  98.275 143.059 100.131 140.648 101.257 138.731 103.303 137.999
 106.785 137.936 108.789 138.548 111.707 140.649 114.763 141.003   118.4 141.089
 154.017 140.849 175.685 141.007 200.127 140.845 219.095 141.427 236.371 142.816
 241.698 143.866 249.953 146.489 251.281 147.047 261.894 154.042 268.664 158.454
#Mann= 8 ,-1 , 0
       0      .1       0  61.712     .04       0  96.473      .1       0
 100.131    .036       0 111.707      .1       0   118.4     .04       0
 236.371     .08       0 261.894     .08       0
#XS Ineff= 1 ,-1
    2.38   57.09  158.27
Permanent Ineff=
       T
Bank Sta=100.131,111.707
XS Rating Curve= 0 ,0
Exp/Cntr=0.3,0.1