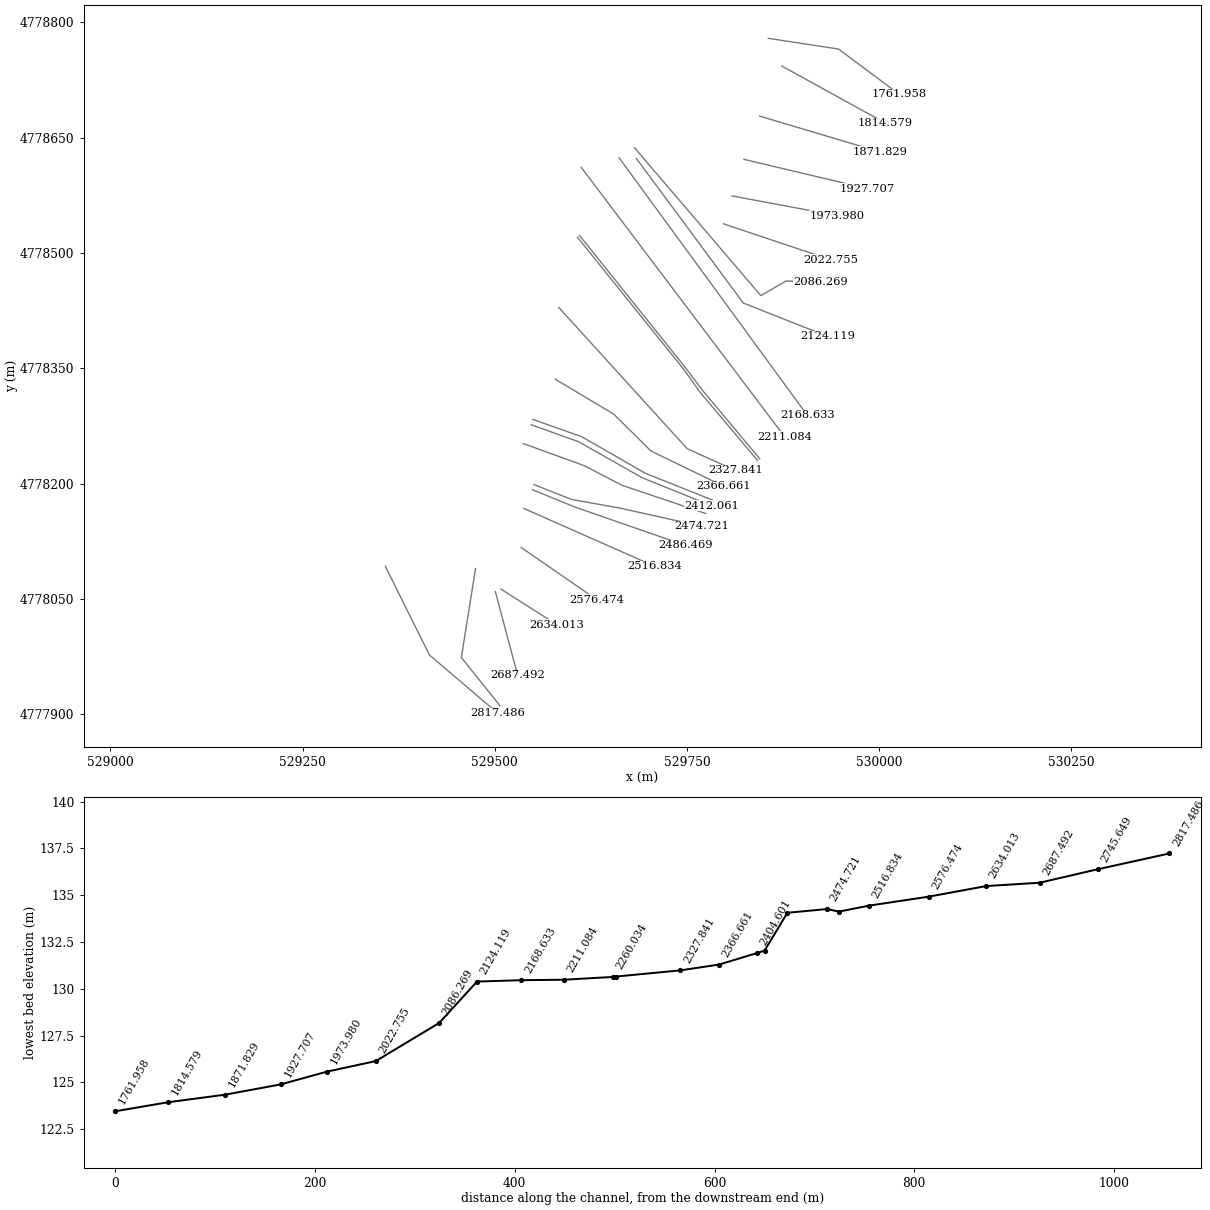
HEC-RAS study Durango.prj: Durango

--- Durango.g18 (geometry) --- (continued)

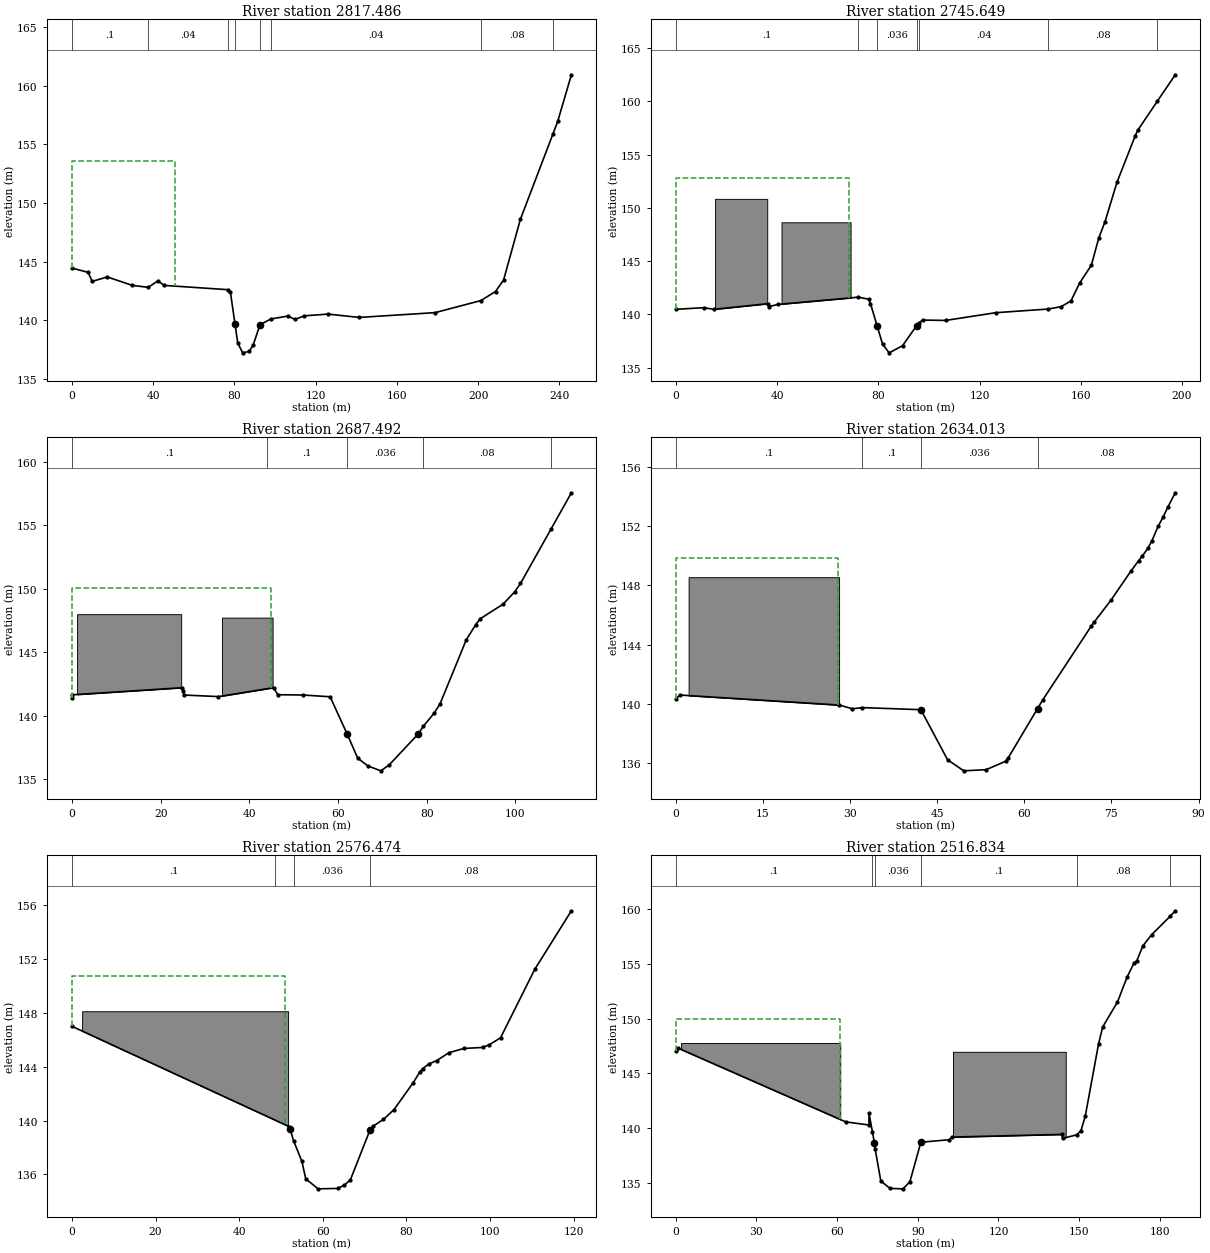
Type RM Length L Ch R = 1 ,2817.486,74.123,71.837,69.551
XS GIS Cut Line= 3
529357.632590242 4778092.5343848529415.012817468 4777977.1143875
529504.0511010944777901.26696071
#Sta/Elev= 30
       0 144.459   8.016 144.086   9.931 143.321  17.441 143.698  29.688 142.981
  37.543 142.813  42.317 143.363   45.41 142.978  77.028 142.611  78.011 142.401
  80.287 139.661  81.626 138.062  84.043 137.233  87.239 137.355  89.221 137.908
  92.559 139.626  97.951 140.119 106.291 140.366 109.793 140.076 114.273 140.383
 126.071 140.534 141.385  140.25  178.77 140.659 201.286 141.685 208.509 142.457
 212.491 143.444 220.766 148.618 236.714  155.85 239.115 156.946  245.86 160.923
#Mann= 8 ,-1 , 0
       0      .1       0  37.543     .04       0  77.028      .1       0
  80.287    .036       0  92.559      .1       0  97.951     .04       0
 201.286     .08       0 236.714     .08       0
#XS Ineff= 2 , 0
           50.66   153.6
Permanent Ineff=
       T       T
Bank Sta=80.287,92.559
XS Rating Curve= 0 ,0
Exp/Cntr=0.3,0.1

Type RM Length L Ch R = 1 ,2745.649,56.601,58.158,59.715
XS GIS Cut Line= 3
529475.0021147414778089.48050557529456.5639944674777973.81669951
529506.6892944674777911.16009951
#Sta/Elev= 30
       0 140.474  11.213 140.628   14.91 140.473  36.293 141.001  36.745 140.719
  40.343 140.936  72.137 141.613   76.17 141.424  76.921 141.015  79.542 138.915
  81.686  137.22  84.293 136.389  89.572 137.054   95.19  138.95  95.939 139.181
  97.497 139.464 106.636 139.431 126.375 140.155 147.253 140.501 152.279 140.726
 156.118 141.252 159.611 142.956 164.207 144.611 167.143 147.173 169.553 148.664
  174.33 152.398  181.54 156.756 182.514 157.272  190.22 159.983 197.364 162.484
#Mann= 7 ,-1 , 0
       0      .1       0  72.137      .1       0  79.542    .036       0
   95.19      .1       0  95.939     .04       0 147.253     .08       0
  190.22     .08       0
#XS Ineff= 2 , 0
           68.55  152.84
Permanent Ineff=
       T       T
#Block Obstruct= 2 ,-1
   15.51   36.12  150.84   41.76   69.07  148.64
Bank Sta=79.542,95.19
XS Rating Curve= 0 ,0
Exp/Cntr=0.3,0.1

Type RM Length L Ch R = 1 ,2687.492,50.735,53.479,56.223
XS GIS Cut Line= 2
529500.7533868854778059.55724271529529.7732719194777950.73267384
#Sta/Elev= 27
       0 141.422    .068 141.655  24.752  142.21  25.044 141.957  25.271 141.635
  33.031 141.513  45.451 142.215   46.43  141.66  52.074 141.638  58.219   141.5
   62.01 138.605  64.444 136.664  66.764 136.051   69.65 135.669  71.531 136.135
  78.097 138.574  79.201 139.167  81.652 140.198  82.987 140.924  88.918 145.981
  91.031 147.164  92.023  147.63  97.214 148.786  99.811 149.744 101.149 150.421
 108.066 154.722 112.627 157.556
#Mann= 5 ,-1 , 0
       0      .1       0  44.037      .1       0   62.01    .036       0
  79.201     .08       0 108.066     .08       0
#XS Ineff= 2 , 0
           44.83  150.03
Permanent Ineff=
       T       T
#Block Obstruct= 2 ,-1
    1.16   24.63     148   33.83   45.25  147.73
Bank Sta=62.01,78.097
XS Rating Curve= 0 ,0
Exp/Cntr=0.3,0.1

Type RM Length L Ch R = 1 ,2634.013,57.679,57.539,57.399
XS GIS Cut Line= 2
529508.0083944674778062.85499951529580.5580944674778016.68699951
#Sta/Elev= 25
       0 140.353    .708 140.603  28.167 139.927  30.407 139.674  32.093 139.756
   42.19 139.614  46.781 136.242  49.577 135.491  53.437 135.572   56.77 136.132
  57.202 136.346  62.275 139.687  63.135 140.252  71.548 145.263  72.023  145.52
  74.905 146.991   78.33 148.946  79.698 149.673  80.321 149.977  81.277 150.503
  81.981 151.015  83.059 151.995  83.876 152.592  84.733 153.294  85.994 154.243
#Mann= 4 ,-1 , 0
       0      .1       0  32.093      .1       0   42.19    .036       0
  62.275     .08       0
#XS Ineff= 2 , 0
           27.93  149.83
Permanent Ineff=
       T       T
#Block Obstruct= 1 ,-1
     2.2   28.11  148.55
Bank Sta=42.19,62.275
XS Rating Curve= 0 ,0
Exp/Cntr=0.3,0.1

Type RM Length L Ch R = 1 ,2576.474,58.947,59.64,60.332
XS GIS Cut Line= 2
529534.3900718114778116.93746994529632.6619552214778049.00455725
#Sta/Elev= 26
       0     147  51.996 139.544    52.2  139.35  52.998  138.51  54.996 136.971
  55.919 135.674  58.871 134.925  63.598 134.957  65.181 135.203  66.606 135.597
  71.324  139.32   71.94  139.56  74.522 140.091  77.033 140.813  81.625  142.81
  83.175 143.584  83.867  143.85  85.304 144.186  87.238 144.456   90.21 145.042
  93.727 145.356  98.243  145.43  99.825 145.632  102.52 146.145 110.696  151.23
 119.466 155.584
#Mann= 4 ,-1 , 0
       0      .1       0  48.599      .1       0  52.998    .036       0
  71.324     .08       0
#XS Ineff= 2 , 0
           50.96  150.76
Permanent Ineff=
       T       T
#Block Obstruct= 1 ,-1
    2.43    51.7  148.12
Bank Sta=52.2,71.324
XS Rating Curve= 0 ,0
Exp/Cntr=0.3,0.1

Type RM Length L Ch R = 1 ,2516.834,30.064,30.365,30.666
XS GIS Cut Line= 2
529537.9588570374778167.66243382529707.8497944674778092.53439951
#Sta/Elev= 30
       0     147    .888  147.29  63.161 140.564  71.839 140.275  71.847 141.328
  73.097 139.682   73.85  138.65  74.147 138.066  76.233 135.175  79.614 134.486
   84.49 134.447   87.06 135.093  91.125 138.704 101.723 138.931 102.618 139.173
 143.464 139.417 143.922  139.06 149.074 139.374 150.686 139.765 152.262  141.06
 157.246 147.702  158.78 149.236 164.253 151.501 167.872 153.802 170.367 155.041
 171.461 155.271 173.647 156.611 176.928 157.642 183.811 159.326 185.761 159.837
#Mann= 6 ,-1 , 0
       0      .1       0  73.097      .1       0  74.147    .036       0
  91.125      .1       0 149.074     .08       0 183.811     .08       0
#XS Ineff= 2 , 0
           61.15     150
Permanent Ineff=
       T       T
#Block Obstruct= 2 ,-1
    1.94   61.15  147.76  103.08  145.02  146.96
Bank Sta=73.85,91.125
XS Rating Curve= 0 ,0
Exp/Cntr=0.5,0.3

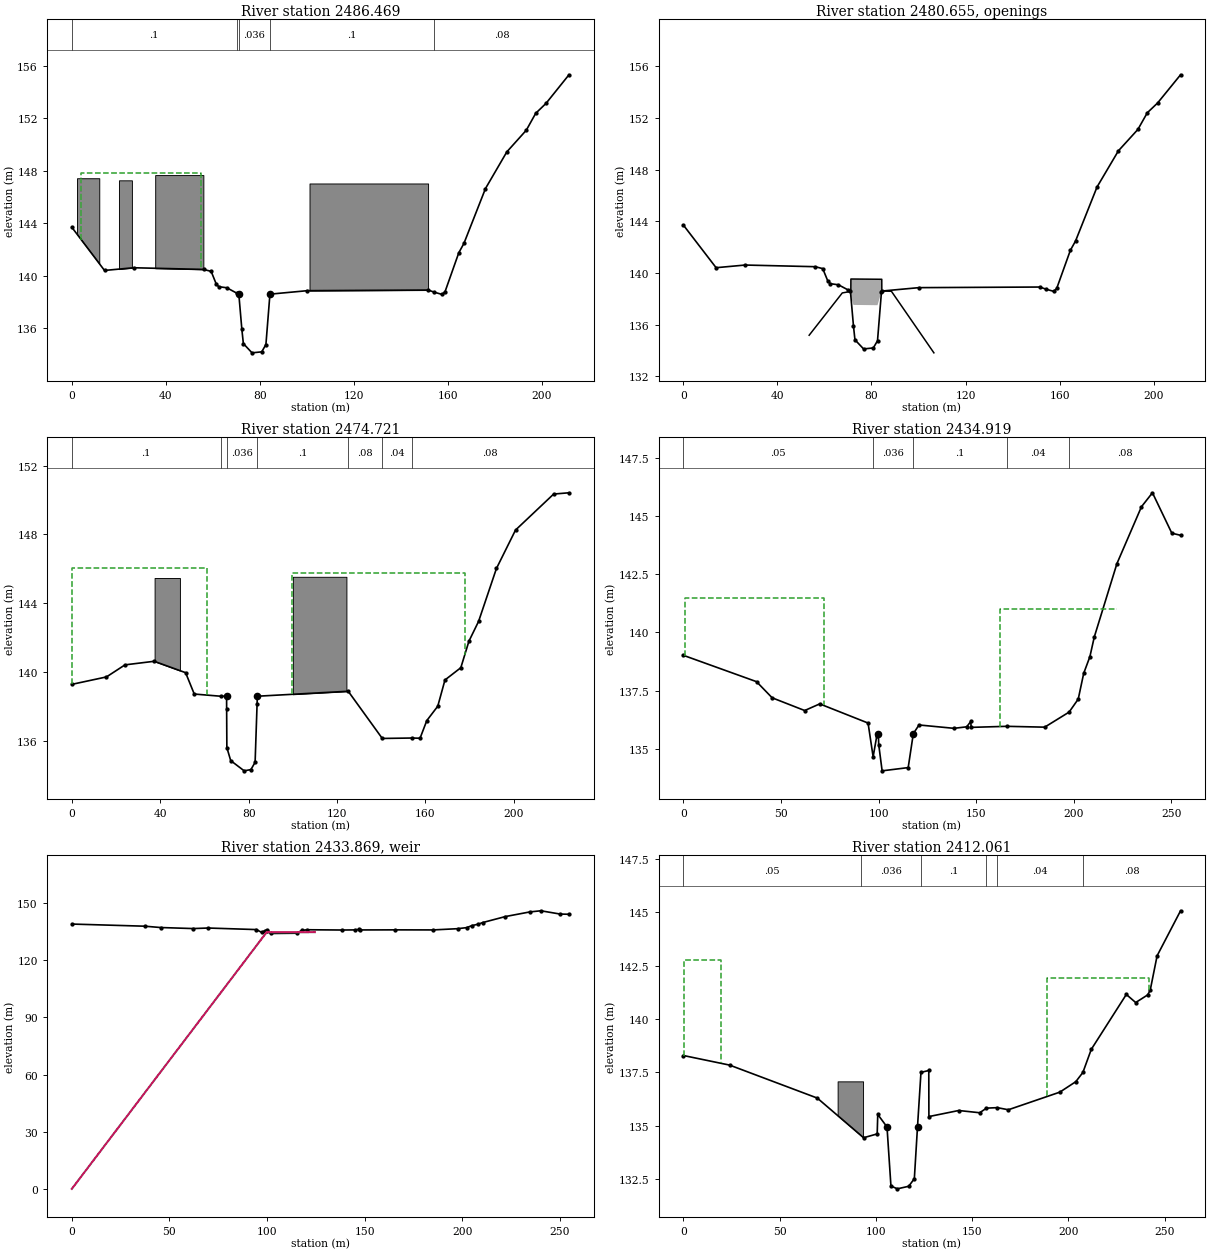
Type RM Length L Ch R = 1 ,2486.469,11.161,11.748,12.336
XS GIS Cut Line= 3
529548.9000143284778192.12535389529604.6229919194778169.39734944
529747.5458311444778119.76909396
#Sta/Elev= 30
       0 143.699    13.9 140.408   26.24 140.614   56.02 140.486   59.26 140.338
  61.395  139.39  62.454 139.172  65.935 139.087  70.146 138.678  71.042 138.584
  72.328 135.909  72.966 134.831  76.647 134.126  80.776 134.202  82.561  134.76
  84.236 138.528  84.269   138.6 100.177 138.866 151.629 138.913 154.165 138.751
 157.536 138.577 158.784 138.802 164.607 141.757 166.795 142.471 175.955 146.653
 185.036 149.448  193.32 151.101 197.326  152.39 201.716 153.148 211.474 155.328
#Mann= 5 ,-1 , 0
       0      .1       0  70.146      .1       0  71.042    .036       0
  84.236      .1       0 154.165     .08       0
#XS Ineff= 1 ,-1
    3.96   55.07  147.84
Permanent Ineff=
       T
#Block Obstruct= 4 ,-1
     2.2   11.67  147.44   20.04   25.55  147.28   35.46   55.95  147.68
   101.1  151.54  147.04
Bank Sta=71.042,84.269
XS Rating Curve= 0 ,0
Exp/Cntr=0.5,0.3

Type RM Length L Ch R = 4 ,2480.655,,,
BEGIN DESCRIPTION:
E141
END DESCRIPTION:
Bridge Culvert--1,0,-1,-1, 0
Deck Dist Width WeirC Skew NumUp NumDn MinLoCord MaxHiCord MaxSubmerge Is_Ogee
0.01,11.55,1.44,0, 13, 13, , , 0.95, 0, ,,,
  53.484  53.627  67.578  71.012  71.207  71.236  84.375  84.376  84.401  84.591
  88.465 106.351 106.546
 135.185 135.218 138.458 138.567 138.573 139.534 139.513 139.513 138.605 138.604
 138.587 133.875 133.824
 135.185  72.481  72.517  72.526 137.533 137.533 137.503 137.257 129.683  72.021
  72.012  71.972 133.824
  52.432  52.575  66.526   69.96  70.155  70.184  83.323  83.324  83.349  83.539
  87.413 105.299 105.494
 135.185 135.218 138.458 138.567 138.573 139.534 139.513 139.513 138.605 138.604
 138.587 133.875 133.824
 135.185  72.481  72.517  72.526 137.533 137.533 137.503 137.257 129.683  72.021
  72.012  71.972 133.824
BR Coef=-1 , 0 , 0 ,, 0 ,,,0.8,-1,,0,
WSPro=,,,, 1 ,,,, 0 ,,,, 0 ,,,,-1 ,-1 ,-1 , 0 , 0 , 0 , 0 , 0
BC Mult= 1 ,0,69.5,0,70
BC Mult= 3 ,69.5,84.3,70,84
BC Mult= 1 ,84.3,230,84,230
BC Design=,, 0 ,, 0 ,,,,,,
BC Use User HTab Curves=0
BC User HTab FreeFlow(D)= 0

Type RM Length L Ch R = 1 ,2474.721,40.917,39.802,38.687
XS GIS Cut Line= 4
529550.8821578254778198.75735252529600.3787038644778179.25937966
529661.8889097434778168.40863716529768.5277806064778144.63826929
#Sta/Elev= 30
       0 139.289  15.666 139.721  24.041 140.422  37.249  140.63  51.471 139.968
  55.386 138.727  67.362138.5992  70.013   138.6  70.041 137.831  70.137 135.616
  71.875 134.859  77.971 134.264  81.014 134.337  82.918  134.76  83.803 138.119
  83.926   138.6 125.038 138.889 140.459 136.146 153.774 136.171 157.544 136.159
 160.606 137.186 165.558  138.02 168.814 139.544 175.986 140.257 179.651 141.797
  184.02 142.947 192.098 146.022 200.727 148.254 217.992 150.348 224.915 150.422
#Mann= 7 ,-1 , 0
       0      .1       0  67.362      .1       0  70.041    .036       0
  83.803      .1       0 125.038     .08       0 140.459     .04       0
 153.774     .08       0
#XS Ineff= 2 ,-1
       0   61.23  146.07   99.78  177.75  145.74
Permanent Ineff=
       T       T
#Block Obstruct= 2 ,-1
   37.44    48.9  145.47     100  124.23  145.54
Bank Sta=70.013,83.926
XS Rating Curve= 0 ,0
Exp/Cntr=0.5,0.3

Type RM Length L Ch R = 1 ,2434.919,22.994,22.857,22.721
XS GIS Cut Line= 4
529537.0282431774778252.14375248529616.2259424164778223.43396324
529665.8221821814778197.71797858529774.4636661814778161.12684033
#Sta/Elev= 30
       0 139.017  37.458 137.888  45.465 137.196  62.137  136.65  69.845 136.935
   94.62 136.113  97.211 134.665  99.102  135.57  99.884 135.655  100.07 135.192
 101.818 134.064 115.177 134.203 117.802 135.659 120.723 136.031 138.644 135.887
 145.168 135.952 147.233  136.18  147.44 135.928 165.662 135.973 185.121 135.937
 197.632 136.583 202.311  137.14 205.113 138.245 208.281 138.959 210.539 139.805
 222.138  142.95 234.711 145.389 240.342 145.988 250.276 144.255 254.746 144.165
#Mann= 5 ,-1 , 0
       0     .05       0  97.211    .036       0 117.802      .1       0
 165.662     .04       0 197.632     .08       0
#XS Ineff= 2 ,-1
    1.06   71.89  141.47  162.29  222.03  141.01
Permanent Ineff=
       T       T
Bank Sta=99.884,117.802
XS Rating Curve= 0 ,0
Exp/Cntr=0.3,0.1

Type RM Length L Ch R = 5 ,2433.869,,,
BEGIN DESCRIPTION:
E142
END DESCRIPTION:
IW Pilot Flow=0
#Inline Weir SE= 4
       0       0   99.81  134.71  115.92   134.7  124.52  134.79
IW Dist,WD,Coef,Skew,MaxSub,Min_El,Is_Ogee,SpillHt,DesHd
0.1,2.7,1.7,0,0.98,, 0 ,,,0,0,

Type RM Length L Ch R = 1 ,2412.061,7.483,7.46,7.438
XS GIS Cut Line= 4
529547.4705541574778276.56387629529609.1749518924778254.46138601
529691.8191988534778207.62536607529782.3781802814778171.01998296
#Sta/Elev= 30
       0 138.291  23.989 137.842  69.517 136.297   93.57 134.438 100.643 134.617
 100.934  135.53 105.739 134.943 107.783 132.178 111.083 132.043 117.012 132.163
 119.941  132.52  121.58  134.95 123.379 137.501 127.441 137.589 127.499  135.43
 142.997 135.714 153.887 135.609 157.407 135.825  163.01 135.848 168.772 135.749
 195.488 136.574 203.785 137.064 207.475 137.496 211.851 138.581 230.043 141.153
 234.908 140.774  241.14 141.132 242.459 141.355 246.034 142.965 258.214 145.074
#Mann= 6 ,-1 , 0
       0     .05       0   92.26    .036       0 123.379      .1       0
 157.407    .045       0  163.01     .04       0 207.475     .08       0
#XS Ineff= 2 ,-1
     .53   19.56  142.75  188.99  241.59  141.93
Permanent Ineff=
       T       T
#Block Obstruct= 1 ,-1
   80.09    93.3  137.08
Bank Sta=105.739,121.58
XS Rating Curve= 0 ,0
Exp/Cntr=0.5,0.3

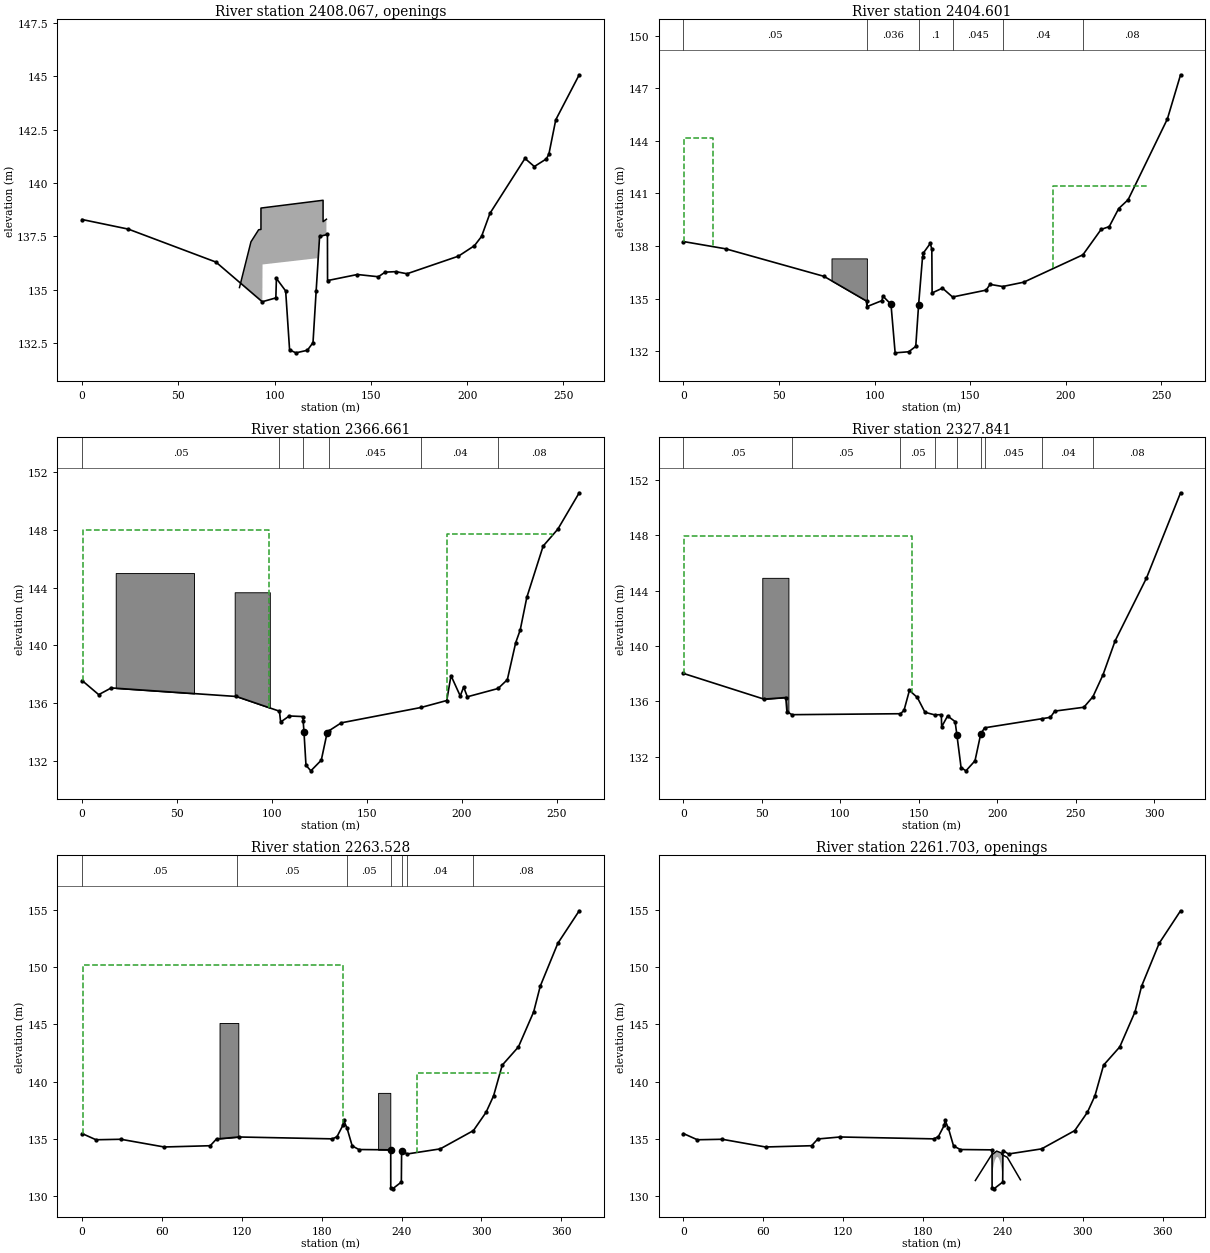
Type RM Length L Ch R = 4 ,2408.067,,,
BEGIN DESCRIPTION:
E143
END DESCRIPTION:
Bridge Culvert--1,0,-1,-1, 0
Deck Dist Width WeirC Skew NumUp NumDn MinLoCord MaxHiCord MaxSubmerge Is_Ogee
0.01,7.26,1.44,0, 15, 15, , , 0.95, 0, ,,,
  81.747  81.998  87.711  91.704  92.902  92.904  93.623  93.719 109.565 118.953
 122.099 122.491 125.178  125.18 126.913
 135.102 135.192 137.247 137.812 137.826 138.828 138.837 138.838 139.017 139.123
 139.159 139.163 139.193 138.192 138.306
 135.102  34.958  34.922  34.896  34.889  34.889  34.884 136.184 136.347 136.444
 136.476  34.302  34.291  34.291  34.284
  83.921  84.172  89.885  93.878  95.076  95.078  95.797  95.893 111.739 121.127
 124.273 124.665 127.352 127.354 129.087
 135.102 135.192 137.247 137.812 137.826 138.828 138.837 138.838 139.017 139.123
 139.159 139.163 139.193 138.192 138.306
 135.102  34.958  34.922  34.896  34.889  34.889  34.884 136.184 136.347 136.444
 136.476  34.302  34.291  34.291  34.284
BR Coef=-1 , 0 , 0 ,, 0 ,,,0.8,-1,,0,
WSPro=,,,, 1 ,,,, 0 ,,,, 0 ,,,,-1 ,-1 ,-1 , 0 , 0 , 0 , 0 , 0
BC Mult= 1 ,0,92,0,95
BC Mult= 3 ,92,125,95,127
BC Mult= 1 ,125,270,127,300
BC Design=,, 0 ,, 0 ,,,,,,
BC Use User HTab Curves=0
BC User HTab FreeFlow(D)= 0

Type RM Length L Ch R = 1 ,2404.601,38.9,37.94,36.981
XS GIS Cut Line= 4
529549.6555854814778283.50588924529613.020207835 4778261.0814195
529695.6856487164778213.58298648529786.1710687254778177.41624756
#Sta/Elev= 30
       0  138.26  22.116 137.845  73.531 136.275  95.761 134.867  95.921 134.546
 103.847 134.893 104.254 135.157 108.553 134.683 110.725 131.914 117.809 131.975
 121.508  132.28  123.01  134.67 125.062 137.389 125.508  137.61 129.097 138.152
 129.913  137.83  130.06  135.33 135.474 135.603 140.764 135.098  158.34 135.491
 160.347 135.818 166.972 135.696 177.964 135.942 208.937 137.505 218.434 138.949
 222.707 139.113 227.661 140.143 232.561 140.642 253.108 145.249 260.001 147.769
#Mann= 6 ,-1 , 0
       0     .05       0  95.921    .036       0  123.01      .1       0
 140.764    .045       0 166.972     .04       0 208.937     .08       0
#XS Ineff= 2 ,-1
     .53   15.33  144.16  193.48  243.44  141.45
Permanent Ineff=
       T       T
#Block Obstruct= 1 ,-1
   77.44   95.95   137.3
Bank Sta=108.553,123.01
XS Rating Curve= 0 ,0
Exp/Cntr=0.5,0.3

Type RM Length L Ch R = 1 ,2366.661,39.008,38.819,38.631
XS GIS Cut Line= 4
529578.5794422034778335.90569337529654.8680125274778290.33657359
529703.1352083784778242.42487484529797.5476656394778196.74215378
#Sta/Elev= 30
       0 137.557   8.756 136.578  15.366 137.044  81.223 136.451 103.917 135.431
 104.541 134.679 109.087 135.101 116.267  135.06 116.407 134.768  116.84  133.98
 117.887 131.684 120.466   131.3 125.944 132.037 129.046 133.954 130.224 134.094
 136.473 134.625 178.466 135.689 192.017 136.172 194.239 137.897 199.111 136.487
 200.904   137.1 202.855  136.43 219.038 137.004 223.908 137.615 228.309 140.176
 230.693  141.06 234.166 143.318 242.769 146.871 250.509 148.045 261.757 150.562
#Mann= 6 ,-1 , 0
       0     .05       0 103.917      .1       0 116.407    .036       0
 130.224    .045       0 178.466     .04       0 219.038     .08       0
#XS Ineff= 2 ,-1
     .26   98.59  147.97  192.16   247.4   147.7
Permanent Ineff=
       T       T
#Block Obstruct= 2 ,-1
   17.71   58.94     145   80.35   98.85  143.67
Bank Sta=116.84,129.046
XS Rating Curve= 0 ,0
Exp/Cntr=0.3,0.1

Type RM Length L Ch R = 1 ,2327.841,64.753,64.314,63.874
XS GIS Cut Line= 3
529583.1961944674778429.23099951529750.2803944674778245.43839951
529812.7171944674778217.29789951
#Sta/Elev= 30
       0 138.025  51.341 136.169  65.244 136.283  65.952 135.271  69.142 135.045
 138.347 135.114 140.595 135.355 144.052 136.797 149.083 136.288 153.975 135.216
  160.18 135.031  164.39 135.048 164.594 134.168 168.379 134.952 173.168 134.546
 174.279  133.61 176.969 131.226 180.065 130.988 185.848 131.714 189.491 133.644
 191.931 134.095 228.561 134.755 233.941 134.856 236.687 135.303 255.253 135.582
 261.009 136.341  267.44 137.926  275.17  140.38 295.155 144.917 316.874 151.075
#Mann= 9 ,-1 , 0
       0     .05       0  69.142     .05       0 138.347     .05       0
  160.18      .1       0 174.279    .036       0 189.491      .1       0
 191.931    .045       0 228.561     .04       0 261.009     .08       0
#XS Ineff= 1 ,-1
     .31  145.55  147.93
Permanent Ineff=
       T
#Block Obstruct= 1 ,-1
   50.26   66.92  144.93
Bank Sta=174.279,189.491
XS Rating Curve= 0 ,0
Exp/Cntr=0.5,0.3

Type RM Length L Ch R = 1 ,2263.528,3.407,3.494,3.58
XS GIS Cut Line= 4
529607.4170397664778520.69322683529745.9769152774778348.47100086
529766.701944586 4778319.3427709529841.901827482 4778230.1204445
#Sta/Elev= 30
       0 135.484  10.443 134.941  29.141 134.983  61.673 134.311  96.281 134.421
 100.994  135.01 117.644 135.183 188.118  135.02 191.503  135.21  195.88 136.191
 196.592 136.623 199.063 135.946  202.92 134.406 207.951 134.089  231.87  134.06
 231.892 130.745 233.274 130.659 239.852 131.249  240.05 133.999 244.216 133.701
 269.067 134.145 294.001 135.742 303.482 137.335 309.143 138.773 315.634 141.449
 327.808 143.043 339.264 146.102 344.214 148.345 357.401 152.081 373.477 154.919
#Mann= 7 ,-1 , 0
       0     .05       0 116.599     .05       0 199.063     .05       0
  231.87    .036       0  240.05      .1       0 244.216     .04       0
 294.001     .08       0
#XS Ineff= 2 ,-1
      .7   196.3  150.23  251.28   320.7  140.77
Permanent Ineff=
       F       T
#Block Obstruct= 2 ,-1
  103.26  117.36  145.13  222.38  231.54  139.03
Bank Sta=231.87,240.05
XS Rating Curve= 0 ,0
Exp/Cntr=0.5,0.3

Type RM Length L Ch R = 4 ,2261.703,,,
BEGIN DESCRIPTION:
E144
END DESCRIPTION:
Bridge Culvert--1,0,-1,-1, 0
Deck Dist Width WeirC Skew NumUp NumDn MinLoCord MaxHiCord MaxSubmerge Is_Ogee
0.01,3.29,1.44,0, 26, 26, , , 0.95, 0, ,,,
 219.306 219.448 231.266 231.672 231.727 232.409 233.345 234.054 234.913 235.055
 235.333 235.336 235.422 236.063 236.667 237.447 238.177 239.035 239.091 239.093
 239.836 239.993 242.008  243.29 253.001 253.165
 131.385 131.412 133.585 133.622 133.627 133.688 133.772 133.836 133.914 133.927
 133.952 133.952 133.948 133.918  133.89 133.854  133.82  133.78 133.777 133.665
 133.618 133.609 133.483 133.414 131.483  131.45
 131.385  70.973  70.855  70.851 131.667  132.29 132.873 133.163 133.371 133.387
 133.418 133.419 133.428 133.433 133.369 133.183 132.893  132.38 132.331 132.329
 131.667  70.623  70.592  70.572  70.423  131.45
 219.245 219.387 231.205 231.611 231.666 232.348 233.284 233.993 234.852 234.994
 235.272 235.275 235.361 236.002 236.606 237.386 238.116 238.974  239.03 239.032
 239.775 239.932 241.947 243.229  252.94 253.104
 131.385 131.412 133.585 133.622 133.627 133.688 133.772 133.836 133.914 133.927
 133.952 133.952 133.948 133.918  133.89 133.854  133.82  133.78 133.777 133.665
 133.618 133.609 133.483 133.414 131.483  131.45
 131.385  70.973  70.855  70.851 131.667  132.29 132.873 133.163 133.371 133.387
 133.418 133.419 133.428 133.433 133.369 133.183 132.893  132.38 132.331 132.329
 131.667  70.623  70.592  70.572  70.423  131.45
BR Coef=-1 , 0 , 0 ,, 0 ,,,0.8,0,,0,
WSPro=,,,, 1 ,,,, 0 ,,,, 0 ,,,,-1 ,-1 ,-1 , 0 , 0 , 0 , 0 , 0
BC Mult= 1 ,0,231,0,231
BC Mult= 3 ,231,240,231,239.5
BC Mult= 1 ,240,400,239.5,400
BC Design=,, 0 ,, 0 ,,,,,,
BC Use User HTab Curves=0
BC User HTab FreeFlow(D)= 0

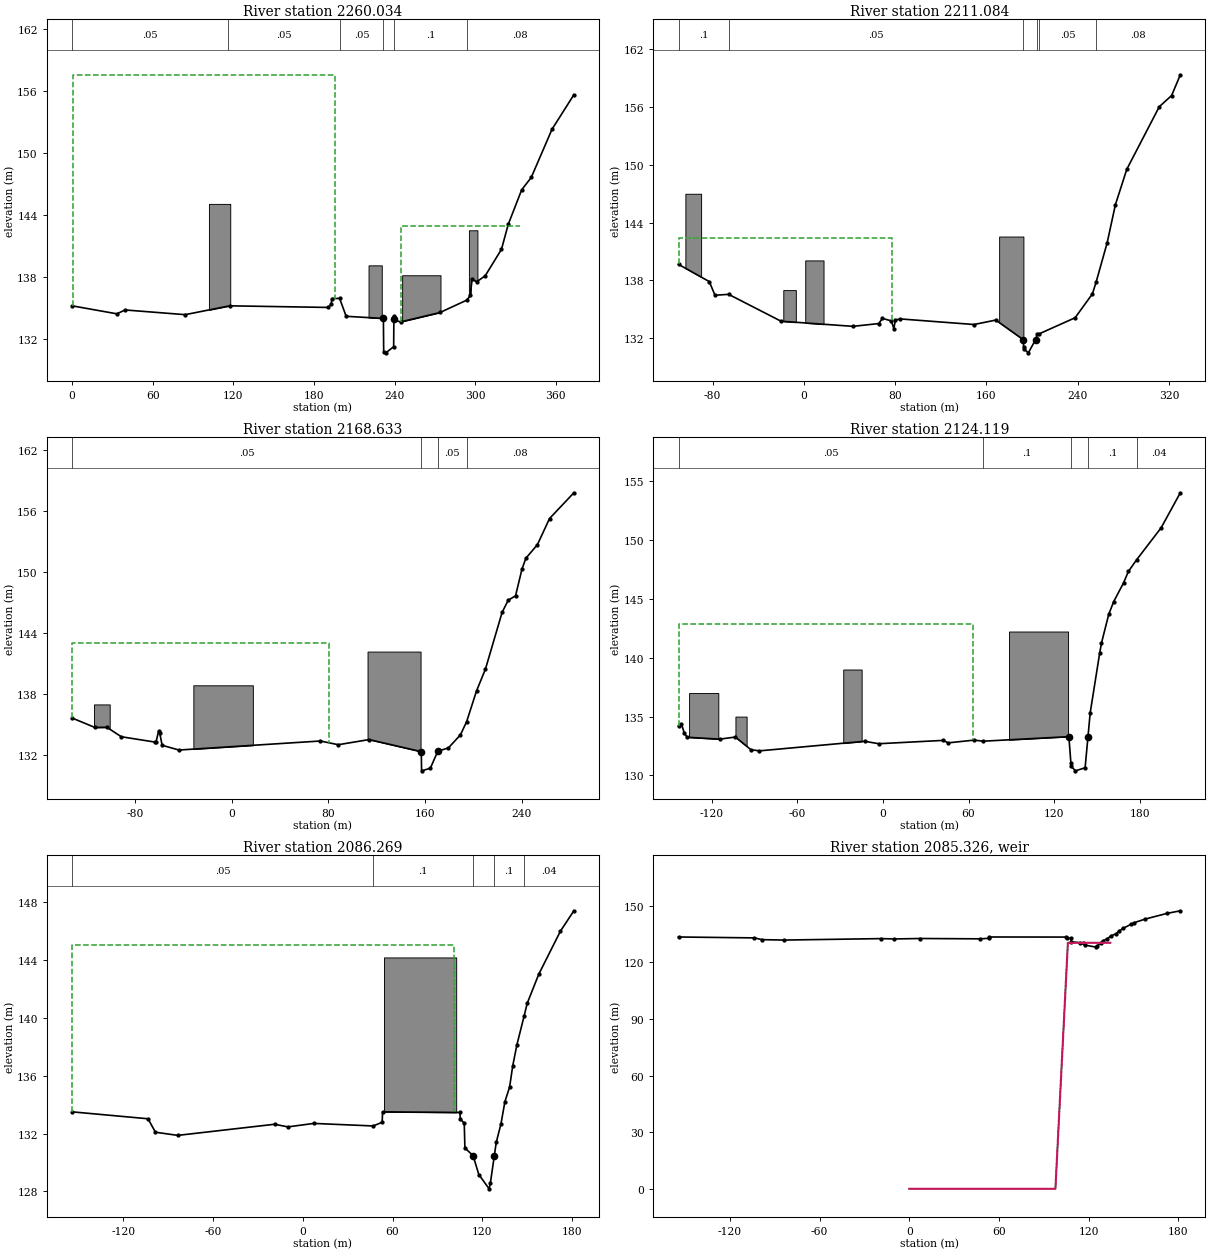
Type RM Length L Ch R = 1 ,2260.034,48.932,48.95,48.968
XS GIS Cut Line= 4
529610.2081554454778522.90290095529748.111328115 4778350.8367256
529769.9699234444778321.59138621529844.6929431614778232.33011863
#Sta/Elev= 30
       0 135.195  33.356  134.42  39.464 134.794  84.152 134.338 117.255 135.195
 190.459 135.039 192.781 135.344 193.373 135.897 199.113 135.914 203.974 134.179
  231.69  133.97 231.907 130.725 233.468 130.636 239.332 131.228  239.48 133.959
  239.52  134.22 239.917 133.783  244.73 133.643 273.847 134.548 293.777  135.75
 296.423 136.217 297.384 137.751 301.297 137.541 307.447 138.105 319.554 140.672
 324.587  143.09 334.604 146.445 341.725 147.643 357.189 152.321  373.43 155.658
#Mann= 6 ,-1 , 0
       0     .05       0 116.174     .05       0 199.113     .05       0
  231.69    .036       0  239.52      .1       0 293.777     .08       0
#XS Ineff= 2 ,-1
      .7  195.59   157.6  244.93  333.39  142.92
Permanent Ineff=
       F       T
#Block Obstruct= 4 ,-1
  101.85  117.71  145.08  220.62  230.48  139.12  245.64  274.19  138.16
  295.33  301.67  142.52
Bank Sta=231.69,239.48
XS Rating Curve= 0 ,0
Exp/Cntr=0.5,0.3

Type RM Length L Ch R = 1 ,2211.084,42.507,42.451,42.394
XS GIS Cut Line= 3
529612.414350614 4778611.4976077 529678.571713414778523.87884459
 529877.378235984778260.57963087
#Sta/Elev= 30
 -109.79139.6684  -82.84137.8831  -77.85136.4669  -65.87136.5584  -19.96133.7704
  43.067 133.238  65.656 133.526  68.853 134.064  76.734 133.803  78.848     133
  80.276 133.905  84.701 134.006 149.121 133.428 168.206 133.889 192.356 131.849
 192.594  131.09  193.27 130.844 196.734 130.488  203.17  131.87 204.511 132.421
 205.939 132.444 237.721  134.13 252.912 136.614 256.121 137.824 265.787 141.898
 273.046  145.87 283.041 149.546 311.518  156.04  322.28 157.191 329.925 159.347
#Mann= 6 ,-1 , 0
 -109.79      .1       0  -65.87     .05       0 192.356    .036       0
 204.511     .01       0 205.939     .05       0 256.121     .08       0
#XS Ineff= 2 , 0
            77.4  142.36
Permanent Ineff=
       T       T
#Block Obstruct= 4 ,-1
  -103.8     -90     147     -18      -7     137    1.23   17.27  140.08
  171.15  192.42  142.56
Bank Sta=192.356,203.17
XS Rating Curve= 0 ,0
Exp/Cntr=0.3,0.1

Type RM Length L Ch R = 1 ,2168.633,42.441,44.515,46.588
XS GIS Cut Line= 3
529661.7666042954778623.86138274529739.7277431864778517.17005103
529906.7161756294778288.64314018
#Sta/Elev= 30
 -132.14135.6612 -113.26134.7335 -103.33134.7496  -91.41133.8189  -63.59133.2948
  -62.59133.3269  -60.61 134.358  -59.61134.1917  -57.63132.9781  -43.72132.5116
   73.27 133.399  88.147 133.035 113.635  133.54  156.79  132.35 157.042 130.464
 164.285 130.718 170.443 132.389 179.313 132.728 189.178 134.001 194.341 135.309
 202.535  138.34 209.876 140.472 223.681  146.06  228.69  147.25 234.788 147.686
  240.14 150.326 243.326 151.381 252.902 152.724 262.901 155.289 283.036 157.824
#Mann= 4 ,-1 , 0
 -132.14     .05       0  156.79    .036       0 170.443     .05       0
 194.341     .08       0
#XS Ineff= 2 , 0
           80.62  143.08
Permanent Ineff=
       T       T
#Block Obstruct= 3 ,-1
    -114    -101     137  -31.79   17.44  138.88  112.33  156.21   142.2
Bank Sta=156.79,170.443
XS Rating Curve= 0 ,0
Exp/Cntr=0.3,0.1

Type RM Length L Ch R = 1 ,2124.119,34.516,37.849,41.182
XS GIS Cut Line= 4
529684.3507497754778622.78193563529769.6269944674778507.49679951
529823.3064783884778434.92739131529933.1935944674778391.41719951
#Sta/Elev= 30
-143.397134.2026-141.405134.3982-139.414 133.618-137.422133.2447-114.519133.0825
-103.565133.2624 -92.611132.1841 -86.636 132.088 -12.946132.9028  -2.987132.6945
  42.212 132.977  45.644 132.767   63.95 133.002  70.042 132.908 130.314 133.297
 131.701 131.076 131.886  130.78 134.913  130.39  141.69 130.651 143.708 133.294
 145.257 135.323 151.861 140.362 153.147  141.24 158.243  143.68 161.714 144.766
 168.709 146.377 172.019 147.331 177.853 148.333 194.979 151.042 208.454 154.019
#Mann= 5 ,-1 , 0
-143.397     .05       0  70.042      .1       0 131.701    .036       0
 143.708      .1       0 177.853     .04       0
#XS Ineff= 2 , 0
           62.86   142.9
Permanent Ineff=
       T       T
#Block Obstruct= 4 ,-1
    -136  -115.5     137  -103.5  -95.65     135   -27.9     -15     139
   88.33  129.74  142.23
Bank Sta=130.314,143.708
XS Rating Curve= 0 ,0
Exp/Cntr=0.3,0.1

Type RM Length L Ch R = 1 ,2086.269,66.66,63.514,60.368
XS GIS Cut Line= 5
529681.8659226534778636.80246378529782.1381811544778519.44228323
529846.1363416434778444.53786019529878.8700924034778463.57400201
529923.7200445014778462.28190362
#Sta/Elev= 30
-154.363133.4989-103.572133.0205 -98.593132.0899 -83.655131.8726 -18.922132.6407
  -9.959132.4589   7.297 132.699  46.998 132.524  53.044 132.778  53.315   133.5
 105.039 133.455 105.316     133 107.938 132.714 108.388     131 113.852 130.473
 117.685 129.168 124.586 128.178 125.392 128.558  128.02  130.44  129.34 131.386
 132.542 132.686 135.116 134.192 138.289 135.218 140.381 136.682  143.16 138.133
 148.068 140.153 150.024  140.99 157.771 143.006 172.253 145.983 181.256 147.394
#Mann= 5 ,-1 , 0
-154.363     .05       0  46.998      .1       0 113.852    .036       0
  128.02      .1       0 148.068     .04       0
#XS Ineff= 2 , 0
          101.32  145.03
Permanent Ineff=
       T       T
#Block Obstruct= 1 ,-1
   54.27  102.56  144.17
Bank Sta=113.852,128.02
XS Rating Curve= 0 ,0
Exp/Cntr=0.3,0.1

Type RM Length L Ch R = 5 ,2085.326,,,
BEGIN DESCRIPTION:
E145
END DESCRIPTION:
IW Pilot Flow=0
#Inline Weir SE= 14
       0       0   97.71       0  106.04  130.41  109.73  130.35  110.12  130.39
  110.21  130.38  112.68  130.41  116.42   130.4  116.48  130.64  117.29  130.66
  117.31  130.41  122.81  130.42  124.56  130.43  134.42  130.43
IW Dist,WD,Coef,Skew,MaxSub,Min_El,Is_Ogee,SpillHt,DesHd
0.1,1.6,1.7,0,0.98,, 0 ,,,0,0,

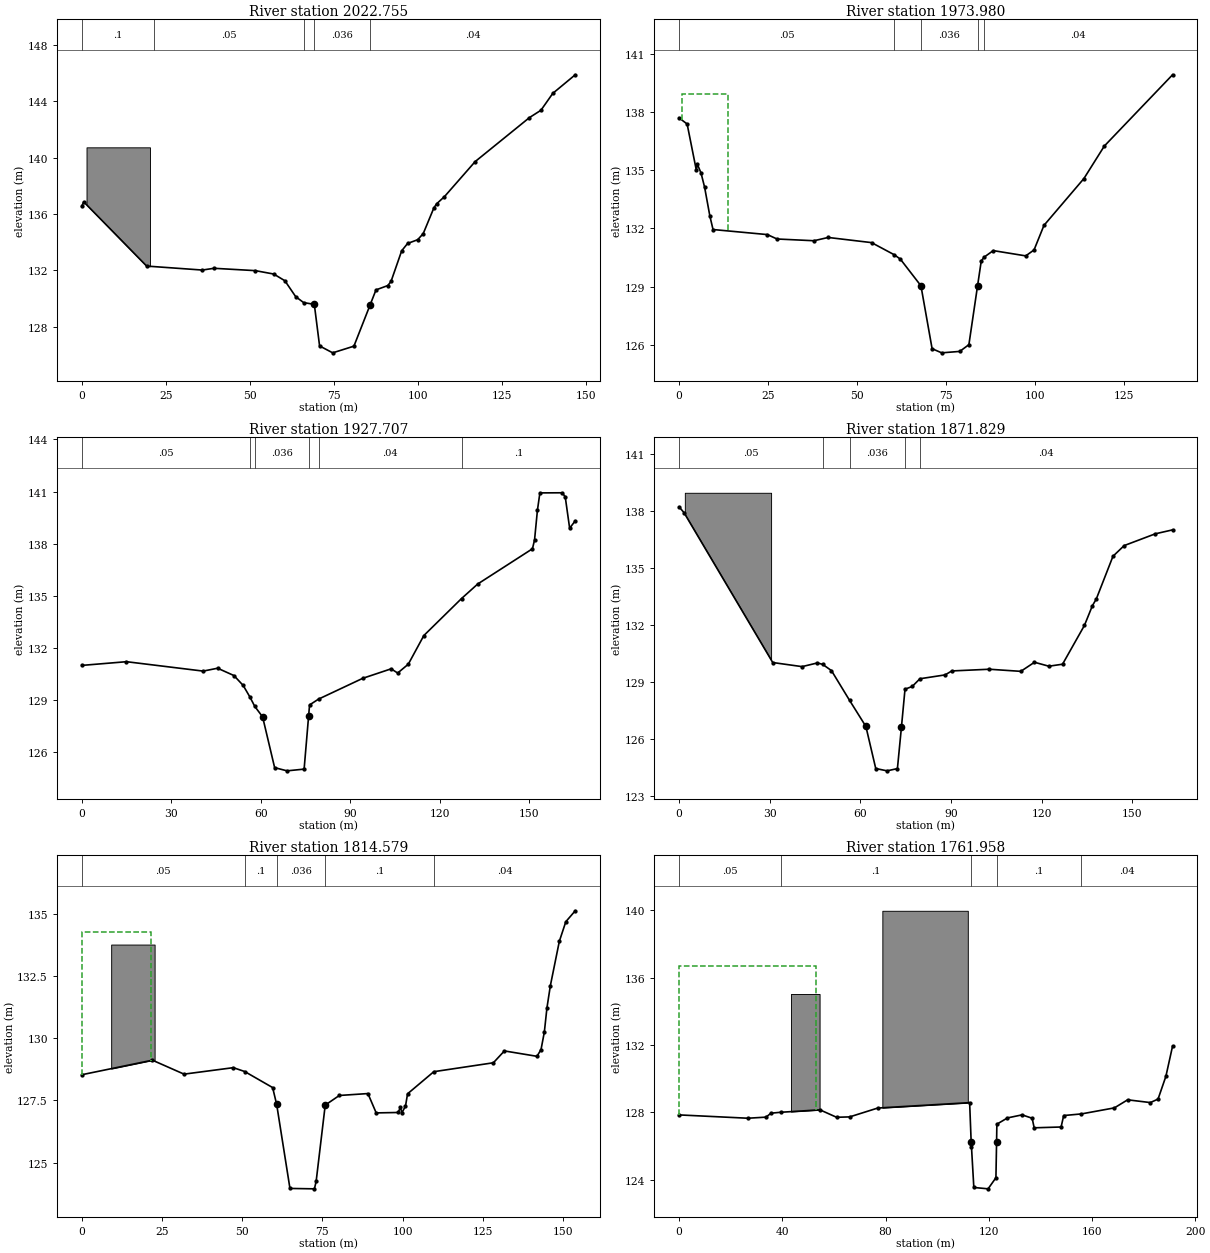
Type RM Length L Ch R = 1 ,2022.755,48.269,48.776,49.283
XS GIS Cut Line= 2
529797.3614176824778537.96532654529936.694459706 4778491.3144837
#Sta/Elev= 30
       0 136.549     .58 136.859   19.31   132.3  35.893 132.018   39.36 132.143
  51.681 131.976  57.157 131.735  60.477 131.258  63.706 130.126  66.077 129.705
  69.239 129.584  70.809 126.631  74.718 126.141  81.032 126.615   85.84 129.535
  87.607  130.61  91.125 130.917  92.086 131.212  95.257 133.385  97.006 133.904
 100.013 134.171  101.67 134.605 104.834 136.427 105.656  136.72 107.998 137.232
 117.125 139.716 133.307 142.842 136.713  143.36 140.256 144.562 146.935  145.88
#Mann= 5 ,-1 , 0
       0      .1       0  21.523     .05       0  66.077      .1       0
  69.239    .036       0   85.84     .04       0
#Block Obstruct= 1 ,-1
    1.41    20.3  140.73
Bank Sta=69.239,85.84
XS Rating Curve= 0 ,0
Exp/Cntr=0.3,0.1

Type RM Length L Ch R = 1 ,1973.980,46.449,46.273,46.097
XS GIS Cut Line= 2
529808.7215758454778574.23176031529945.027096458 4778548.7294371
#Sta/Elev= 30
       0   137.7   2.263 137.381   4.833 135.011   5.137 135.303   6.154 134.863
   7.171 134.122    8.65 132.634   9.539  131.94  24.814 131.679  27.518 131.452
  37.903 131.362  41.896 131.531  54.091 131.265  60.474 130.638  62.172 130.415
  67.963 129.039    71.1 125.793  73.794  125.58  78.876 125.654  81.438 126.002
   83.86  129.02  84.908 130.315  85.718 130.516  88.284 130.853  97.414 130.581
   99.75 130.888 102.532 132.154 113.769 134.572 119.497 136.246  138.67 139.922
#Mann= 5 ,-1 , 0
       0     .05       0  60.474      .1       0  67.963    .036       0
   83.86      .1       0  85.718     .04       0
#XS Ineff= 1 ,-1
     .74   13.81  138.95
Permanent Ineff=
       T
Bank Sta=67.963,83.86
XS Rating Curve= 0 ,0
Exp/Cntr=0.3,0.1

Type RM Length L Ch R = 1 ,1927.707,56.085,55.878,55.671
XS GIS Cut Line= 2
529824.1491944674778621.81749951529985.0379433774778583.64553013
#Sta/Elev= 30
       0 130.976  14.979  131.19  40.667 130.648  45.522 130.814  50.978 130.392
  54.083 129.822   56.32  129.16   57.98  128.61  60.593  128.01  64.625 125.082
  68.779 124.898  74.504 124.997      76  128.04  76.329 128.697  79.337 129.033
  94.165 130.233 103.667 130.779 105.851 130.536 109.414 131.046 114.623 132.698
 127.257 134.832 132.679 135.669 151.016   137.7  151.72 138.211 152.677 139.916
 153.507 140.921  160.97 140.928 161.998 140.697 163.476 138.885 165.355 139.311
#Mann= 6 ,-1 , 0
       0     .05       0   56.32      .1       0   57.98    .036       0
      76      .1       0  79.337     .04       0 127.257      .1       0
Bank Sta=60.593,76
XS Rating Curve= 0 ,0
Exp/Cntr=0.3,0.1

Type RM Length L Ch R = 1 ,1871.829,58.033,57.25,56.467
XS GIS Cut Line= 2
529844.375207399 4778678.0985044530000.9067084894778631.49081025
#Sta/Elev= 30
       0 138.208   1.604 137.912  30.992 130.035  40.703  129.82  45.765 130.013
  47.495 129.941  50.425 129.612  56.443 128.043  61.822 126.679  65.087 124.469
   68.82 124.347   72.26 124.464   73.59  126.64  74.771 128.634  77.154 128.778
  79.711 129.183   88.05 129.386  90.248 129.593 102.665 129.683 113.099 129.572
 117.624 130.049 122.378 129.842 126.914 129.947  134.15 131.982 136.795  133.02
 138.086 133.373 143.606 135.617 147.313 136.177 157.636 136.796 163.324 137.002
#Mann= 5 ,-1 , 0
       0     .05       0  47.495      .1       0  56.443    .036       0
  74.771      .1       0  79.711     .04       0
#Block Obstruct= 1 ,-1
     1.9   30.45  138.95
Bank Sta=61.822,73.59
XS Rating Curve= 0 ,0
Exp/Cntr=0.3,0.1

Type RM Length L Ch R = 1 ,1814.579,53.13,52.621,52.112
XS GIS Cut Line= 2
529873.3950944674778743.17339951530008.111948234  4778668.995813
#Sta/Elev= 30
       0 128.537  22.018 129.123  31.868 128.561  47.233 128.822  50.766 128.667
   59.48  128.02   60.74  127.34  64.877 123.958  72.508 123.942   73.04 124.242
  75.869 127.314  80.262 127.702  89.175 127.779  91.755     127  98.604 127.017
   99.32 127.233  99.746     127 100.887 127.274 101.529 127.769 109.713  128.66
 128.275 129.019 131.708 129.496 141.861 129.279 143.126 129.552 144.159 130.256
 144.965 131.226 146.034 132.125 148.833 133.912 150.854 134.701 153.789  135.14
#Mann= 5 ,-1 , 0
       0     .05       0  50.766      .1       0   60.74    .036       0
  75.869      .1       0 109.713     .04       0
#XS Ineff= 2 , 0
           21.43  134.28
Permanent Ineff=
       T       T
#Block Obstruct= 1 ,-1
    9.16    22.7  133.78
Bank Sta=60.74,75.869
XS Rating Curve= 0 ,0
Exp/Cntr=0.3,0.1

Type RM Length L Ch R = 1 ,1761.958,37.103,37.383,37.663
XS GIS Cut Line= 3
529855.8072833214778779.22840679529947.1439877444778765.29228557
530026.4090317014778706.23899897
#Sta/Elev= 30
       0 127.852  26.648 127.655   33.69 127.719   35.59 127.953  39.415 128.009
  54.588 128.153  61.042 127.711  66.103 127.734      77  128.26   112.6  128.58
  113.19  126.25 113.317 125.951 114.224 123.545 119.748 123.463 122.788 124.122
 123.043 126.264 123.151   127.3  127.25 127.673 132.924 127.855 136.821 127.654
 137.614 127.086 148.044 127.134 149.048 127.814 155.936 127.911 168.697 128.269
 173.828 128.748 182.635 128.584 185.617 128.792  188.66 130.145 191.239 131.934
#Mann= 5 ,-1 , 0
       0     .05       0  39.415      .1       0 113.317    .036       0
 123.151      .1       0 155.936     .04       0
#XS Ineff= 2 , 0
           53.22  136.71
Permanent Ineff=
       T       T
#Block Obstruct= 2 ,-1
   43.35   54.45  135.03   78.77  111.89  139.97
Bank Sta=113.19,123.043
XS Rating Curve= 0 ,0
Exp/Cntr=0.3,0.1