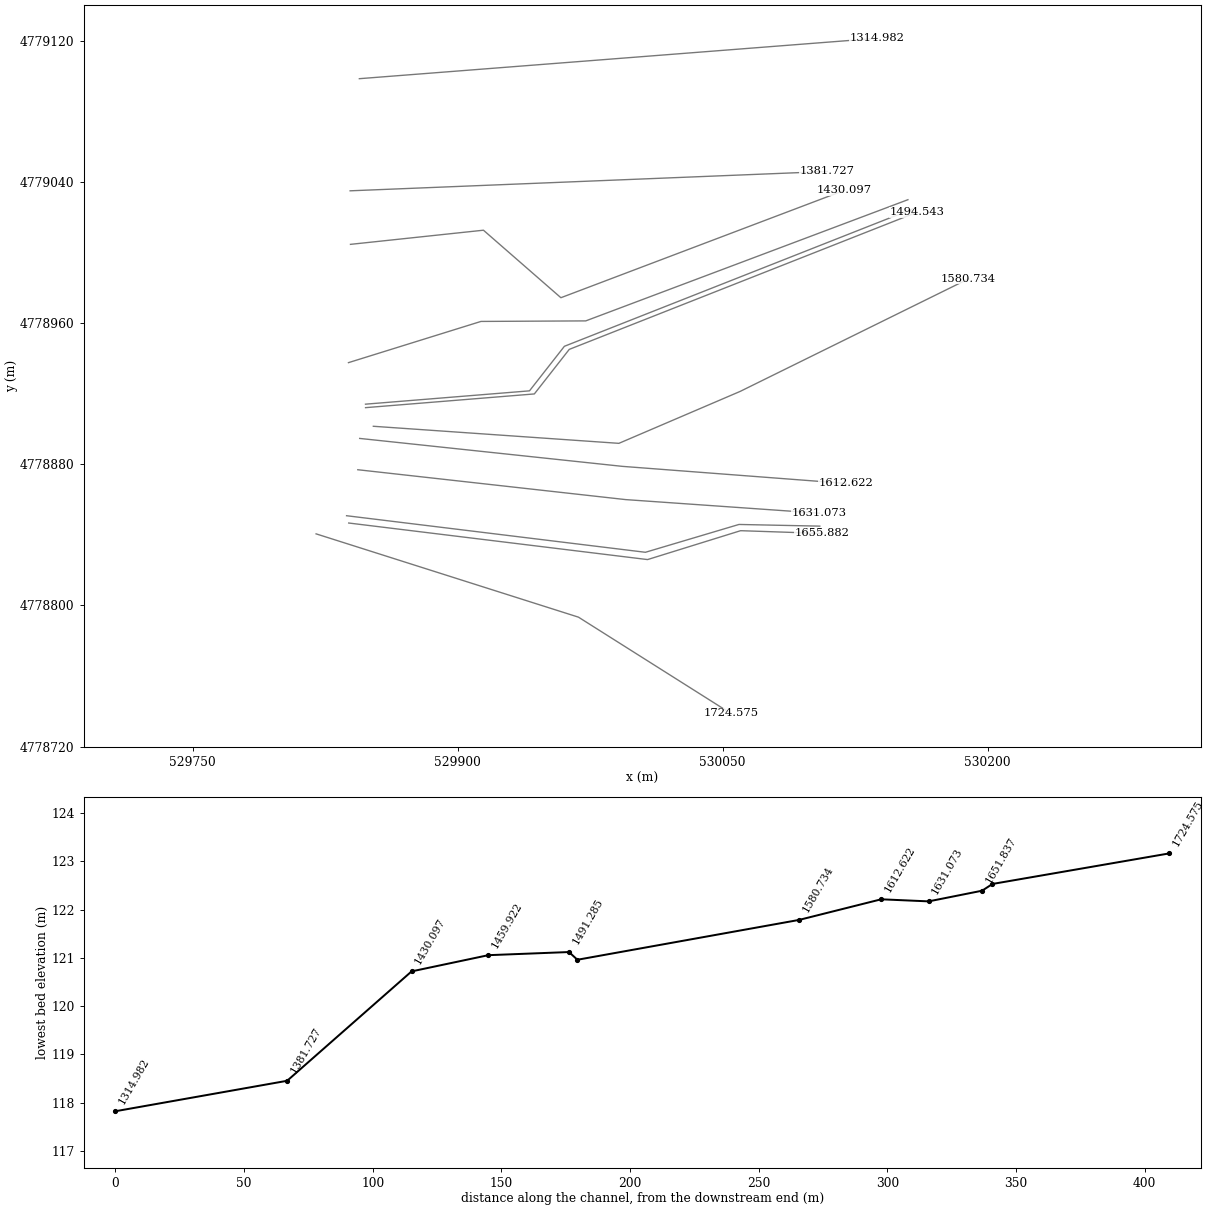
HEC-RAS study Durango.prj: Durango

--- Durango.g18 (geometry) --- (continued)

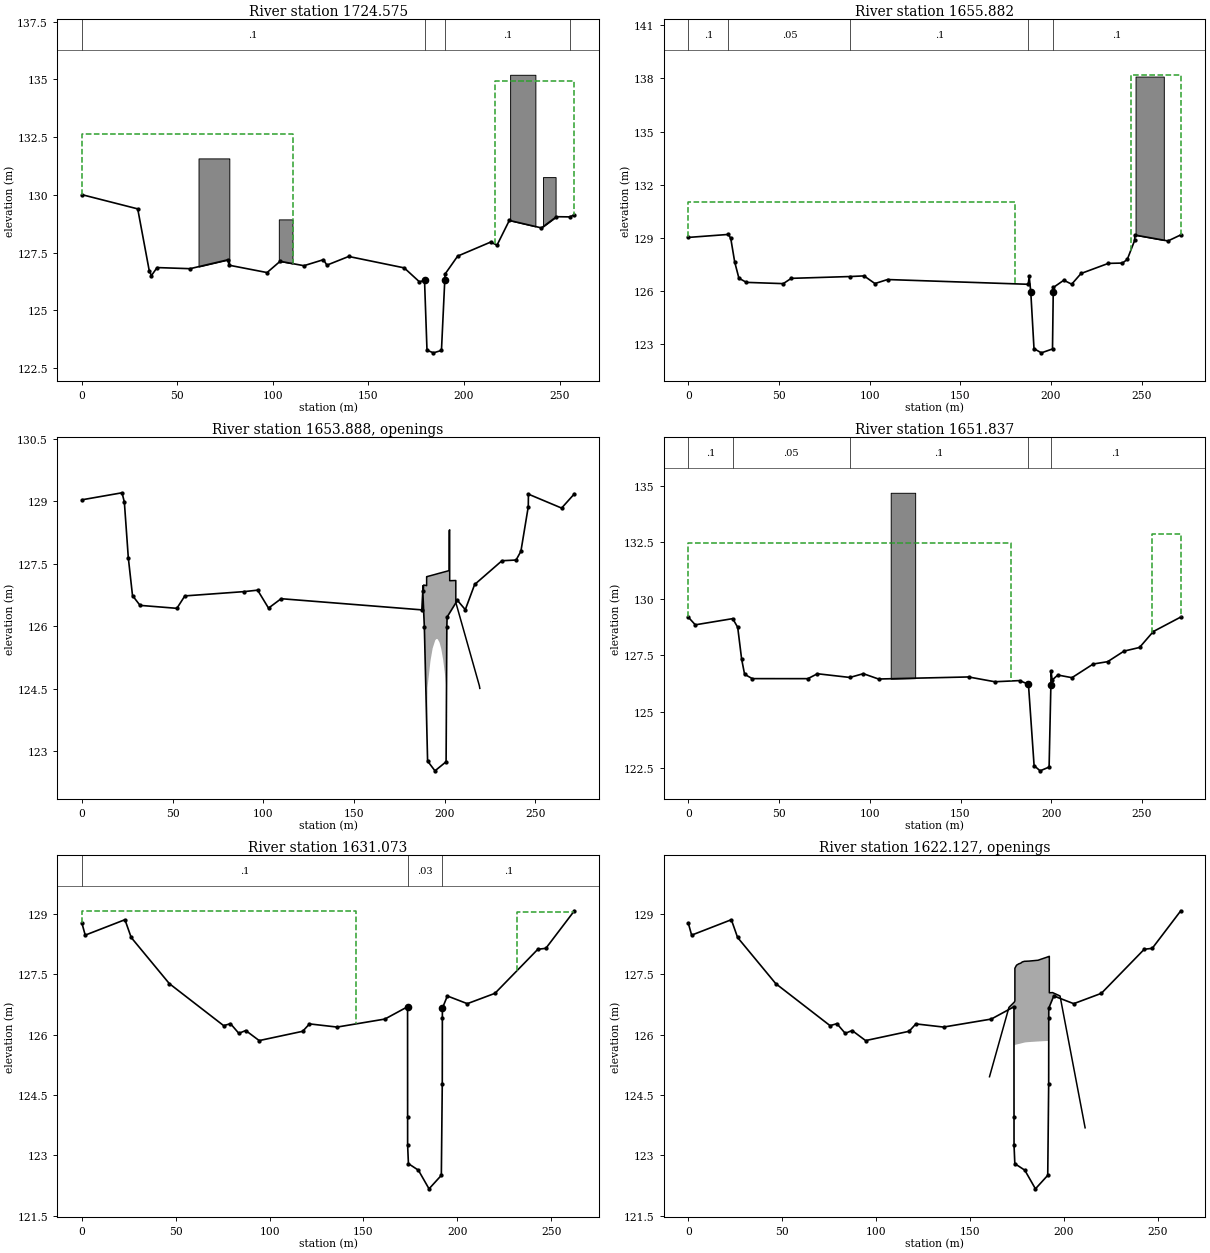
Type RM Length L Ch R = 1 ,1724.575,65.441,68.693,71.939
XS GIS Cut Line= 3
529819.9011847274778840.49945452529968.3692944674778793.29869951
530054.5494944674778738.77639951
#Sta/Elev= 30
       0 130.011  29.238 129.395  35.281 126.713  36.409 126.506  39.364 126.854
  56.633 126.806  76.464 127.191  77.015 126.957  96.937 126.638 103.746 127.125
 116.228 126.935 126.448 127.196 128.227 126.959  139.66 127.335 168.702 126.841
  176.64  126.24  179.34   126.3 180.632 123.275  184.02 123.163 188.202 123.267
  189.94  126.31 190.106 126.575 196.678  127.35 213.927 127.957 217.282 127.825
 223.716 128.895  240.54 128.571 248.383 129.056 255.398 129.048  257.77 129.142
#Mann= 4 ,-1 , 0
       0      .1       0  179.34    .036       0  189.94      .1       0
 255.398      .1       0
#XS Ineff= 2 , 0
          110.75  132.64  216.21          134.92
Permanent Ineff=
       T       T
#Block Obstruct= 4 ,-1
   61.06   77.18  131.58  103.08  110.22  128.94  224.14  237.36   135.2
  241.32  247.93  130.77
Bank Sta=179.34,189.94
XS Rating Curve= 0 ,0
Exp/Cntr=0.5,0.3

Type RM Length L Ch R = 1 ,1655.882,4.091,4.045,4.005
XS GIS Cut Line= 4
529838.3538522624778846.64582418530007.4619842364778825.92736592
530060.1284100944778842.29835514530106.1406141114778840.74842604
#Sta/Elev= 30
       0 129.034   22.16 129.203  23.436 128.978  25.607 127.647  27.928 126.736
  32.077 126.501  52.383  126.43  56.789 126.728  89.426 126.831  96.917 126.866
 102.925 126.435 109.876 126.661 187.451 126.393 187.976 126.843 188.846 125.974
  190.63 122.764   194.7  122.53  200.83 122.748  201.24  125.98  201.38  126.22
 207.061 126.622 211.415 126.398 216.573 127.002 231.623 127.572 239.416 127.589
 242.077 127.799 246.142 128.871 246.218  129.17 264.517 128.836 271.563 129.178
#Mann= 5 ,-1 , 0
       0      .1       0   22.16     .05       0  89.426      .1       0
 187.451    .036       0  201.38      .1       0
#XS Ineff= 2 , 0
          180.26  131.02  243.96           138.2
Permanent Ineff=
       T       T
#Block Obstruct= 1 ,-1
  246.61   262.2   138.1
Bank Sta=188.846,201.24
XS Rating Curve= 0 ,0
Exp/Cntr=0.5,0.3

Type RM Length L Ch R = 4 ,1653.888,,,
BEGIN DESCRIPTION:
E146
END DESCRIPTION:
Bridge Culvert--1,0,-1,-1, 0
Deck Dist Width WeirC Skew NumUp NumDn MinLoCord MaxHiCord MaxSubmerge Is_Ogee
0.01,3.85,1.44,0, 31, 33, , , 0.95, 0, ,,,
     188 188.203 188.489 189.918 190.094 190.099 190.312 190.399 190.571 192.236
 193.429 194.867 195.511 196.233 197.249 198.152 199.037 199.243 200.168  200.95
 201.188   201.3 201.664 202.451 202.463 202.819 202.821 206.187 206.192 219.173
 219.417
 126.968 126.816  126.99 126.976 126.974 127.189 127.192 127.193 127.195 127.214
 127.228 127.245 127.253 127.262 127.274 127.284 127.295 127.297 127.308 127.317
  127.32 127.321 127.326 127.335 128.294 128.314 127.093 127.098 126.571 124.572
 124.509
  28.372  28.372  28.372  28.372  70.502  71.657 122.769 123.656 124.526 125.172
 125.471 125.665 125.695 125.689 125.606 125.459 125.237 125.185 124.865 124.526
 123.848 123.084  27.629  27.629  27.629  27.629  27.629  27.629  27.629  27.629
 124.509
 176.427 177.048 182.071 186.853 187.139 188.568 188.744 188.749 188.962 189.049
 189.221 190.886 192.079 193.517 194.161 194.883 195.899 196.802 197.687 197.893
 198.818   199.6 199.838  199.95 200.314 201.101 201.113 201.469 201.471 204.837
 204.842 217.823 218.067
 124.085 124.343 126.428 126.816  126.99 126.976 126.974 127.189 127.192 127.193
 127.195 127.214 127.228 127.245 127.253 127.262 127.274 127.284 127.295 127.297
 127.308 127.317  127.32 127.321 127.326 127.335 128.294 128.314 127.093 127.098
 126.571 124.572 124.509
 124.085  28.372  28.372  28.372  28.372  28.372  70.502  71.657 122.769 123.656
 124.526 125.172 125.471 125.665 125.695 125.689 125.606 125.459 125.237 125.185
 124.865 124.526 123.848 123.084  27.629  27.629  27.629  27.629  27.629  27.629
  27.629  27.629 124.509
BR Coef=-1 , 0 , 0 ,, 0 ,,,0.8,-1,,0,
WSPro=,,,, 1 ,,,, 0 ,,,, 0 ,,,,-1 ,-1 ,-1 , 0 , 0 , 0 , 0 , 0
BC Mult= 1 ,0,187,0,187
BC Mult= 3 ,187,206,187,204
BC Mult= 1 ,206,280,204,280
BC Design=,, 0 ,, 0 ,,,,,,
BC Use User HTab Curves=0
BC User HTab FreeFlow(D)= 0

Type RM Length L Ch R = 1 ,1651.837,22.09,20.764,19.438
XS GIS Cut Line= 4
529837.1442041884778850.77781442530006.2523361624778830.05935616
530059.2000958634778845.83145788530104.9309660384778844.88041627
#Sta/Elev= 30
       0  129.19   3.878 128.849  24.477 129.123  27.241  128.74  29.406 127.332
  31.038 126.661  35.273 126.469  65.914 126.468  71.155 126.685  89.033 126.521
  96.454 126.688  104.82 126.452 154.434 126.543  168.88 126.331 182.583 126.382
 187.428 126.217 190.535 122.624 193.832  122.39 198.807 122.557  199.79   126.2
   199.9  126.79 200.494 126.406 203.597 126.628 211.412 126.511 223.098 127.115
 231.071 127.219 240.084 127.686 248.625 127.847 256.219 128.552 271.361 129.194
#Mann= 5 ,-1 , 0
       0      .1       0  24.477     .05       0  89.033      .1       0
 187.428    .036       0   199.9      .1       0
#XS Ineff= 2 , 0
          177.62  132.49  255.33          132.88
Permanent Ineff=
       T       T
#Block Obstruct= 1 ,-1
  111.54  125.02  134.69
Bank Sta=187.428,199.79
XS Rating Curve= 0 ,0
Exp/Cntr=0.5,0.3

Type RM Length L Ch R = 1 ,1631.073,18.474,18.451,18.429
XS GIS Cut Line= 3
529843.4958169434778876.84074735529995.0629242944778859.91362009
530104.674782246 4778852.2178146
#Sta/Elev= 30
       0 128.783   1.787 128.478  22.953 128.862  26.284  128.42  46.615 127.272
  75.556 126.227  79.176 126.277  83.628 126.036  87.304 126.106  94.477 125.856
 117.645 126.087 121.273 126.271  135.98 126.192 161.429 126.391  173.52 126.697
 173.546  123.96 173.554 123.252 173.979 122.795 179.283 122.633 184.958 122.169
 191.511 122.505  192.01 124.778 192.054 126.411 192.075 126.662 194.723 126.965
 205.347 126.774 220.072 127.031 242.925 128.127 247.182  128.15 262.391 129.084
#Mann= 3 ,-1 , 0
       0      .1       0 173.546     .03       0  192.01      .1       0
#XS Ineff= 2 , 0
           145.9  129.08  231.81          129.05
Permanent Ineff=
       T       T
Bank Sta=173.52,192.075
XS Rating Curve= 0 ,0
Exp/Cntr=0.5,0.3

Type RM Length L Ch R = 4 ,1622.127,,,
BEGIN DESCRIPTION:
E147
END DESCRIPTION:
Bridge Culvert--1,0,-1,-1, 0
Deck Dist Width WeirC Skew NumUp NumDn MinLoCord MaxHiCord MaxSubmerge Is_Ogee
0.01,18.25,1.44,0, 35, 35, , , 0.95, 0, ,,,
 160.486 160.867 170.845 173.146 173.473 173.732 173.893 174.004 174.008 174.704
 174.916 176.125 177.062 177.956 179.156 179.418 180.356 181.105 181.556 186.356
 187.556 187.812 188.755 189.955 191.155  192.06 192.296 192.355 192.358 194.068
 195.154 196.915 198.068 210.907  211.42
 124.957 125.021 126.682 126.788 126.803 126.815 126.832 126.844 127.655 127.716
 127.732 127.766  127.78 127.812 127.828 127.828  127.83 127.832 127.833 127.854
 127.874 127.878 127.893 127.912 127.931 127.947 127.951 127.952 127.044  127.05
 127.027  126.99 126.965 123.813 123.687
 124.957   7.383   7.125   7.066 125.677  125.72 125.747 125.748 125.748 125.756
 125.759 125.772 125.783 125.793 125.807  125.81 125.814 125.817 125.819 125.834
 125.837 125.838  125.84 125.843 125.846 125.848   6.623   6.622   6.622   6.593
   6.575   6.545   6.526    6.31 123.687
 160.611 160.992  170.97 173.271 173.598 173.857 174.018 174.129 174.133 174.829
 175.041  176.25 177.187 178.081 179.281 179.543 180.481  181.23 181.681 186.481
 187.681 187.937  188.88  190.08  191.28 192.185 192.421  192.48 192.483 194.193
 195.279  197.04 198.193 211.032 211.545
 124.957 125.021 126.682 126.788 126.803 126.815 126.832 126.844 127.655 127.716
 127.732 127.766  127.78 127.812 127.828 127.828  127.83 127.832 127.833 127.854
 127.874 127.878 127.893 127.912 127.931 127.947 127.951 127.952 127.044  127.05
 127.027  126.99 126.965 123.813 123.687
 124.957   7.383   7.125   7.066 125.677  125.72 125.747 125.748 125.748 125.756
 125.759 125.772 125.783 125.793 125.807  125.81 125.814 125.817 125.819 125.834
 125.837 125.838  125.84 125.843 125.846 125.848   6.623   6.622   6.622   6.593
   6.575   6.545   6.526    6.31 123.687
BR Coef=-1 , 0 , 0 ,, 0 ,,,0.8,-1,,0,
WSPro=,,,, 1 ,,,, 0 ,,,, 0 ,,,,-1 ,-1 ,-1 , 0 , 0 , 0 , 0 , 0
BC Mult= 1 ,0,173,0,173
BC Mult= 3 ,173,194,173,197.5
BC Mult= 1 ,194,280,197.5,300
BC Design=,, 0 ,, 0 ,,,,,,
BC Use User HTab Curves=0
BC User HTab FreeFlow(D)= 0

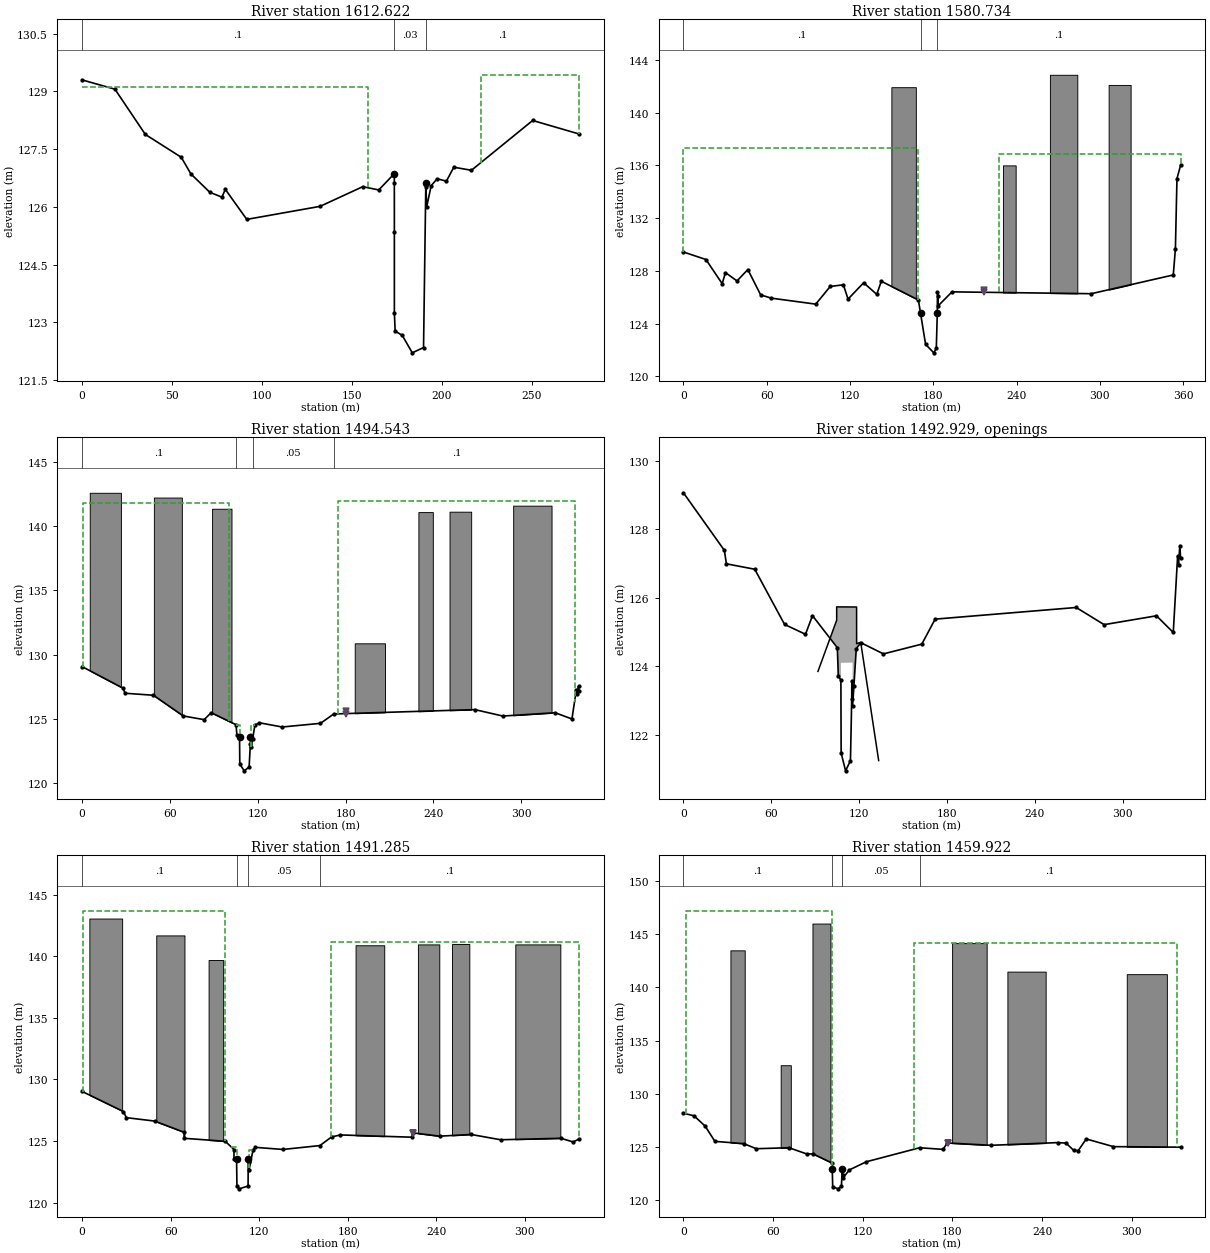
Type RM Length L Ch R = 1 ,1612.622,30.114,31.888,33.661
XS GIS Cut Line= 3
529844.5761895394778894.58007643529993.1931765294778878.75104823
530119.8254021314778869.07775321
#Sta/Elev= 30
       0 129.297  18.266 129.056   35.18 127.881  55.139 127.289  60.535 126.855
  71.027  126.38  77.772 126.253  79.646 126.456  91.591 125.676 132.398 126.015
 156.055 126.525 164.984 126.441  173.65 126.864  173.65  126.62 173.662 125.356
 173.666 123.251 174.097 122.777 178.051 122.665 183.641 122.212 189.885  122.35
 191.133 126.521 191.138  126.61 191.625     126  194.13  126.55 197.448 126.732
 202.596 126.668 206.702  127.03 216.531 126.951 250.574 128.244 276.459 127.892
#Mann= 3 ,-1 , 0
       0      .1       0 173.662     .03       0 191.133      .1       0
#XS Ineff= 2 , 0
          158.85   129.1  221.76          129.43
Permanent Ineff=
       T       T
Bank Sta=173.65,191.138
XS Rating Curve= 0 ,0
Exp/Cntr=0.5,0.3

Type RM Length L Ch R = 1 ,1580.734,84.338,86.192,88.045
XS GIS Cut Line= 4
529852.2896944674778901.46369951529991.2333944674778891.79039951
 530059.837765334778921.20955716530189.0962944674778985.00579951
#Sta/Elev= 30
       0 129.431  16.216 128.862   27.92 127.028  30.274  127.87  38.574 127.238
  46.392   128.1  55.623 126.179  63.346 125.931   95.31 125.478 105.736 126.816
  115.22 126.946 118.561 125.859 129.795 127.097 139.279 126.217 142.512 127.214
 169.243 125.791  170.76 124.816 174.403 122.433 180.318 121.785 182.134 122.119
  182.87  124.83 182.979  126.39 183.439 126.126 183.455 125.347  193.45 126.409
 293.805  126.27  352.82  127.69 354.363 129.668 355.478     135 358.071 135.996
#Mann= 3 ,-1 , 0
       0      .1       0  170.76     .03       0 182.979      .1       0
Levee=0,,,-1,216.74,126.57,,Levee 2
#XS Ineff= 2 , 0
          168.81  137.33  227.31           136.9
Permanent Ineff=
       T       T
#Block Obstruct= 4 ,-1
  149.78   167.4  141.93  230.13   239.3     136  263.96   283.7  142.87
  306.26  322.11   142.1
Bank Sta=170.76,182.87
XS Rating Curve= 0 ,0
Exp/Cntr=0.5,0.3

Type RM Length L Ch R = 1 ,1494.543,3.255,3.257,3.259
XS GIS Cut Line= 4
529847.8927692214778912.01636558529943.4023350844778919.78756859
529963.1546046624778945.03232043530160.0763809474779022.81956298
#Sta/Elev= 30
       0  129.06   27.97 127.382  29.353  126.99  48.713 126.833  69.106 125.223
  83.386 124.938  88.169  125.48 105.142 124.545 105.809 123.721  107.57 123.604
 107.737 121.482 110.772 120.959 114.105 121.257 114.964 123.055 115.033  123.57
 115.532 122.837 116.451 123.417 118.067 124.517 121.181 124.693 136.662 124.366
  162.86 124.651 171.942 125.379 268.316 125.718 287.405 125.218 323.151 125.476
 334.629  124.99 337.605 127.219 338.204 126.966 339.121 127.521 339.607 127.165
#Mann= 4 ,-1 , 0
       0      .1       0 105.142     .03       0 116.451     .05       0
 171.942      .1       0
Levee=0,,,-1,180.09,125.6,,Levee 2
#XS Ineff= 4 ,-1
     .62  100.22  141.77  105.14  107.57  124.55  115.55  118.07  124.55
  174.85  336.43 141.963
Permanent Ineff=
       T       T       T       T
#Block Obstruct= 7 ,-1
    5.24   26.52  142.57   49.03   68.15   142.2   88.81  102.07  141.33
  186.26  206.92  130.87  229.74   239.6  141.07  251.01  265.81   141.1
  294.49   320.7  141.57
Bank Sta=107.57,115.033
XS Rating Curve= 0 ,0
Exp/Cntr=0.5,0.3

Type RM Length L Ch R = 4 ,1492.929,,,
BEGIN DESCRIPTION:
E148
END DESCRIPTION:
Bridge Culvert--1,0,-1,-1, 0
Deck Dist Width WeirC Skew NumUp NumDn MinLoCord MaxHiCord MaxSubmerge Is_Ogee
0.01,3.06,1.44,0, 13, 13, , , 0.95, 0, ,,,
  91.901  92.422 104.685 104.691 107.023 107.573 115.548   115.6 118.294 118.323
 121.121 133.257 133.376
 123.856 123.917 125.347 125.736 125.735 125.735 125.733 125.733 125.732 124.664
 124.703 121.292 121.258
 123.856  59.842  59.932  59.932  59.949 124.105 124.113   59.65  59.598  59.597
  59.549  59.343 121.258
  89.283  89.804 102.067 102.073   104.2  104.69  113.43  113.61 115.676 115.705
 118.503 130.639 130.758
 123.856 123.917 125.347 125.736 125.735 125.735 125.733 125.733 125.732 124.664
 124.703 121.292 121.258
 123.856  59.842  59.932  59.932  59.949 124.105 124.113   59.65  59.598  59.597
  59.549  59.343 121.258
BR Coef=-1 , 0 , 0 ,, 0 ,,,0.8,0,,0,
WSPro=,,,, 1 ,,,, 0 ,,,, 0 ,,,,-1 ,-1 ,-1 , 0 , 0 , 0 , 0 , 0
BC Mult= 1 ,0,104,0,102
BC Mult= 3 ,104,119,102,116
BC Mult= 1 ,119,350,116,350
BC Design=,, 0 ,, 0 ,,,,,,
BC Use User HTab Curves=0
BC User HTab FreeFlow(D)= 0

Type RM Length L Ch R = 1 ,1491.285,34.686,31.364,28.042
XS GIS Cut Line= 4
529847.8543391574778913.98778736529940.6535558024778921.53846091
 529960.405825384778946.78321274530157.3276016654779024.57045529
#Sta/Elev= 30
       0  129.03  28.009 127.396  30.016 126.899  49.079 126.624  69.095 125.714
  69.145 125.223  97.046 124.979 102.927  124.31 102.942 123.578  104.69 123.543
 104.931  121.35 106.486 121.119 112.487  121.35  112.59  123.55 113.076 123.291
 113.083 122.635 115.856 124.268 117.362 124.488 136.123 124.318 161.158 124.632
 169.057 125.332 175.012 125.496 223.337 125.313 224.471 125.662  242.31 125.396
 263.591 125.536 283.607 125.105 324.464 125.225  332.83 124.924  336.89 125.177
#Mann= 4 ,-1 , 0
       0      .1       0  104.69     .03       0  112.59     .05       0
 161.158      .1       0
Levee=0,,,-1,224.49,125.67,,Levee 2
#XS Ineff= 4 ,-1
     .31   96.52   143.7  100.92  104.69   124.5  113.43  115.86  124.27
  168.71  338.59141.1367
Permanent Ineff=
       T       T       T       T
#Block Obstruct= 7 ,-1
    4.93   27.14  143.07   50.26   69.38   141.7   85.73   95.59   139.7
  185.33  204.76   140.9  227.58  242.07  140.97   250.7  262.42     141
  293.57   324.1  140.97
Bank Sta=104.69,112.59
XS Rating Curve= 0 ,0
Exp/Cntr=0.5,0.3

Type RM Length L Ch R = 1 ,1459.922,33.012,29.825,26.807
XS GIS Cut Line= 4
529838.2194944674778937.51869951529913.199560079 4778960.8734427
529972.4899601464778961.17738089530154.7999944674779029.85469951
#Sta/Elev= 30
       0 128.171   7.137 127.914   14.53 126.952  21.072 125.518  40.379 125.303
  48.758 124.827  70.629  124.92  82.494 124.336  86.739 124.338  99.517 123.475
   99.62  122.88  99.868  121.26 103.413 121.054 105.723  121.29 106.216 122.883
  106.72 122.387 106.757  122.08 111.056 122.836  122.36 123.599 158.038 124.917
 173.682 124.765 176.595 125.369 205.901 125.146 250.574 125.403 256.053 125.352
 261.014 124.686 264.178 124.649 269.523 125.743 287.729 125.023 332.642 124.973
#Mann= 4 ,-1 , 0
       0      .1       0   99.62     .03       0 106.216     .05       0
 158.038      .1       0
Levee=0,,,-1,176.7,125.36,,Levee 2
#XS Ineff= 2 ,-1
    1.85    99.6   147.2  154.49  330.57  144.16
Permanent Ineff=
       T       T
#Block Obstruct= 6 ,-1
   31.45   41.01  143.48   65.07   71.85  132.68   86.34   98.37     146
  179.78  202.91  144.16  216.78  242.38  141.48  296.65  323.48  141.24
Bank Sta=99.62,106.216
XS Rating Curve= 0 ,0
Exp/Cntr=0.3,0.1

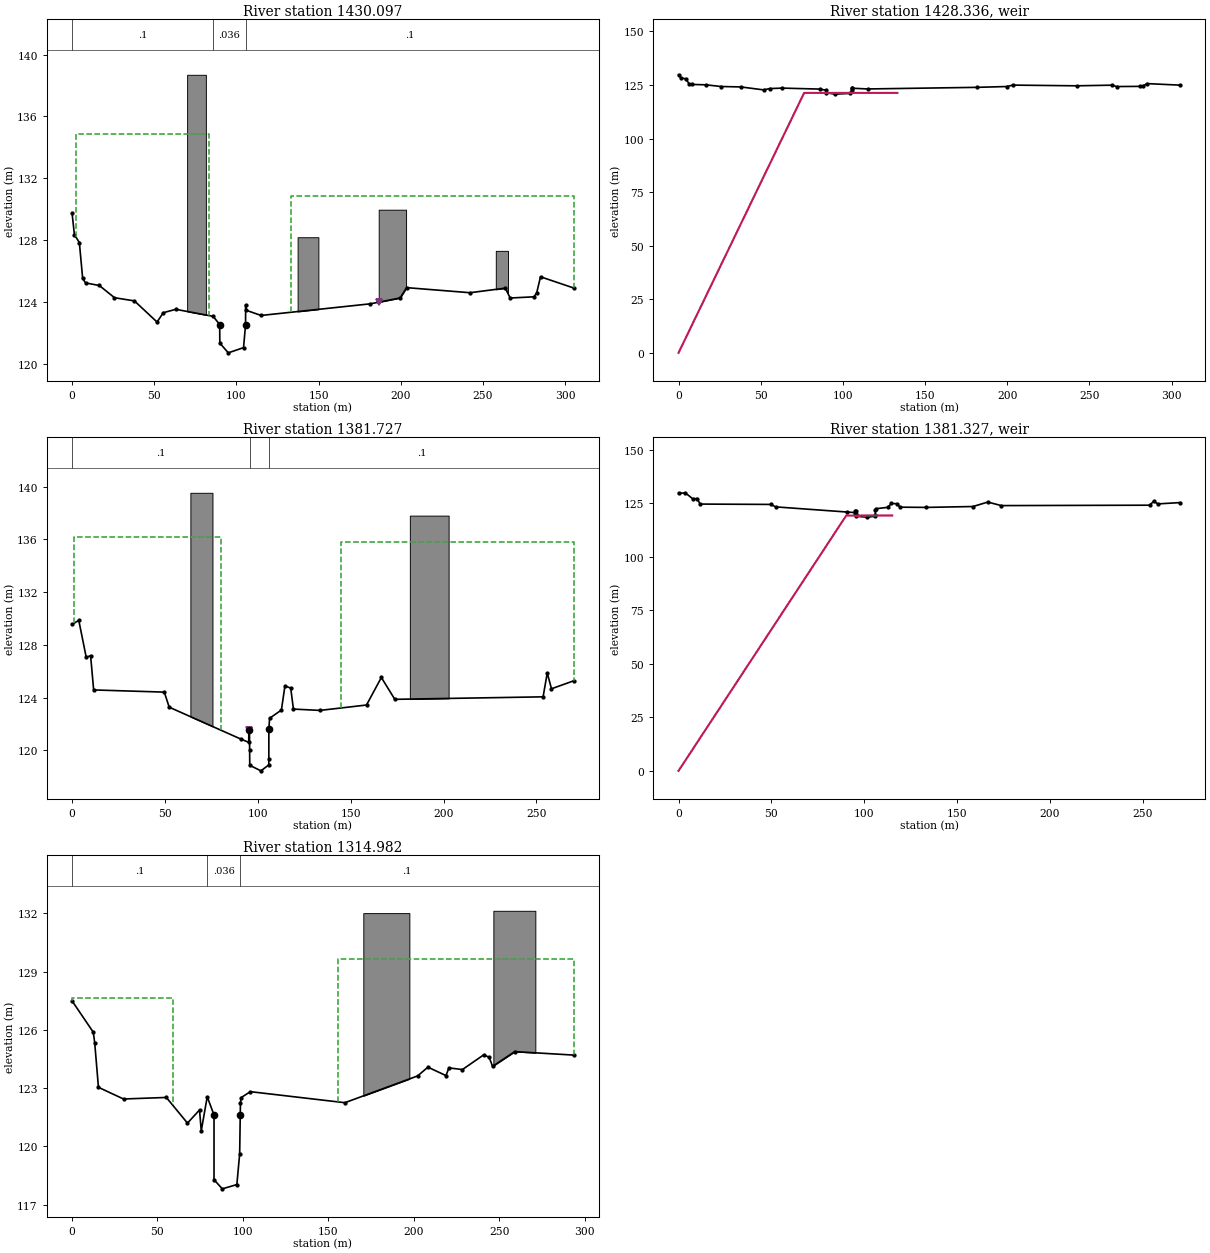
Type RM Length L Ch R = 1 ,1430.097,45.052,48.37,51.517
XS GIS Cut Line= 4
529839.3621581054779004.55084325 529914.600827934779012.56618457
529958.4268174684778974.31170953530118.7450295354779035.13102936
#Sta/Elev= 30
       0 129.751   1.417 128.356   4.434 127.848   6.445 125.527   8.237 125.236
  16.568 125.071  25.813 124.281  37.931 124.075    51.7 122.709  55.511 123.312
  63.115 123.53185.83987 123.07789.80885 122.54989.90361 121.34595.06054 120.718
104.3272 121.054105.5561  122.53105.6056 123.812105.7407 123.476114.9981 123.135
 181.572 123.887 199.609 124.266 203.519 124.932 242.138 124.604  263.62 124.899
 266.558 124.262 281.049 124.339 282.682  124.59 285.011 125.634 305.304 124.906
#Mann= 3 ,-1 , 0
       0      .1       085.83987    .036       0105.6056      .1       0
Levee=0,,,-1,186.87,124.03,,Levee 2
#XS Ineff= 2 ,-1
    2.47   83.26  134.88  132.91  312.69  130.83
Permanent Ineff=
       T       T
#Block Obstruct= 4 ,-1
      70   81.41  138.69  137.22  149.87  128.19  186.56  203.22  129.97
   257.8   265.2  127.31
Bank Sta=89.80885,105.5561
XS Rating Curve= 0 ,0
Exp/Cntr=0.3,0.1

Type RM Length L Ch R = 5 ,1428.336,,,
BEGIN DESCRIPTION:
E149
END DESCRIPTION:
IW Pilot Flow=0
#Inline Weir SE= 7
       0       0   76.41   121.3   98.06   121.3  101.35   121.3  108.07   121.3
  118.58   121.3  133.11   121.3
IW Dist,WD,Coef,Skew,MaxSub,Min_El,Is_Ogee,SpillHt,DesHd
0.1,2,1.7,0,0.98,, 0 ,,,0,0,

Type RM Length L Ch R = 1 ,1381.727,66.608,66.745,66.882
XS GIS Cut Line= 2
529839.1555688364779034.88764756530109.0895961274779045.84451454
#Sta/Elev= 30
       0 129.548   3.618 129.859   7.621 127.057   9.972 127.183  11.625 124.584
  49.656 124.419  52.291 123.277    90.8 120.864  95.118 120.612  95.165 121.573
  95.508 121.573  95.589 120.068  95.669  118.87 101.667 118.451 105.912   118.9
  105.93  119.37  105.95  121.59 106.339 122.434 112.708  123.06 114.605 124.888
 117.712 124.726 119.173 123.133  133.48 123.032 158.521 123.441 166.513 125.527
 173.758 123.872  253.59 124.061 255.826 125.867 258.113 124.672 270.157  125.28
#Mann= 3 ,-1 , 0
       0      .1       0  95.589    .036       0  105.95      .1       0
Levee=-1,95.34,121.57,0,,,Levee 40,Levee 41
#XS Ineff= 2 ,-1
    1.06   80.09  136.17  144.58  271.45  135.77
Permanent Ineff=
       T       T
#Block Obstruct= 2 ,-1
    63.7   75.59  139.53  181.85  202.73   137.8
Bank Sta=95.508,105.95
XS Rating Curve= 0 ,0
Exp/Cntr=0.3,0.1

Type RM Length L Ch R = 5 ,1381.327,,,
BEGIN DESCRIPTION:
E150
END DESCRIPTION:
IW Pilot Flow=0
#Inline Weir SE= 5
       0       0   90.26   119.2   95.61   119.2  105.87  119.25  115.03  119.25
IW Dist,WD,Coef,Skew,MaxSub,Min_El,Is_Ogee,SpillHt,DesHd
0.8,1.5,1.7,0,0.98,, 0 ,,,0,0,

Type RM Length L Ch R = 1 ,1314.982,19.106,19.098,19.09
XS GIS Cut Line= 2
529844.3810920134779098.42720243530137.2181137174779121.29135428
#Sta/Elev= 30
       0 127.493  12.428 125.879  13.247 125.339  15.437 123.044  30.123 122.444
  55.179 122.523  67.551 121.203  74.616 121.879  75.613   120.8  79.119 122.558
   83.09 121.619  83.091  118.29  87.949  117.82   96.46 118.039  98.111 119.632
   98.44   121.6  98.556  122.23  98.946 122.515 104.364 122.821 159.682 122.253
  202.27 123.631 208.293 124.082 218.878 123.648 220.582 124.044  228.51 123.959
  240.89 124.712 244.131 124.596 246.137 124.124 259.134 124.882 293.729 124.703
#Mann= 3 ,-1 , 0
       0      .1       0  79.119    .036       0  98.556      .1       0
#XS Ineff= 2 , 0
           58.94  127.62  155.95          129.66
Permanent Ineff=
       T       T
#Block Obstruct= 2 ,-1
  170.48  197.44  132.01  246.61  271.19  132.13
Bank Sta=83.09,98.44
XS Rating Curve= 0 ,0
Exp/Cntr=0.5,0.3