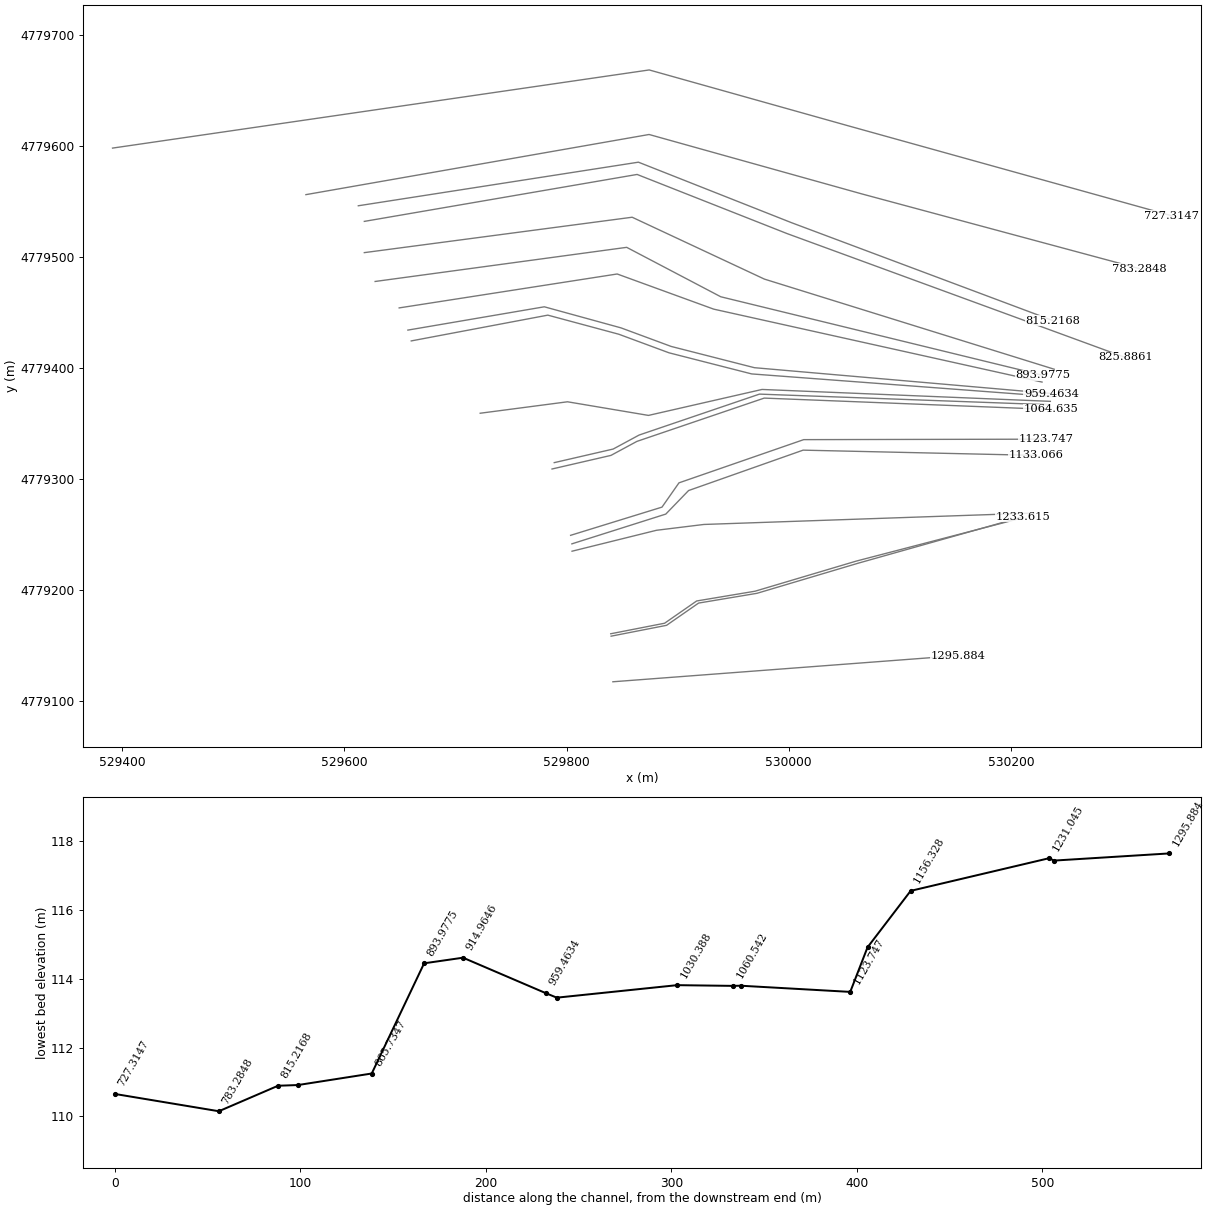
HEC-RAS study Durango.prj: Durango

--- Durango.g18 (geometry) --- (continued)

Type RM Length L Ch R = 4 ,1305.924,,,
BEGIN DESCRIPTION:
E151
END DESCRIPTION:
Bridge Culvert--1,0,-1,-1, 0
Deck Dist Width WeirC Skew NumUp NumDn MinLoCord MaxHiCord MaxSubmerge Is_Ogee
0.01,18.9,1.44,0, 16, 18, , , 0.95, 0, ,,,
   80.35    81.5  81.506  82.562   82.57   82.78  83.108  98.122  98.455  98.905
  98.909  99.939  99.946 100.696 116.985 117.202
 122.659 122.651 123.874 123.923 123.692 123.692 123.693 123.719 123.719  123.72
 123.905 123.898 122.666 122.658 118.155 118.095
   8.375   8.355   8.355   8.338   8.337   8.334 121.626 121.648   8.473   8.477
   8.477   8.487   8.487   8.493   8.639 118.095
  64.111  64.278  81.306  82.456  82.462  83.518  83.526  83.736  84.064  99.078
  99.411  99.861  99.865 100.895 100.902 101.652 117.941 118.158
 117.844  117.89 122.659 122.651 123.874 123.923 123.692 123.692 123.693 123.719
 123.719  123.72 123.905 123.898 122.666 122.658 118.155 118.095
 117.844   8.663   8.375   8.355   8.355   8.338   8.337   8.334 121.626 121.648
   8.473   8.477   8.477   8.487   8.487   8.493   8.639 118.095
BR Coef=-1 , 0 , 0 ,, 0 ,,,0.8,-1,,0,
WSPro=,,,, 1 ,,,, 0 ,,,, 0 ,,,,-1 ,-1 ,-1 , 0 , 0 , 0 , 0 , 0
BC Mult= 1 ,0,81.5,0,83
BC Mult= 3 ,81.5,100,83,101
BC Mult= 1 ,100,300,101,320
BC Design=,, 0 ,, 0 ,,,,,,
BC Use User HTab Curves=0
BC User HTab FreeFlow(D)= 0

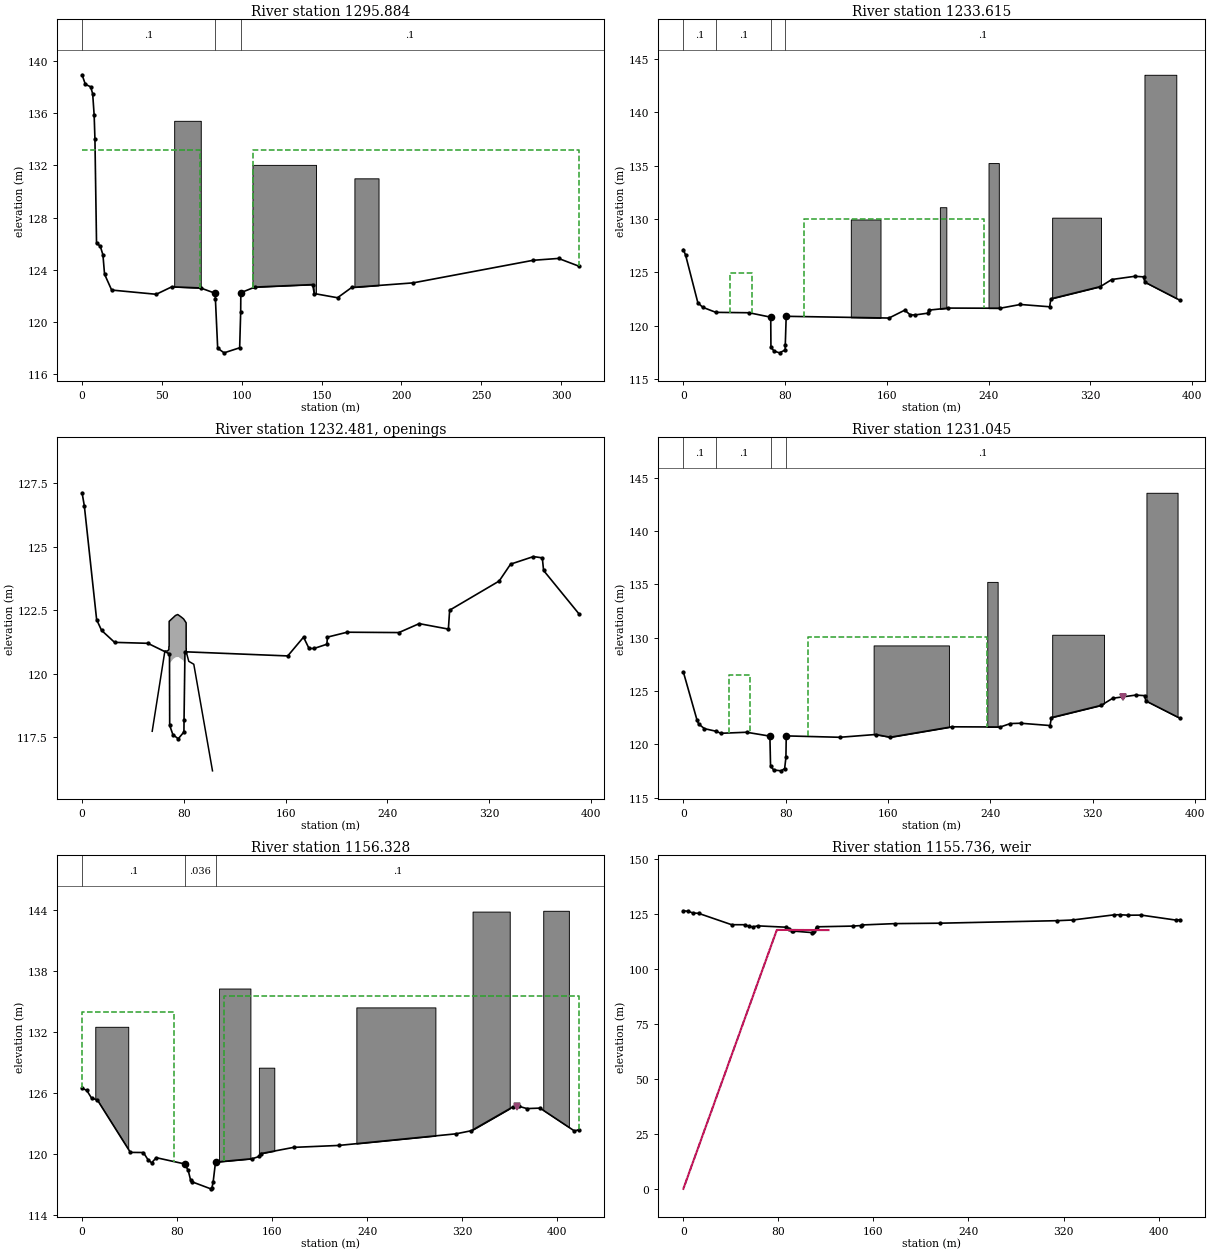
Type RM Length L Ch R = 1 ,1295.884,60.31,62.268,64.227
XS GIS Cut Line= 2
529841.7462682324779117.55019448530152.0994712774779141.07591912
#Sta/Elev= 30
       0 138.921   2.031 138.195   5.354     138   6.633 137.471   7.566 135.822
   8.048 134.018   9.051 126.028  11.362 125.825  13.062 125.146  14.065 123.671
  18.514 122.455  46.448 122.132  56.186 122.703  74.237 122.615    83.3  122.21
  83.483 121.785  84.913 118.008  88.915 117.653  98.675 118.039  99.309 120.747
  99.411 122.256 108.244 122.683 144.438 122.874 145.336 122.188 159.961 121.867
 168.837 122.654 207.213 123.003 282.463 124.732 298.337 124.874 311.243 124.275
#Mann= 3 ,-1 , 0
       0      .1       0  83.483    .036       0  99.309      .1       0
#XS Ineff= 2 , 0
            73.7   133.2     107          133.13
Permanent Ineff=
       T       T
#Block Obstruct= 3 ,-1
   57.67   74.32   135.4   106.7  146.48  132.03  170.53  185.64     131
Bank Sta=83.3,99.411
XS Rating Curve= 0 ,0
Exp/Cntr=0.5,0.3

Type RM Length L Ch R = 1 ,1233.615,2.57,2.57,2.57
XS GIS Cut Line= 6
  529840.1537523 4779158.5998097  529890.0445348 4779168.3558333
  529918.8902817 4779188.3848165  529971.4852207 4779197.1830659
    530062.41969 4779224.2449331  530210.4990666        4779266.
#Sta/Elev= 30
       0 127.133   1.783 126.612  11.445 122.136  15.327 121.713   25.57 121.241
  51.711 121.204  68.739 120.788  68.899  117.97  71.424 117.605  75.641 117.444
  80.093 117.713  80.178 118.164    80.9  120.87 161.737 120.707 174.147 121.447
 178.472     121 182.354     121 192.498 121.167 192.945 121.448 208.438 121.641
249.1274121.6271265.0979121.9789288.0556 121.764289.0538122.5084 327.982123.6561
336.9654124.3216354.9323124.6198361.9194124.5699362.9176124.0734 390.866122.3562
#Mann= 4 ,-1 , 0
       0      .1       0   25.57      .1       0  68.899    .036       0
  80.178      .1       0
#XS Ineff= 2 ,-1
   36.34   53.96  124.92   95.15  236.12  130.04
Permanent Ineff=
       T       T
#Block Obstruct= 5 ,-1
  131.72  155.07  129.95  201.76  206.83   131.1     240  248.11  135.24
  290.04  328.46  130.12  362.64  387.67  143.52
Bank Sta=68.739,80.9
XS Rating Curve= 0 ,0
Exp/Cntr=0.5,0.3

Type RM Length L Ch R = 4 ,1232.481,,,
BEGIN DESCRIPTION:
E152
END DESCRIPTION:
Bridge Culvert--1,0,-1,-1, 0
Deck Dist Width WeirC Skew NumUp NumDn MinLoCord MaxHiCord MaxSubmerge Is_Ogee
0.01,2.37,1.44,0, 32, 32, , , 0.95, 0, ,,,
  55.148  55.545  65.124  67.026  68.161  68.259  68.261  68.461   68.47  68.679
  71.722  73.453  73.716  74.453  75.053  75.252  75.793  77.553  78.051  79.555
  79.848  80.866  81.197   81.84  81.845  81.907  81.919  83.901  87.133   87.85
 102.175 102.559
  117.74 117.866 120.905 120.898 120.951 120.955 121.071 121.083 122.069 122.079
  122.22 122.301 122.306 122.322 122.335 122.337 122.318 122.255 122.237 122.175
 122.163 122.085  122.06 122.012 121.006 121.001 120.864 120.494   120.4 120.379
 116.291 116.181
  117.74  40.529  40.436  40.417  40.406   55.42  55.799  86.649   88.14   120.4
 120.591 120.648 120.657  120.66 120.662 120.663 120.665 120.602 120.584  120.53
 120.493 120.363  40.594  40.594  40.594  40.594  40.594  40.594  40.594  40.594
  40.594 116.181
  54.656  55.053  64.632  66.534  67.669  67.767  67.769  67.969  67.978  68.187
   71.23  72.961  73.224  73.961  74.561   74.76  75.301  77.061  77.559  79.063
  79.356  80.374  80.705  81.348  81.353  81.415  81.427  83.409  86.641  87.358
 101.683 102.067
  117.74 117.866 120.905 120.898 120.951 120.955 121.071 121.083 122.069 122.079
  122.22 122.301 122.306 122.322 122.335 122.337 122.318 122.255 122.237 122.175
 122.163 122.085  122.06 122.012 121.006 121.001 120.864 120.494   120.4 120.379
 116.291 116.181
  117.74  40.529  40.436  40.417  40.406   55.42  55.799  86.649   88.14   120.4
 120.591 120.648 120.657  120.66 120.662 120.663 120.665 120.602 120.584  120.53
 120.493 120.363  40.594  40.594  40.594  40.594  40.594  40.594  40.594  40.594
  40.594 116.181
BR Coef=-1 , 0 , 0 ,, 0 ,,,0.8,-1,,0,
WSPro=,,,, 1 ,,,, 0 ,,,, 0 ,,,,-1 ,-1 ,-1 , 0 , 0 , 0 , 0 , 0
BC Mult= 1 ,0,68,0,67
BC Mult= 3 ,68,82,67,82
BC Mult= 1 ,82,400,82,400
BC Design=,, 0 ,, 0 ,,,,,,
BC Use User HTab Curves=0
BC User HTab FreeFlow(D)= 0

Type RM Length L Ch R = 1 ,1231.045,76.511,74.718,72.925
XS GIS Cut Line= 6
  529839.8164404 4779160.7673169  529888.3078166 4779170.2496899
  529917.1535635 4779190.2786732  529969.7485025 4779199.0769225
  530060.6829718 4779226.1387898  530209.9272401        4779265.
#Sta/Elev= 30
       0 126.801  10.645 122.303  11.967 121.912   16.52 121.471  25.693 121.225
  29.312 121.036  49.411 121.134   67.66  120.77  68.172 117.967  70.623 117.595
  76.523 117.514  79.192 117.728  80.185 118.773  80.445   120.8   80.49 120.792
 122.358 120.662 150.198 120.923 161.753 120.668 209.833 121.645247.7024121.6271
255.6877121.9511263.6729121.9789286.6306 121.764287.6288122.5084 326.557123.6561
335.5404124.3216353.5073124.6198360.4944124.5699361.4926124.0734388.4429122.4281
#Mann= 4 ,-1 , 0
       0      .1       0  25.693      .1       0  68.172    .036       0
  80.185      .1       0
Levee=0,,,-1,343.61,124.44,,Levee 42
#XS Ineff= 2 ,-1
   35.46   52.42  126.52   97.36     237  130.04
Permanent Ineff=
       T       T
#Block Obstruct= 4 ,-1
  148.72  207.58  129.28  237.53  245.64  135.24  288.28  328.81  130.28
  361.94  386.26   143.6
Bank Sta=67.66,80.49
XS Rating Curve= 0 ,0
Exp/Cntr=0.5,0.3

Type RM Length L Ch R = 1 ,1156.328,20.618,23.261,25.798
XS GIS Cut Line= 4
  529804.9874122 4779235.0745122  529881.0140122 4779253.9159122
  529923.6638122 4779259.1528122  530220.5046413 4779269.4063003
#Sta/Elev= 30
       0 126.487   3.966 126.262   7.932 125.509  12.889 125.313   40.65 120.154
  51.557 120.141  55.523 119.427  58.497 119.129  62.463 119.632  86.321 119.017
  89.319 118.381  91.318 117.429  92.317 117.265 108.306 116.563 109.305  116.68
 110.304 117.231 112.303 119.198 143.224  119.53 149.204 119.761 150.201  120.03
 178.109 120.649 215.984 120.839 314.657 121.983 327.614 122.289 362.499 124.632
 367.483 124.697  374.46  124.47 385.423 124.517 414.328 122.269 418.315 122.391
#Mann= 3 ,-1 , 0
       0      .1       0  86.321    .036       0 112.303      .1       0
Levee=0,,,-1,365.64,124.68,,Levee 42
#XS Ineff= 2 , 0
           77.44  134.03  119.21           135.6
Permanent Ineff=
       T       T
#Block Obstruct= 6 ,-1
    11.1   38.85  132.53  115.24  141.67   136.3  148.81  161.76   128.5
  230.84  297.36  134.44  328.63  359.91  143.88  388.11  409.69  143.96
Bank Sta=86.321,112.303
XS Rating Curve= 0 ,0
Exp/Cntr=0.3,0.1

Type RM Length L Ch R = 5 ,1155.736,,,
BEGIN DESCRIPTION:
E153
END DESCRIPTION:
IW Pilot Flow=0
#Inline Weir SE= 5
       0       0    78.7  117.77   89.97  117.77  111.46  117.71  122.25  117.71
IW Dist,WD,Coef,Skew,MaxSub,Min_El,Is_Ogee,SpillHt,DesHd
0.1,1.3,1.7,0,0.98,, 0 ,,,0,0,

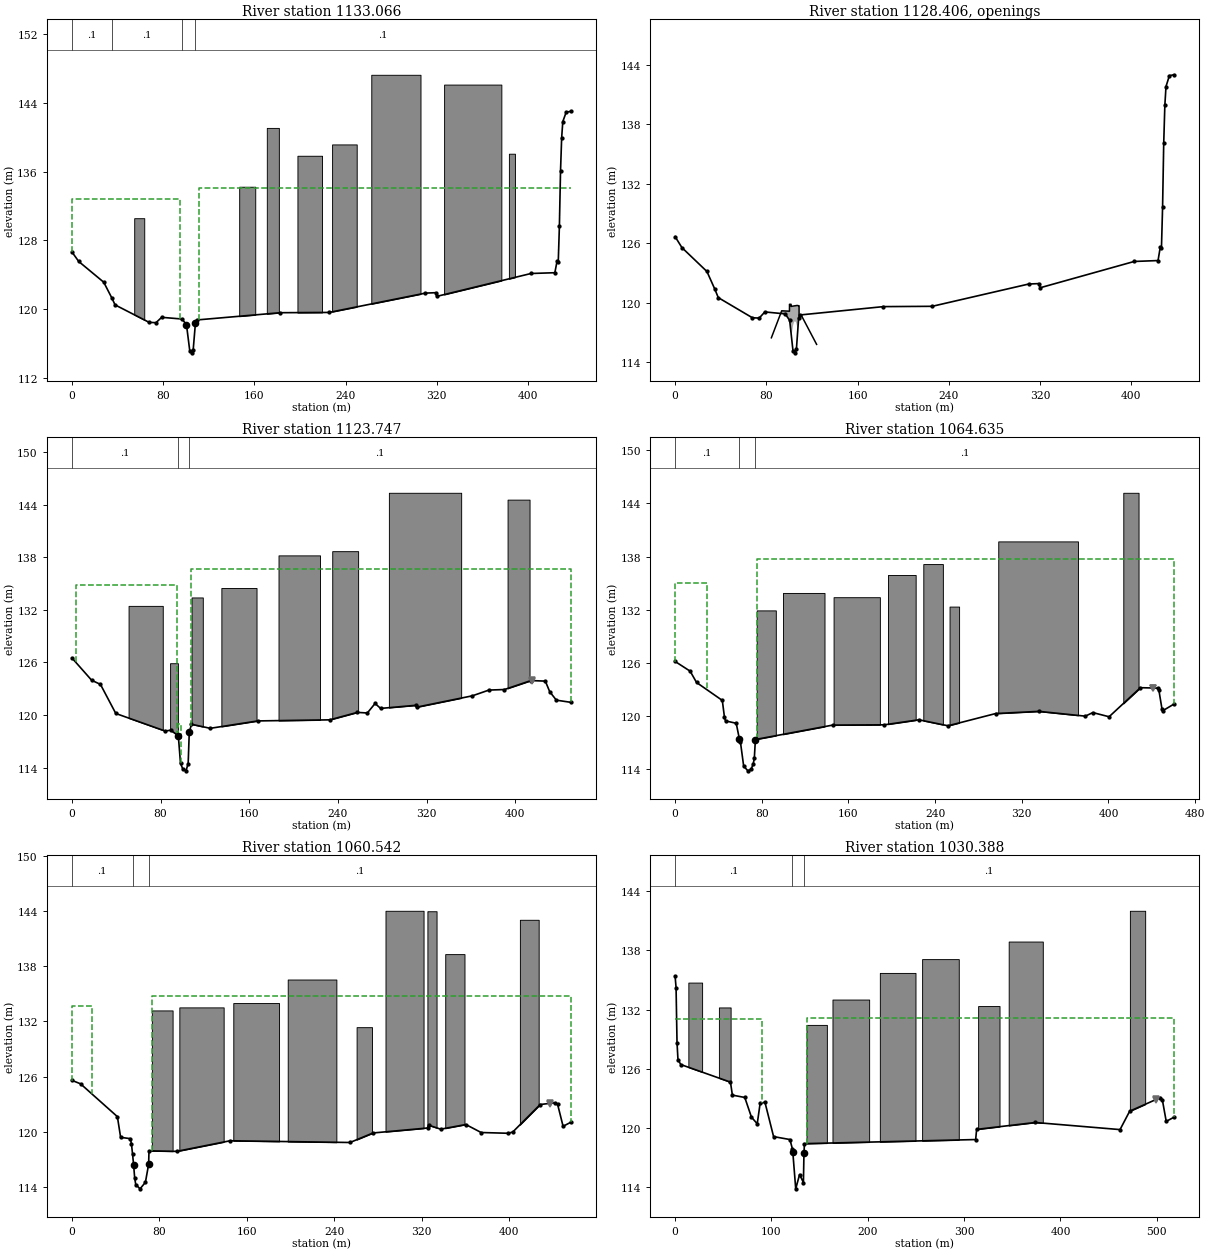
Type RM Length L Ch R = 1 ,1133.066,8.865,9.319,9.88
XS GIS Cut Line= 5
  529804.8397122 4779241.7007122  529889.3729122 4779268.4929122
  529909.8838122 4779289.6791122  530012.9753924 4779326.0432173
  530222.9383242 4779321.3248688
#Sta/Elev= 30
       0 126.654   5.978 125.546  27.899 123.135  34.873 121.337  37.862 120.496
  67.754 118.463  73.732 118.429  78.714 119.051  96.541 118.853 100.473 118.199
 103.422 115.087 105.387  114.92  106.37 115.274 108.336 118.405 109.319 118.742
 182.762 119.588 225.495 119.618 310.095 121.868 319.053 121.914 320.048 121.488
 402.661 124.148 423.563 124.239 425.553 125.617 426.549 125.478 427.544 129.619
 428.539 136.062 429.535  139.92  430.53 141.811 433.516 142.914 437.497     143
#Mann= 4 ,-1 , 0
       0      .1       0  34.873      .1       0  96.541    .036       0
 108.336      .1       0
#XS Ineff= 2 , 0
           94.71  132.87  111.89          134.08
Permanent Ineff=
       T       T
#Block Obstruct= 8 ,-1
   54.63   63.44  130.58   146.7  160.79  134.24  170.93   181.5  141.08
   197.8  219.38  137.84  228.19  249.78  139.16  262.56  305.73  147.26
  326.43  376.65  146.12  383.26  388.55  138.08
Bank Sta=100.473,108.336
XS Rating Curve= 0 ,0
Exp/Cntr=0.5,0.3

Type RM Length L Ch R = 4 ,1128.406,,,
BEGIN DESCRIPTION:
E154
END DESCRIPTION:
Bridge Culvert--1,0,-1,-1, 0
Deck Dist Width WeirC Skew NumUp NumDn MinLoCord MaxHiCord MaxSubmerge Is_Ogee
0.01,9.12,1.44,0, 32, 32, , , 0.95, 0, ,,,
  84.423  84.985  93.478 100.306 100.318 101.457 101.705 101.711 101.714 101.754
 102.054 102.671 103.288 104.074 104.598 105.337 105.988 106.325 106.912 107.062
 107.506 108.041 108.247 108.453 108.551 108.723 108.733 108.883 110.461 110.746
 123.802 124.102
 116.439 116.608 119.166 119.126 119.823 119.821 119.821 119.821 119.611 119.611
 119.617 119.628 119.639 119.653 119.663 119.676 119.688 119.694 119.704 119.707
 119.697 119.685 119.681 119.676 119.674  119.67 118.696 118.696 118.696 118.696
 115.841 115.775
 116.439  43.049  42.837  42.666  42.666  42.638 115.193 115.223 115.241 115.441
  116.25 117.093 117.585  117.95 118.073 118.108 118.005   117.9 117.619 117.505
 117.169 116.524 116.157 115.622 115.182  77.277  75.153  41.985  41.955   41.95
  41.706 115.775
  81.229  81.791  90.284  97.112  97.124  98.263  98.511  98.517   98.52   98.56
   98.86  99.477 100.094  100.88 101.404 102.143 102.794 103.131 103.718 103.868
 104.312 104.847 105.053 105.259 105.357 105.529 105.539 105.689 107.267 107.552
 120.608 120.908
 116.439 116.608 119.166 119.126 119.823 119.821 119.821 119.821 119.611 119.611
 119.617 119.628 119.639 119.653 119.663 119.676 119.688 119.694 119.704 119.707
 119.697 119.685 119.681 119.676 119.674  119.67 118.696 118.696 118.696 118.696
 115.841 115.775
 116.439  43.049  42.837  42.666  42.666  42.638 115.193 115.223 115.241 115.441
  116.25 117.093 117.585  117.95 118.073 118.108 118.005   117.9 117.619 117.505
 117.169 116.524 116.157 115.622 115.182  77.277  75.153  41.985  41.955   41.95
  41.706 115.775
BR Coef=-1 , 0 , 0 ,, 0 ,,,0.8,0,,0,
WSPro=,,,, 1 ,,,, 0 ,,,, 0 ,,,,-1 ,-1 ,-1 , 0 , 0 , 0 , 0 , 0
BC Mult= 1 ,0,100,0,95
BC Mult= 3 ,100,108,95,106
BC Mult= 1 ,108,500,106,500
BC Design=,, 0 ,, 0 ,,,,,,
BC Use User HTab Curves=0
BC User HTab FreeFlow(D)= 0

Type RM Length L Ch R = 1 ,1123.747,60.837,59.112,57.387
XS GIS Cut Line= 5
  529803.6931122 4779249.3725122  529885.9573122 4779274.7632122
  529901.2370122 4779296.6123122  530013.5071349 4779335.5038908
  530231.8618281 4779335.9269662
#Sta/Elev= 30
       0 126.502  17.812 123.954  25.729 123.485  39.583 120.165  84.114 118.162
  89.056 118.259  95.968 117.623  97.943 114.472  99.918 113.866 102.881 113.623
 104.855 114.446 105.843 118.021 107.818 118.937 124.737 118.473  167.67 119.317
 232.567  119.44 257.494 120.291 266.467 120.221 273.447 121.307 278.432 120.744
 310.338   121.1 311.335 120.896 361.189  122.18 376.145 122.836 390.104 122.897
 414.034 123.919 426.996 123.858 430.984 122.647 436.966 121.684 449.928 121.439
#Mann= 3 ,-1 , 0
       0      .1       0  95.968    .036       0 105.843      .1       0
Levee=0,,,-1,414.98,123.97,,Levee 43
#XS Ineff= 3 ,-1
     3.3   95.15   134.8   95.82   98.52     119  107.49  452.86  136.64
Permanent Ineff=
       T       T       T
#Block Obstruct= 8 ,-1
    51.1   81.94  132.44   88.55   95.59   125.9  107.93  118.06   133.4
   134.8  166.52  134.48  186.34  223.79   138.2   234.8  258.15  138.68
   285.9   351.1  145.34  392.95  412.78  144.56
Bank Sta=95.968,105.843
XS Rating Curve= 0 ,0
Exp/Cntr=0.5,0.3

Type RM Length L Ch R = 1 ,1064.635,4.091,4.093,4.095
XS GIS Cut Line= 5
  529786.9675122 4779309.0818122  529840.0195122 4779321.3245122
  529863.3667122 4779333.9245122  529977.9636353 4779372.8920086
   530236.146124 4779362.6721272
#Sta/Elev= 30
       0 126.154  13.859 125.058  19.799 123.778  43.557 121.754  45.537 119.868
  46.527 119.442  56.412 119.174  59.359 117.377  60.342 117.012   63.29 114.324
   67.22 113.803  70.168 113.975  72.133   114.6  73.116 115.233  74.098 117.341
 145.466 118.968 193.088     119 224.963 119.568 251.899  118.89 295.794  120.27
 335.699 120.519 378.596 119.978  385.58  120.38 400.544  119.91 429.475 123.192
 445.437 123.145 446.435 122.976 449.427 120.749 450.425 120.613 460.401 121.339
#Mann= 3 ,-1 , 0
       0      .1       0  59.359    .036       0  74.098      .1       0
Levee=0,,,-1,441.41,123.17,,Levee 43
#XS Ineff= 2 ,-1
     .22   29.07     135   75.77  462.33  137.72
Permanent Ineff=
       T       T
#Block Obstruct= 8 ,-1
   75.33   92.95  131.92   99.56  137.89  133.89  146.26  188.99  133.41
  196.48  222.03  135.92  229.07  247.14  137.15   253.3  262.11  132.35
  298.24  371.81  139.71  413.66  427.75   145.2
Bank Sta=59.359,74.098
XS Rating Curve= 0 ,0
Exp/Cntr=0.3,0.1

Type RM Length L Ch R = 1 ,1060.542,32.59,30.154,27.718
XS GIS Cut Line= 5
  529788.9732122 4779314.8003122  529842.0252122 4779327.0430122
  529865.3724122 4779339.6429122  529973.7069699 4779376.4810395
  530234.3208619 4779366.9310723
#Sta/Elev= 30
       0 125.591   7.919  125.21  41.577 121.644  44.547 119.394  53.456 119.254
  54.446 118.682  55.429 117.602  56.411 116.411  57.394 114.985  58.377 114.264
  62.307 113.798   67.22 114.511  70.168 116.474   70.48  117.93  95.902  117.87
 144.657 119.024 254.355 118.835 275.338  119.87 325.296 120.411 326.296 120.711
 337.287 120.283 360.268 120.789 374.256  119.92 399.235 119.836 403.232 119.982
 428.212 122.963   442.2 123.157 444.198 122.976 449.194 120.597 456.189 121.028
#Mann= 3 ,-1 , 0
       0      .1       0  55.429    .036       0   70.48      .1       0
Levee=0,,,-1,437.44,122.97,,Levee 43
#XS Ineff= 2 ,-1
     .44   18.28  133.68   72.91  457.93134.7534
Permanent Ineff=
       T       T
#Block Obstruct= 9 ,-1
   73.13   92.07  133.19   98.24  138.77  133.52  147.58  189.43  133.99
  197.36  241.85  136.55  260.35  274.45  131.37  286.78  321.59  144.02
  325.11  333.48  143.97  341.41  359.03  139.31  409.69  426.87  143.04
Bank Sta=56.411,70.168
XS Rating Curve= 0 ,0
Exp/Cntr=0.3,0.1

Type RM Length L Ch R = 1 ,1030.388,65.548,64.859,64.168
XS GIS Cut Line= 5
  529722.3136967 4779359.2708863  529800.8957832 4779369.5750236
  529873.7799122 4779357.3109122  529976.0082381  4779380.677578
  530235.5377033 4779369.9731759
#Sta/Elev= 30
       0 135.373    .991 134.225   1.981 128.633   2.972 126.911   5.944 126.419
   57.46 124.637  59.441 123.321   72.32 123.083  79.255 121.084  85.247 120.416
  88.244 122.487  93.237 122.599 102.226 119.114 119.205 118.817 121.834 117.833
 122.202 117.512 125.198 113.819 129.193 115.268 133.188 114.459  133.74  117.42
  134.27   118.4 311.978 118.816 312.977 119.847 373.919 120.546 461.836 119.825
 471.826 121.687 503.796 123.077 505.794 122.827  509.79 120.659 517.783 121.075
#Mann= 3 ,-1 , 0
       0      .1       0 121.834    .036       0  133.74      .1       0
Levee=0,,,-1,499.56,122.79,,Levee 43
#XS Ineff= 2 , 0
            90.4  131.05  136.92          131.19
Permanent Ineff=
       T       T
#Block Obstruct= 9 ,-1
   13.74   28.02  134.73   45.46   57.62  132.21  136.39  157.53  130.44
  163.35  201.41  133.01  212.51  249.52  135.71  256.39  294.45  137.11
  314.54  336.74  132.35  346.26  381.67  138.89  472.07  487.93  142.01
Bank Sta=122.202,133.74
XS Rating Curve= 0 ,0
Exp/Cntr=0.5,0.3

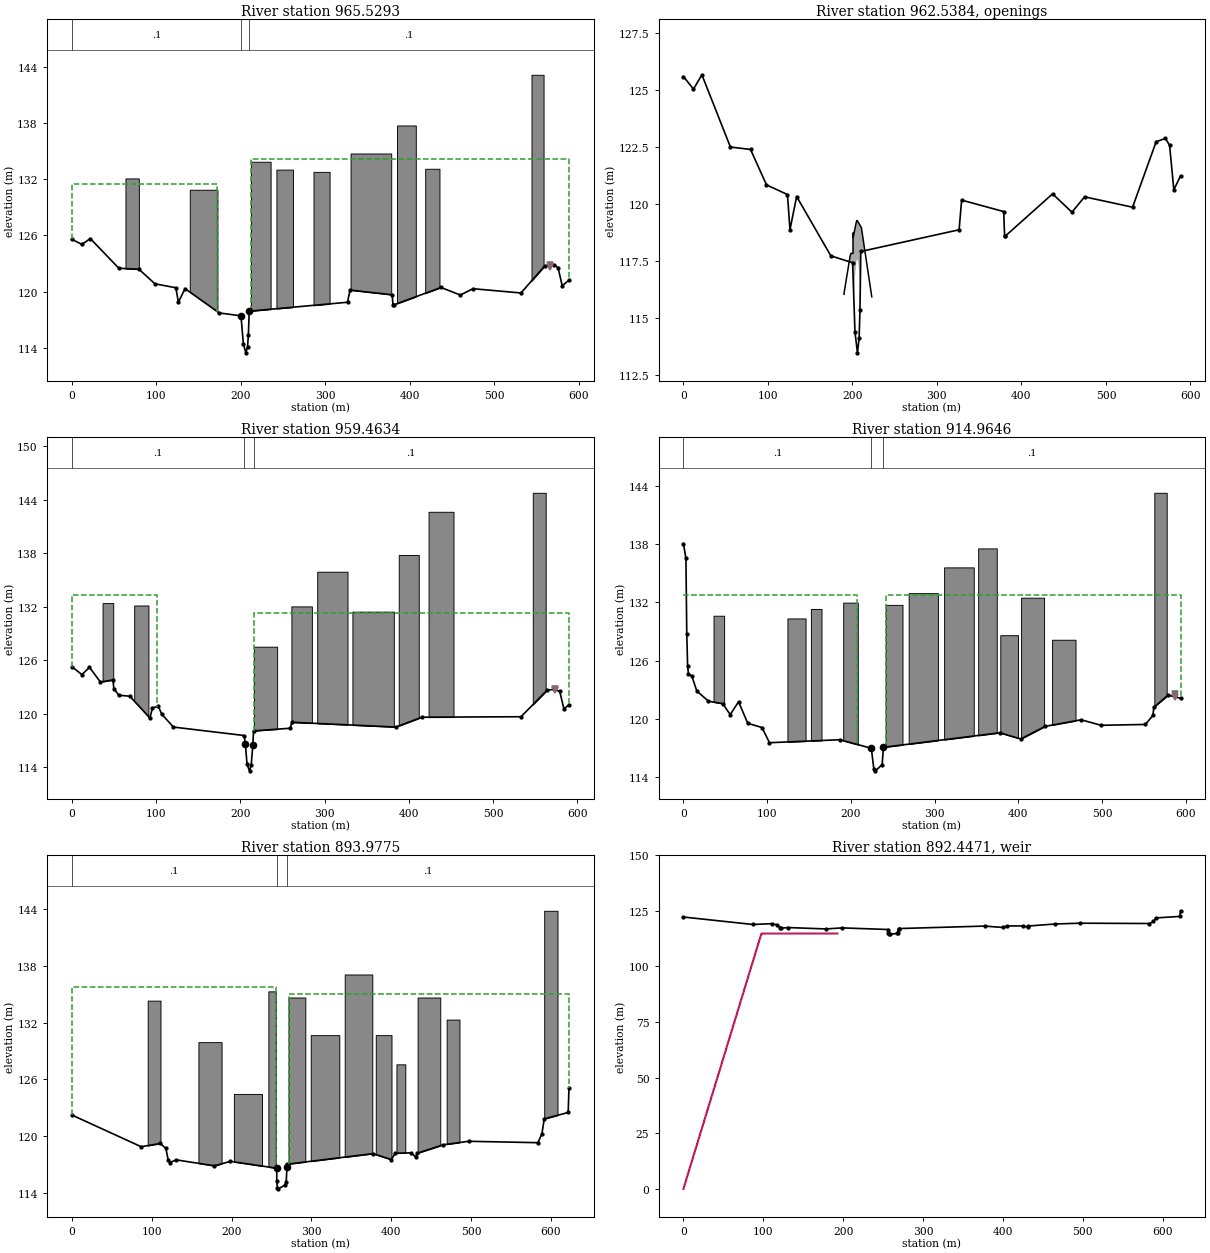
Type RM Length L Ch R = 1 ,965.5293,6.065,6.066,6.068
XS GIS Cut Line= 6
  529660.2547828 4779424.3719039  529783.1769809 4779447.5707518
  529847.0067122 4779430.4019122  529892.2405122 4779413.6676122
  529966.7043794 4779394.6571931  530237.9713862  4779374.232121
#Sta/Elev= 30
       0 125.577  11.914 125.025  21.841 125.653  55.597 122.483  79.424 122.377
  98.287 120.824 123.107 120.399 126.079 118.857 133.971 120.312 174.419 117.711
 200.201 117.406 203.002 114.372 205.955 113.455 207.923  114.11 208.908 115.321
 209.892 117.901 326.237 118.854 329.226 120.155 379.049 119.652 380.046 118.591
 381.042 118.581 436.844 120.429 459.763 119.624  474.71 120.299 531.508 119.844
 559.409 122.715  570.37 122.862 575.352 122.559 580.334 120.605 588.306 121.219
#Mann= 3 ,-1 , 0
       0      .1       0 200.201    .036       0 209.892      .1       0
Levee=0,,,-1,565.64,122.6,,Levee 43
#XS Ineff= 2 , 0
          172.33  131.47  212.51          134.13
Permanent Ineff=
       T       T
#Block Obstruct= 9 ,-1
   63.44    79.3  132.07  139.56  172.33  130.86  211.98  235.24  133.85
  242.11  261.67  133.01  285.99  305.02  132.77  329.87  377.97  134.73
  384.85  407.05  137.72  418.15  435.07   133.1  543.96  558.24  143.13
Bank Sta=200.201,209.892
XS Rating Curve= 0 ,0
Exp/Cntr=0.5,0.3

Type RM Length L Ch R = 4 ,962.5384,,,
BEGIN DESCRIPTION:
E155
END DESCRIPTION:
Bridge Culvert--1,0,-1,-1, 0
Deck Dist Width WeirC Skew NumUp NumDn MinLoCord MaxHiCord MaxSubmerge Is_Ogee
0.01,5.87,1.44,0, 29, 29, , , 0.95, 0, ,,,
     190 190.177 197.294 198.314 200.661 200.674 200.915 200.918 201.311 201.675
 202.076 202.748 203.393 204.642 204.733 205.338 205.446 206.191 207.084 207.175
 208.206 209.157 209.631 209.899 210.088 210.123 210.591 222.808 222.875
 116.024 116.092 117.709 117.819 117.818 118.711 118.712 118.527 118.599 118.664
 118.737 118.859 118.976 119.202  119.21 119.263 119.257 119.218 119.171 119.166
   119.1  119.04 119.009 118.992  118.98 118.978 118.948 115.931 115.915
 116.024  67.094  67.035  67.026  67.006  67.006  67.004  67.004  67.001 115.504
 115.995 116.596 117.001 117.438  117.47 117.541 117.554 117.531 117.349 117.309
 116.849 116.098 115.538 115.127  67.016  67.016  67.006  66.752 115.915
 194.818 195.118 202.235 203.255 205.602 205.615 205.856 205.859 206.252 206.616
 207.017 207.689 208.334 209.583 209.674 210.279 210.387 211.132 212.025 212.116
 213.147 214.098 214.572  214.84 215.029 215.064 215.532 227.749 227.816
 116.024 116.092 117.709 117.819 117.818 118.711 118.712 118.527 118.599 118.664
 118.737 118.859 118.976 119.202  119.21 119.263 119.257 119.218 119.171 119.166
   119.1  119.04 119.009 118.992  118.98 118.978 118.948 115.931 115.915
 116.024  67.094  67.035  67.026  67.006  67.006  67.004  67.004  67.001 115.504
 115.995 116.596 117.001 117.438  117.47 117.541 117.554 117.531 117.349 117.309
 116.849 116.098 115.538 115.127  67.016  67.016  67.006  66.752 115.915
BR Coef=-1 , 0 , 0 ,, 0 ,,,0.8,-1,,0,
WSPro=,,,, 1 ,,,, 0 ,,,, 0 ,,,,-1 ,-1 ,-1 , 0 , 0 , 0 , 0 , 0
BC Mult= 1 ,0,200,0,205
BC Mult= 3 ,200,216,205,216
BC Mult= 1 ,216,600,216,600
BC Design=,, 0 ,, 0 ,,,,,,
BC Use User HTab Curves=0
BC User HTab FreeFlow(D)= 0

Type RM Length L Ch R = 1 ,959.4634,44.48,44.499,44.518
XS GIS Cut Line= 6
  529657.2126792 4779434.1066354  529780.0247007 4779455.0776081
  529849.0124122 4779436.1203122  529894.2462122 4779419.3860122
  529969.1400169 4779400.2658312  530236.5644133 4779376.9826897
#Sta/Elev= 30
       0 125.281  11.961 124.375  20.931 125.202  33.888  123.55  48.839 123.782
  49.836 122.799  55.816 122.064  68.773 121.958  92.695 119.504  95.685 120.638
 102.662 120.839 106.649 119.948 120.603 118.497 204.586 117.549 205.978 116.589
 207.946 114.339 210.899 113.589 212.868 114.222 214.836  116.45  215.68  118.07
 259.229 118.366 261.211 119.036 384.528   118.5 415.462 119.603 533.214 119.657
  564.15 122.636 572.133 122.724 579.119 122.511 584.109 120.528 590.096 121.002
#Mann= 3 ,-1 , 0
       0      .1       0 204.586    .036       0  215.68      .1       0
Levee=0,,,-1,573.04,122.74,,Levee 43
#XS Ineff= 2 , 0
          100.97  133.29  216.74          131.28
Permanent Ineff=
       T       T
#Block Obstruct= 9 ,-1
   36.48   49.16   132.4   74.01   90.93  132.13  216.22   243.7  127.51
  260.62  284.93  132.03  291.28  327.22  135.92  333.04   382.2  131.44
  388.02  411.81  137.79  423.44  453.04  142.64  547.14  562.47  144.77
Bank Sta=205.978,214.836
XS Rating Curve= 0 ,0
Exp/Cntr=0.5,0.3

Type RM Length L Ch R = 1 ,914.9646,21.482,20.987,20.492
XS GIS Cut Line= 4
  529649.3708121 4779454.0831159  529845.6079122 4779484.6141122
  529932.5204122 4779452.9652122  530228.0465231  4779387.325842
#Sta/Elev= 30
       0 138.073   2.994  136.55   3.992  128.73    4.99 125.465   5.988 124.624
    9.98 124.418  15.968 122.858  29.939 121.805  46.905 121.556  55.887 120.423
  65.867 121.751  76.844 119.524   93.81 119.091 102.792 117.522 186.622  117.83
 224.457 116.949 227.441 114.797  229.43 114.618 237.387 115.264  238.94  117.05
 378.017 118.549 402.995 117.905 431.969 119.208 474.931 119.888  498.91  119.32
 551.862 119.406 560.854 120.342 561.853 121.177 578.837 122.429 593.823 122.104
#Mann= 3 ,-1 , 0
       0      .1       0 224.457    .036       0  238.94      .1       0
Levee=0,,,-1,586.78,122.51,,Levee 43
#XS Ineff= 2 , 0
          207.75  132.73  241.59          132.77
Permanent Ineff=
       T       T
#Block Obstruct= 12 ,-1
   35.95   48.63  130.63  124.23   145.9  130.35  152.25  164.93  131.33
  190.84  208.28  131.98  241.59  261.67  131.75  269.07  303.96  132.96
  311.37  346.78  135.62  352.07  374.27  137.58   378.5  399.65  128.62
  403.35  430.84  132.49  440.35  468.37  128.15  562.47  577.27  143.32
Bank Sta=224.457,238.94
XS Rating Curve= 0 ,0
Exp/Cntr=0.3,0.1

Type RM Length L Ch R = 1 ,893.9775,28.072,28.243,28.414
XS GIS Cut Line= 4
  529627.7380752 4779477.8791264  529854.1578122 4779508.5986122
  529938.8780122 4779464.0989122  530228.6549439 4779393.4100492
#Sta/Elev= 30
       0 122.244  86.808 118.899 110.755 119.241 117.739 118.718 120.733 117.488
 122.728 117.228  130.71  117.51 178.604 116.887  198.56 117.357  256.56  116.63
  256.57 115.257 257.402 114.527 258.399 114.455  267.37 114.868 268.367 115.131
 269.364 116.734 269.463 117.055  377.06  118.17 400.004 117.542 404.992 118.214
 424.943 118.254 430.928 117.771 431.926   118.2 464.845 119.102 496.767 119.472
 583.555 119.323 588.542 120.256 591.535 121.839 621.462 122.513 622.459 125.053
#Mann= 3 ,-1 , 0
       0      .1       0  256.56    .036       0 269.463      .1       0
#XS Ineff= 2 , 0
          255.33  135.76  271.98          135.06
Permanent Ineff=
       T       T
#Block Obstruct= 12 ,-1
   94.98  111.01  134.31   158.5  187.49  129.93  202.91  238.06  124.47
  246.08  255.33  135.29  271.37  292.33  134.64  299.12  334.89  130.67
  341.67  376.21  137.07  380.53  400.26  130.67  406.43  417.53  127.59
  432.95  461.32  134.64  469.34  485.37  132.31  591.45  608.11  143.79
Bank Sta=256.56,269.364
XS Rating Curve= 0 ,0
Exp/Cntr=0.3,0.1

Type RM Length L Ch R = 5 ,892.4471,,,
BEGIN DESCRIPTION:
E156
END DESCRIPTION:
IW Pilot Flow=0
#Inline Weir SE= 5
       0       0   97.57  114.75  124.02  114.75  139.14  114.81  192.75  114.81
IW Dist,WD,Coef,Skew,MaxSub,Min_El,Is_Ogee,SpillHt,DesHd
1.8,1.8,1.7,0,0.98,, 0 ,,,0,0,

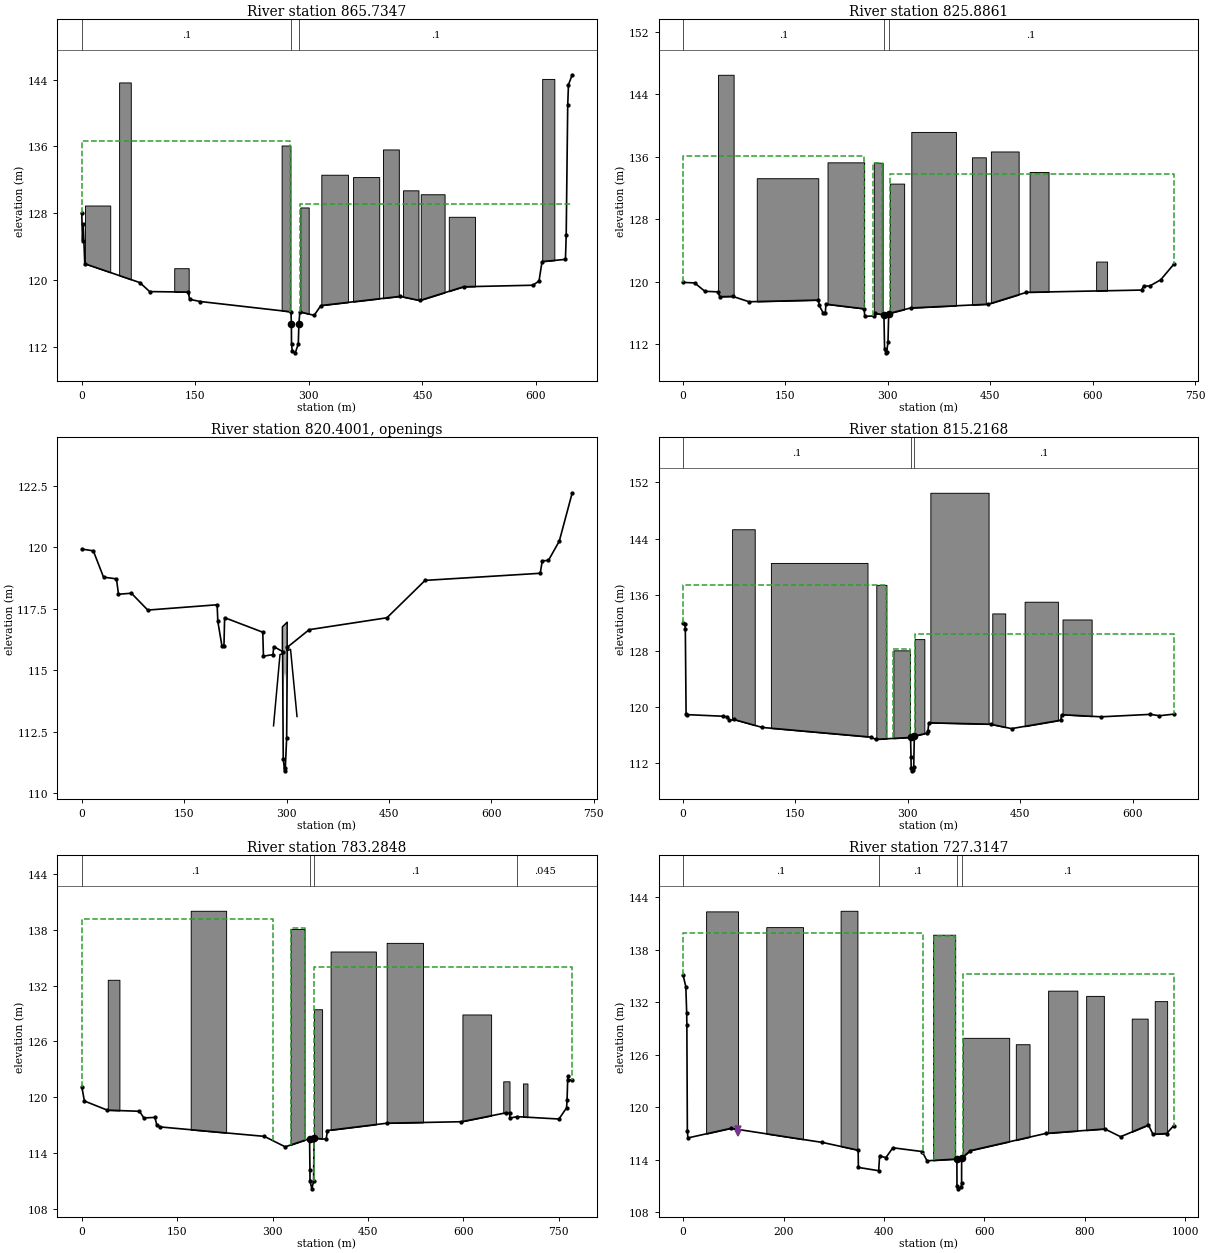
Type RM Length L Ch R = 1 ,865.7347,39.621,39.849,40.076
XS GIS Cut Line= 4
  529618.0033436 4779503.8384107  529859.0827122 4779535.7021122
  529978.1365122 4779480.0083122  530238.9980962 4779398.8858357
#Sta/Elev= 30
       0 128.019    .997 124.678   1.993  126.63   3.986 121.926   76.74 119.664
  89.696 118.587 140.524 118.529 142.517  117.66  156.47 117.398   276.3  116.16
 276.867 114.711 277.031 112.276 278.027 111.461  282.01 111.248 285.993 112.318
  286.78  114.76  288.02  116.16 306.903  115.74 315.865 116.918 420.475 118.012
 446.397  117.52 504.224 119.164 595.949  119.35 603.925 119.863 607.913 122.184
  638.82 122.448 639.817 125.358 641.811 140.912 642.808 143.382 647.793 144.567
#Mann= 3 ,-1 , 0
       0      .1       0 276.867    .036       0  286.78      .1       0
#XS Ineff= 2 , 0
          275.68  136.65  288.63          129.09
Permanent Ineff=
       T       T
#Block Obstruct= 12 ,-1
    4.32   37.62   128.9   49.34   64.76  143.65  122.11  141.23  121.39
  263.96  275.68  136.09  288.63  299.74  128.67  316.39  351.54  132.59
  358.33  392.86  132.31   397.8  418.77  135.62  424.32  444.67  130.72
  447.75  479.21  130.25  484.76   519.3  127.55  608.11  624.14  144.07
Bank Sta=276.867,286.78
XS Rating Curve= 0 ,0
Exp/Cntr=0.5,0.3

Type RM Length L Ch R = 1 ,825.8861,10.672,10.669,10.666
XS GIS Cut Line= 5
  529618.0033436 4779531.9609686  529863.5447122 4779574.2140122
  529998.4313122 4779521.0226122  530250.5580899 4779428.6984512
530302.9958227094779409.49672368
#Sta/Elev= 30
       0 119.925  16.942 119.853  31.891 118.784  50.827 118.714  53.816 118.089
  72.752  118.13   96.67 117.446 198.324 117.661  199.32 116.986   205.3 115.995
  208.29 115.982 209.286 117.137  265.15 116.546  266.15 115.573 280.149 115.635
 281.149 115.964  294.19  115.76 295.149 111.394 297.149 110.912 298.149 111.014
 300.148 112.255 301.148 115.935 333.147 116.649 447.047 117.133 502.943 118.652
671.5812118.9409 674.575119.4485683.5562119.4613699.5226120.2497718.4828122.2126
#Mann= 3 ,-1 , 0
       0      .1       0  294.19    .036       0 301.148      .1       0
#XS Ineff= 3 ,-1
       0  264.32  136.08  278.41  291.81  135.17  303.79718.4828  133.73
Permanent Ineff=
       T       F       T
#Block Obstruct= 10 ,-1
   51.19   74.01  146.48  107.93  197.97  133.25  211.54   265.2  135.28
  279.38  292.33  135.23  302.82  323.79  132.56  334.27  399.65  139.17
  423.08  443.44  135.92  450.84  491.54  136.67  507.58  535.33  134.05
  605.02  621.06  122.59
Bank Sta=294.19,301.148
XS Rating Curve= 0 ,0
Exp/Cntr=0.5,0.3

Type RM Length L Ch R = 4 ,820.4001,,,
BEGIN DESCRIPTION:
E157
END DESCRIPTION:
Bridge Culvert--1,0,-1,-1, 0
Deck Dist Width WeirC Skew NumUp NumDn MinLoCord MaxHiCord MaxSubmerge Is_Ogee
0.01,10.47,1.44,0, 30, 30, , , 0.95, 0, ,,,
 280.924 281.074 290.398 293.888   293.9 294.141 294.288 294.319 294.589 295.215
 295.788 296.679 297.312 297.505 297.866 298.567  298.85 299.368 300.028  300.53
  300.82 300.887 300.893   300.9 300.925 300.949 301.496 305.833 314.989  315.31
 112.742 112.788  115.64 115.662 116.764 116.771 116.775 116.775 116.783   116.8
 116.815 116.839 116.856 116.861 116.871  116.89 116.898 116.912  116.93 116.943
 116.951 116.953 115.798 115.799 115.799 115.799 115.805  115.85 113.214 113.121
 112.742  39.765  40.022  40.118  40.119  40.125 111.793  112.07 112.962 113.875
 114.349 114.761 114.882 114.894 114.887 114.759 114.661 114.401 113.869 113.192
 112.505 112.229 112.203 112.173 111.985 111.793  40.049  40.096  40.196 113.121
 289.324 289.474 298.798 302.288   302.3 302.541 302.688 302.719 302.989 303.615
 304.188 305.079 305.712 305.905 306.266 306.967  307.25 307.768 308.428  308.93
  309.22 309.287 309.293   309.3 309.325 309.349 309.896 314.233 323.389  323.71
 112.742 112.788  115.64 115.662 116.764 116.771 116.775 116.775 116.783   116.8
 116.815 116.839 116.856 116.861 116.871  116.89 116.898 116.912  116.93 116.943
 116.951 116.953 115.798 115.799 115.799 115.799 115.805  115.85 113.214 113.121
 112.742  39.765  40.022  40.118  40.119  40.125 111.793  112.07 112.962 113.875
 114.349 114.761 114.882 114.894 114.887 114.759 114.661 114.401 113.869 113.192
 112.505 112.229 112.203 112.173 111.985 111.793  40.049  40.096  40.196 113.121
BR Coef=-1 , 0 , 0 ,, 0 ,,,0.8,0,,0,
WSPro=,,,, 1 ,,,, 0 ,,,, 0 ,,,,-1 ,-1 ,-1 , 0 , 0 , 0 , 0 , 0
BC Mult= 1 ,0,294,0,303
BC Mult= 3 ,294,301,303,310
BC Mult= 1 ,301,800,310,700
BC Design=,, 0 ,, 0 ,,,,,,
BC Use User HTab Curves=0
BC User HTab FreeFlow(D)= 0

Type RM Length L Ch R = 1 ,815.2168,31.55,31.932,32.314
XS GIS Cut Line= 4
  529612.5951594 4779546.0222476  529864.7373122 4779585.2556122
  530002.5944122 4779530.7679122  530237.7812547 4779442.6921279
#Sta/Elev= 30
       0 131.904   1.994 131.876    2.99 131.142   3.987 118.983   4.984 118.905
  53.826 118.673   58.81 118.596    61.8 118.071  67.781 118.211 105.659  117.08
 250.192 115.708 257.166 115.377  303.55  115.65  304.17  112.88  304.32  111.27
 304.919 110.892  307.15  111.01  307.75  111.38  308.57  115.84 325.812 116.275
 326.807 116.614 327.802 117.747 410.388 117.536 438.292 116.912 504.067 118.111
 505.063 118.901 557.882 118.595 623.657 118.943 635.616 118.747 654.551 118.971
#Mann= 3 ,-1 , 0
       0      .1       0  303.55    .036       0  308.57      .1       0
#XS Ineff= 3 ,-1
       0  271.37   137.4     280   302.2  128.27  308.99 654.551  130.33
Permanent Ineff=
       T       F       T
#Block Obstruct= 9 ,-1
   65.37   95.59  145.33  117.18  246.08  140.53   257.8  271.37   137.4
  280.62  302.82  128.07  308.99  321.94  129.67  329.96  407.67  150.53
   412.6  429.87  133.33  455.77  500.18     135  506.34   545.2  132.47
Bank Sta=303.55,308.57
XS Rating Curve= 0 ,0
Exp/Cntr=0.5,0.3

Type RM Length L Ch R = 1 ,783.2848,55.975,55.97,55.965
XS GIS Cut Line= 4
529565.4379493024779556.04010312529874.3157043154779610.18368492
530065.5831284014779556.76071474530315.5498653964779489.48734489
#Sta/Elev= 30
       0 121.152    4.16 119.592  40.242 118.611  90.695  118.49  97.669 117.774
 114.976 117.831 117.991 117.016 122.909 116.808 286.884 115.794 319.843 114.669
  358.13  115.55 358.706 112.206  358.79  110.99 361.719  110.15 364.466  110.99
  365.09   115.6 384.211 115.486 386.233  116.42 479.934  117.21  596.92 117.367
 666.812 118.325 672.673 118.301 672.886 117.755 684.295 117.915 750.109 117.658
 762.116 118.856 762.932 119.722 764.017 122.281 764.564 121.806 771.037 121.891
#Mann= 4 ,-1 , 0
       0      .1       0 358.706    .036       0 364.466      .1       0
 684.295    .045       0
#XS Ineff= 3 ,-1
       0  300.97  139.17  329.16  350.31  138.19  364.41 771.037  134.03
Permanent Ineff=
       T       F       T
#Block Obstruct= 9 ,-1
   40.88   59.21  132.63  171.28  226.96  140.05  328.46  350.31  138.09
  365.11   377.8  129.46  391.19  462.38  135.67   479.3  536.39   136.6
  598.41  643.52   128.9  662.56  672.42  121.71  693.57  700.62  121.48
Bank Sta=358.13,365.09
XS Rating Curve= 0 ,0
Exp/Cntr=0.3,0.1

Type RM Length L Ch R = 1 ,727.3147,49.507,50.74,51.972
XS GIS Cut Line= 4
529391.3593944674779597.93329951529874.4377944674779668.28449951
530052.6609944674779618.25699951530345.0094944674779536.96219951
#Sta/Elev= 30
       0 135.108   5.469 133.775   7.163 130.745    7.49  129.43   8.501 117.308
   9.511 116.476   95.12 117.575 277.414 115.962 348.577 115.073 349.056 113.101
 389.478 112.728 391.341 114.405 403.876 114.234 417.773 115.351  475.94 114.919
  485.83 113.861 545.207  114.06 545.407  110.92 547.702 110.652 553.955 110.901
 554.593 111.307 554.658 114.168 571.959 115.022 722.183 116.991  839.82 117.505
  871.22 116.614 926.658 117.954 935.666 116.899 962.987 116.976 976.727 117.875
#Mann= 4 ,-1 , 0
       0      .1       0 389.478      .1       0 545.207    .036       0
 554.658      .1       0
Levee=-1,110.13,117.05,0,,,Levee 4,
#XS Ineff= 3 ,-1
       0  478.41  139.91  499.56  541.85  139.63  556.83 976.727  135.25
Permanent Ineff=
       T       F       T
#Block Obstruct= 10 ,-1
   45.81  109.25   142.4  165.64  238.77   140.6  313.66  347.14  142.47
   497.8  541.85  139.73  556.83  649.35  127.93  662.56  689.87   127.2
  726.87  785.02  133.33  802.64  837.89  132.73  893.39  925.11  130.13
  939.21  963.88  132.13
Bank Sta=545.207,554.658
XS Rating Curve= 0 ,0
Exp/Cntr=0.5,0.3