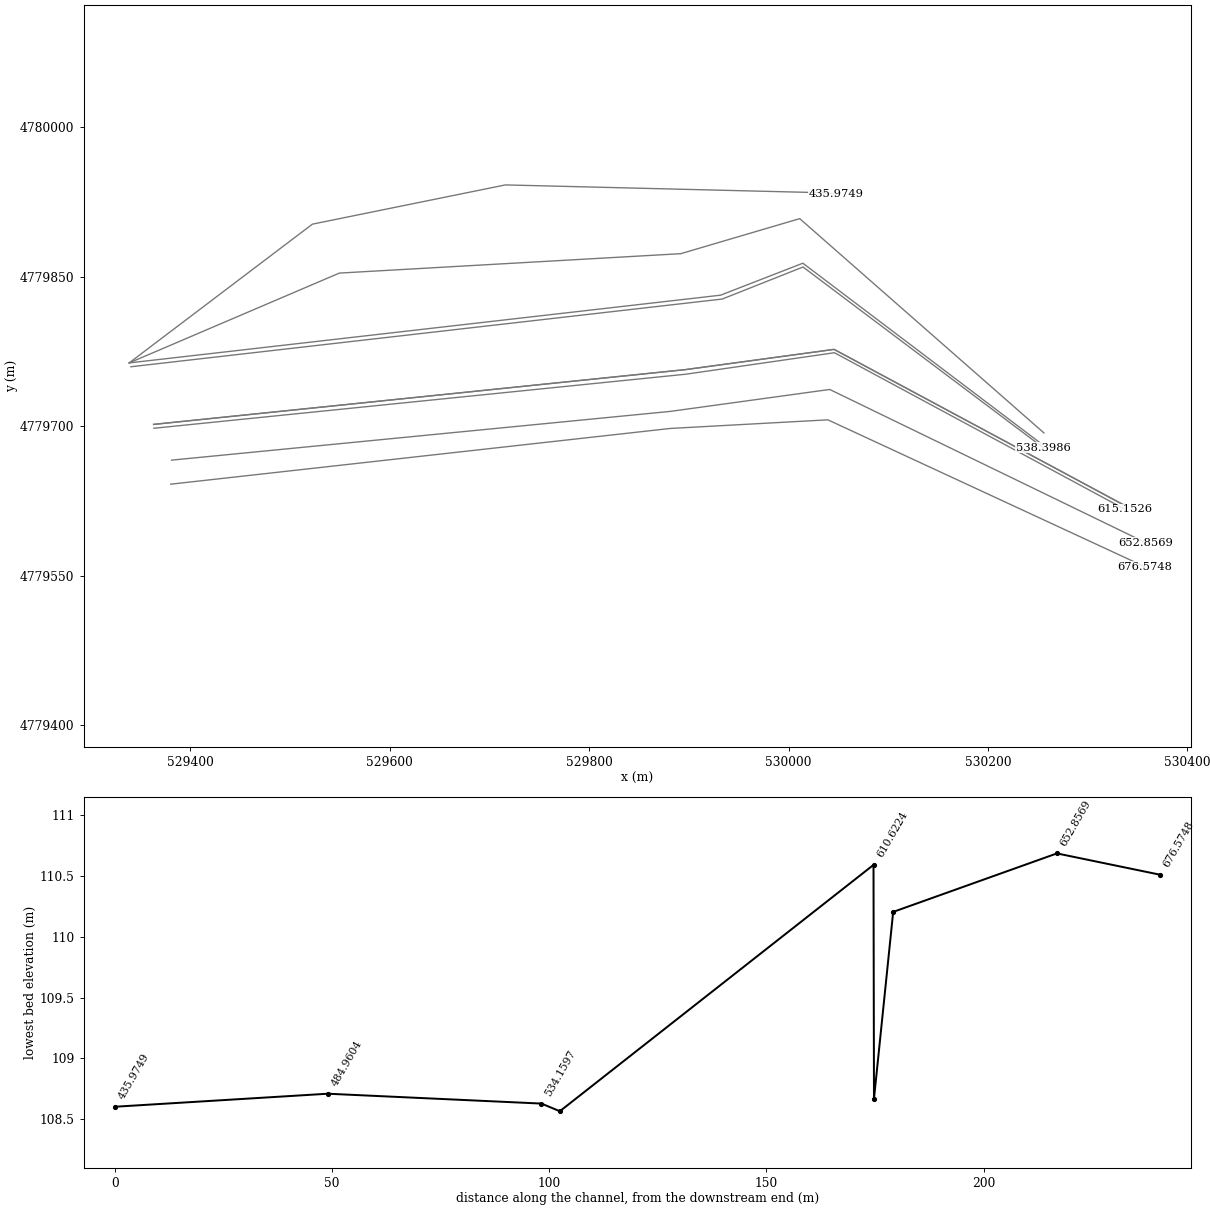
HEC-RAS study Durango.prj: Durango

--- Durango.g18 (geometry) --- (continued)

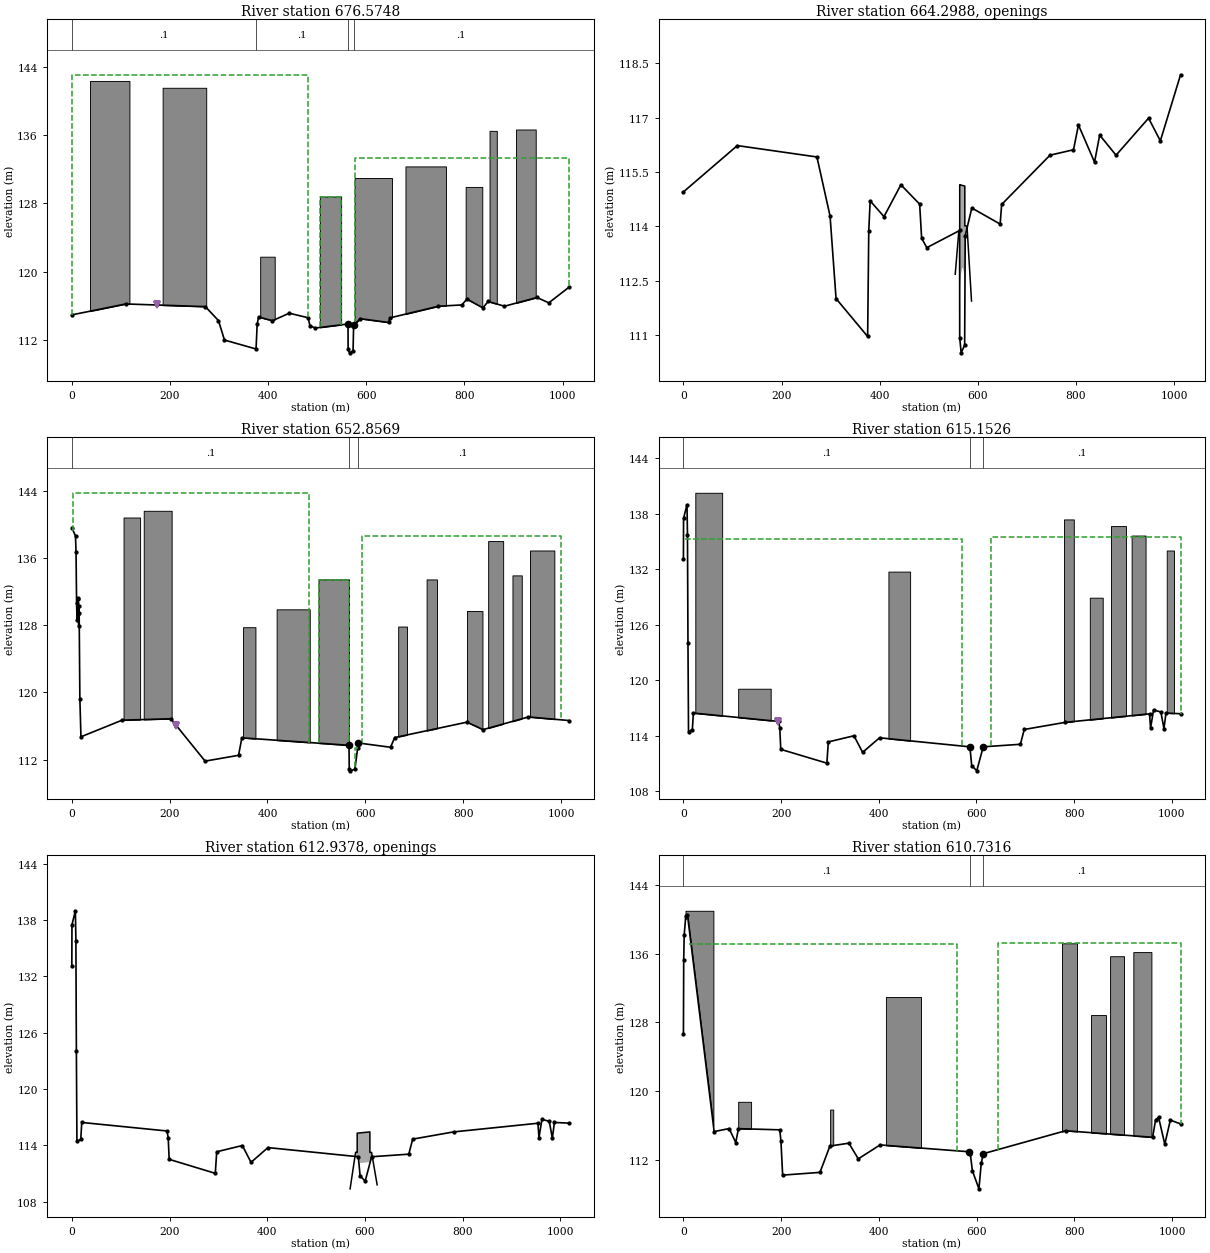
Type RM Length L Ch R = 1 ,676.5748,23.383,23.718,24.053
XS GIS Cut Line= 4
529380.415825951   4779641.70739529881.3778165774779697.60067324
530039.5064696534779706.24968232530357.5163321374779558.84926707
#Sta/Elev= 30
       0 114.951 109.791 116.229 272.033 115.915 298.799 114.283 310.998 112.007
 375.357 110.961 377.623  113.86 380.449 114.704 408.685 114.269 443.088 115.147
 481.323 114.614 485.348 113.676 495.887 113.412  562.79 113.886 562.937  110.93
 565.886  110.51 573.023 110.725  574.16  113.74 587.589 114.507 645.338 114.063
 648.398 114.604 746.896 115.964 794.783 116.114 804.912 116.797 837.635 115.773
 848.174 116.518 881.499 115.963 947.773 116.986 971.775 116.3591012.946 118.183
#Mann= 4 ,-1 , 0
       0      .1       0 375.357      .1       0  562.79    .036       0
  574.16      .1       0
Levee=-1,174.45,116.21,0,,,Levee 4,
#XS Ineff= 3 ,-1
    1.06  481.06  143.04  505.37  548.72  128.71  577.271012.946  133.29
Permanent Ineff=
       F       T       T
#Block Obstruct= 9 ,-1
      37  117.36  142.32  185.02  273.83  141.52  383.79  413.39  121.76
  505.37  548.72   128.8  576.21  652.33  130.96  679.82  762.29  132.32
  802.47   836.3  129.92   851.1   865.9  136.48  905.02   945.2  136.64
Bank Sta=562.79,574.16
XS Rating Curve= 0 ,0
Exp/Cntr=0.5,0.3

Type RM Length L Ch R = 4 ,664.2988,,,
BEGIN DESCRIPTION:
E158
END DESCRIPTION:
Bridge Culvert--1,0,-1,-1, 0
Deck Dist Width WeirC Skew NumUp NumDn MinLoCord MaxHiCord MaxSubmerge Is_Ogee
0.01,23.52,1.44,0, 21, 17, , , 0.95, 0, ,,,
 553.822 554.099 560.881 562.627 562.933 562.943  564.12 565.634 567.299 568.567
 569.972 571.199 572.806 573.362 573.393 574.535 574.835 574.971 577.777 586.853
 587.008
 112.678 112.723 113.833 113.848 113.851  115.15 115.145  115.14 115.134 115.129
 115.124  115.12 115.114 115.112 114.013 114.013 114.013 114.013 114.013 111.974
  111.94
 112.678  37.372  37.372  37.372 112.209 112.211 112.448 112.673 112.819  112.86
 112.835 112.753 112.558 112.454 112.449 112.236 112.168  36.788  36.768  36.701
  111.94
   564.5 565.815 565.978 566.168 566.661 567.112 574.466 574.503 577.242 577.256
 579.303 580.174 580.634 580.651  585.53 585.612  587.86
     130     130     130     130     130     130     130     130     130     130
     130     130     130     130     130     130     130
  -28.47  -28.47  -28.47  -28.47  -28.47 113.071 113.075 113.075 113.077 113.077
 113.078 -30.062 -30.067 -30.067 -30.113 -30.114 -30.135
BR Coef=-1 , 0 , 0 ,, 0 ,,,0.8,-1,,0,
WSPro=,,,, 1 ,,,, 0 ,,,, 0 ,,,,-1 ,-1 ,-1 , 0 , 0 , 0 , 0 , 0
BC Mult= 1 ,0,562.9,0,566.65
BC Mult= 3 ,562.9,575,566.65,585.37
BC Mult= 1 ,575,1100,585.37,1100
BC Design=,, 0 ,, 0 ,,,,,,
BC Use User HTab Curves=0
BC User HTab FreeFlow(D)= 0

Type RM Length L Ch R = 1 ,652.8569,37.639,37.704,37.769
XS GIS Cut Line= 4
529381.224641459 4779665.8273895529881.5290547374779714.72399602
530041.3255457834779736.71134618530358.3251476454779582.96926657
#Sta/Elev= 30
       0  139.61   7.498 138.594   8.587 136.692   9.724 130.621  10.596 128.622
  11.601 131.245  12.606 131.085  13.065 129.295  14.059  127.95  14.615 130.223
  14.974 129.499  16.406  119.28  18.633 114.732 102.844 116.709 202.378 116.875
 272.461  111.84 340.824 112.532 347.626 114.611  566.65  113.72 567.107 110.906
 568.545 110.685 578.681  110.87 584.173 113.359 585.368     114 651.471 113.487
 660.128 114.644 807.857 116.473 840.655 115.585 933.445 117.0931016.305 116.665
#Mann= 3 ,-1 , 0
       0      .1       0  566.65    .036       0 584.173      .1       0
Levee=-1,213.57,116.16,0,,,Levee 4,
#XS Ineff= 4 ,-1
    3.17  485.29  143.74  504.32  565.64  133.43   579.3  584.17   113.4
  594.18 1000.18  138.64
Permanent Ineff=
       T       F       T       T
#Block Obstruct= 11 ,-1
  105.73  139.56   140.8  146.96  204.05   141.6  349.96  375.33  127.76
  418.68  486.35129.8867  504.32   566.7  133.44  667.14  685.11  127.84
  725.29  746.43  133.44  807.75  839.47  129.68   851.1  881.76     138
  900.79  919.82  133.92  936.74  986.43  136.88
Bank Sta=566.65,585.368
XS Rating Curve= 0 ,0
Exp/Cntr=0.5,0.3

Type RM Length L Ch R = 1 ,615.1526,4.457,4.421,4.385
XS GIS Cut Line= 4
529363.5119871944779697.79295905529897.0812245524779752.02393555
530046.0695370654779773.55460023 530337.485771764779616.49819694
#Sta/Elev= 30
       0 133.078     .26 137.493   7.296 138.978   8.291 135.719   9.307 124.002
  10.415 114.434  18.277 114.642  20.363  116.45 194.975 115.542  197.27 114.843
 199.321 112.525 293.765 111.034 296.633  113.33 349.138 113.995 366.889 112.205
 401.543 113.775  586.55   112.8 590.261 110.775 600.628 110.204 613.805 112.801
 689.923 113.074 697.892 114.676 781.524 115.443 954.364 116.367 956.472 114.832
 962.643 116.782  977.55 116.568 983.873  114.78 988.089 116.4511017.899 116.377
#Mann= 3 ,-1 , 0
       0      .1       0  586.55    .036       0 613.805      .1       0
Levee=-1,194.54,115.46,0,,,Levee 4,
#XS Ineff= 2 ,-1
    4.23  570.93  135.22  629.08 1032.95  135.52
Permanent Ineff=
       T       T
#Block Obstruct= 8 ,-1
   24.32    79.3  140.26  112.07  178.68  119.08  419.74  464.14  131.74
  779.21   799.3  137.38  832.07   858.5  128.92  875.42  906.08  136.66
  917.71  946.26  135.64   989.6 1004.41  134.02
Bank Sta=586.55,613.805
XS Rating Curve= 0 ,0
Exp/Cntr=0.5,0.3

Type RM Length L Ch R = 4 ,612.9378,,,
BEGIN DESCRIPTION:
E159
END DESCRIPTION:
Bridge Culvert--1,0,-1,-1, 0
Deck Dist Width WeirC Skew NumUp NumDn MinLoCord MaxHiCord MaxSubmerge Is_Ogee
0.01,4.22,1.44,0, 14, 14, , , 0.95, 0, ,,,
 569.781 570.183 580.948 584.067 584.278 584.279 584.283  609.45 609.529 610.273
 610.293 613.709  624.97 625.157
 109.385 109.524 113.261 113.261 113.261 113.552 115.311 115.441 115.441 115.445
 113.261 113.263 109.867 109.811
 109.385   7.614   7.614   7.614 111.783 112.099 112.099 112.229   7.913   7.919
   7.919   7.944   8.025 109.811
 571.939 572.341 583.106 586.225 586.436 586.437 586.441 611.608 611.687 612.431
 612.451 615.867 627.128 627.315
 109.385 109.524 113.261 113.261 113.261 113.552 115.311 115.441 115.441 115.445
 113.261 113.263 109.867 109.811
 109.385   7.614   7.614   7.614 111.783 112.099 112.099 112.229   7.913   7.919
   7.919   7.944   8.025 109.811
BR Coef=-1 , 0 , 0 ,, 0 ,,,0.8,-1,,0,
WSPro=,,,, 1 ,,,, 0 ,,,, 0 ,,,,-1 ,-1 ,-1 , 0 , 0 , 0 , 0 , 0
BC Mult= 1 ,0,584,0,586
BC Mult= 3 ,584,609.5,586,612
BC Mult= 1 ,609.5,1100,612,1100
BC Design=,, 0 ,, 0 ,,,,,,
BC Use User HTab Curves=0
BC User HTab FreeFlow(D)= 0

Type RM Length L Ch R = 1 ,610.7316,0.109,0.109,0.109
XS GIS Cut Line= 4
 529363.219336214779701.61106935529896.702100321 4779756.5673175
530045.7241584914779776.85472287530337.1931207764779620.31630723
#Sta/Elev= 30
       0 126.692    .585  135.27    1.56 138.137   4.808 140.404    8.19 140.538
  62.883  115.32  93.607 115.671 107.056 114.051 112.659  115.66 197.178 115.525
 199.603 114.219   203.1 110.261 279.505  110.58 299.825 113.639 338.654 113.974
  357.87 112.152 402.526  113.77  583.81  112.98 587.171 112.743 591.462 110.761
 604.889 108.667 609.548 111.625 613.793 112.752 782.161 115.419 960.316 114.658
  966.47 116.686 972.635 116.963 985.288 113.855 996.639 116.657 1017.55 116.212
#Mann= 3 ,-1 , 0
       0      .1       0 587.171    .036       0 613.793      .1       0
#XS Ineff= 2 ,-1
   11.63  560.35  137.14  643.88 1018.15  137.26
Permanent Ineff=
       T       T
#Block Obstruct= 8 ,-1
    4.23   61.32  140.98  112.07   138.5  118.78  300.26  306.61  117.88
  414.45  486.34  130.96  774.98  805.64   137.2  834.18  864.85  128.86
   873.3  901.85   135.7  920.88  957.89  136.18
Bank Sta=583.81,613.793
XS Rating Curve= 0 ,0
Exp/Cntr=0.5,0.3

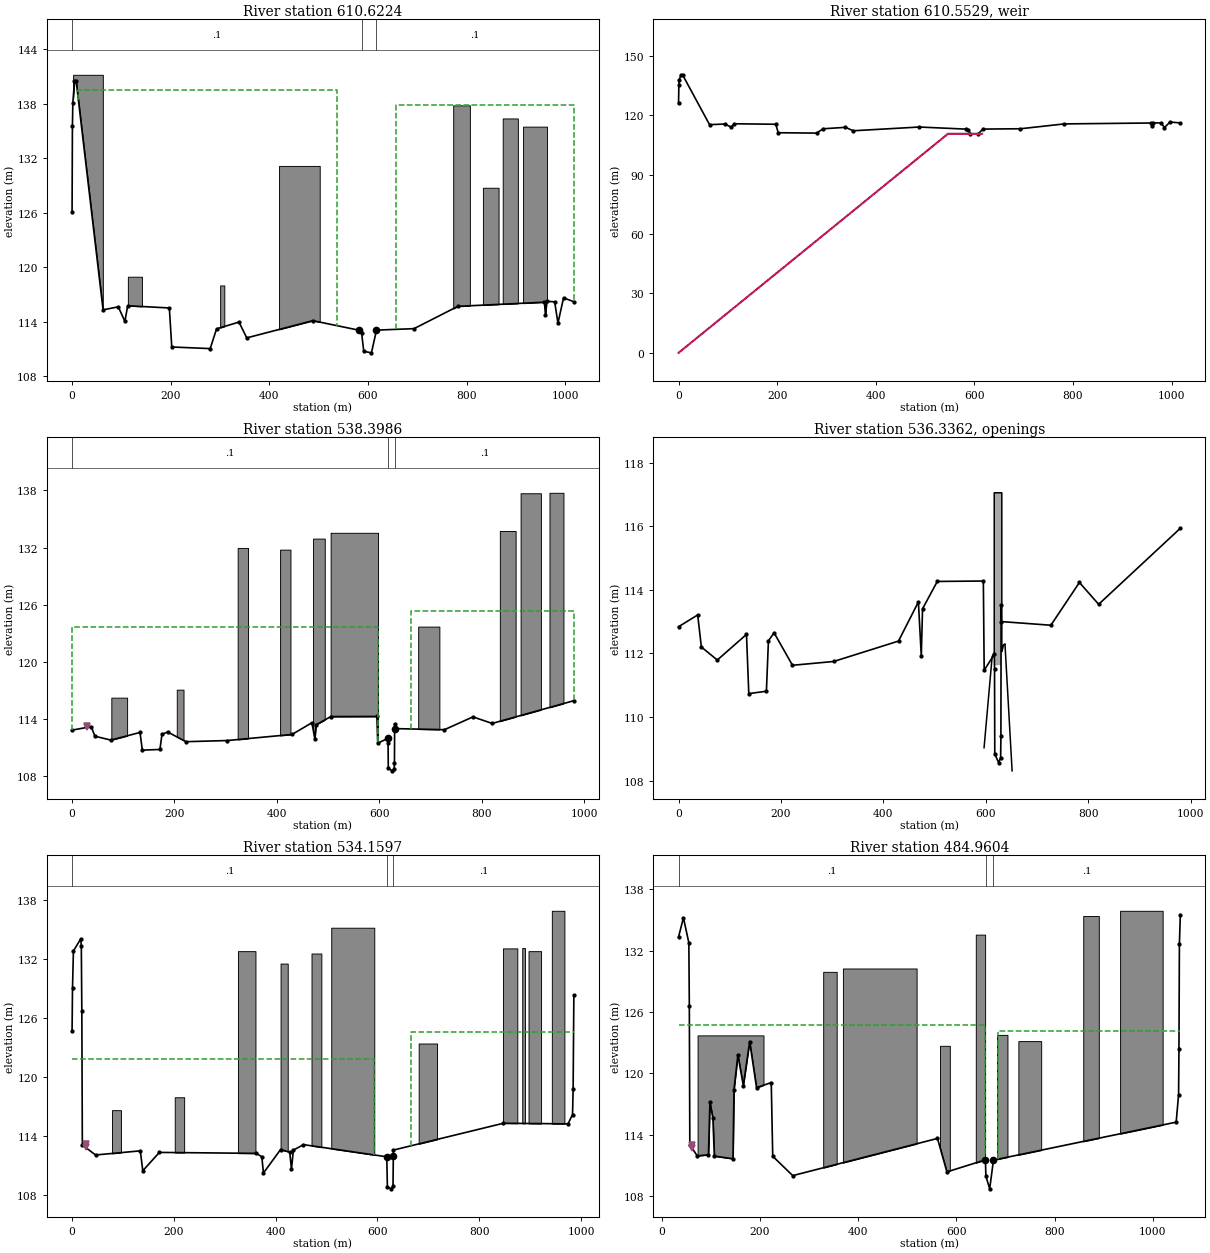
Type RM Length L Ch R = 1 ,610.6224,71.387,72.224,73.061
XS GIS Cut Line= 4
529363.2069387974779701.71016927529896.6897029074779756.66641742
530045.7117610784779776.95382279530337.1807233624779620.41540716
#Sta/Elev= 30
       0 126.043     .71 135.556   1.572 138.092   4.874 140.422   8.155 140.531
  62.895 115.318  93.731 115.647 107.128 114.053 112.784 115.767 197.243 115.525
 202.181 111.235 280.096 111.056 293.012 113.231 338.465 113.973 354.218 112.235
 488.233 114.128 582.549  113.07 587.214  112.74 591.496  110.76  607.07110.5906
 617.299 113.088 693.437  113.25 782.242 115.702 957.893  116.16 960.007 114.696
 962.431 116.256 978.603   116.2   985.3 113.855 996.651  116.641017.549 116.207
#Mann= 3 ,-1 , 0
       0      .1       0 587.214    .036       0 617.299      .1       0
#XS Ineff= 2 ,-1
   12.69  537.09  139.52  656.56 1023.44   137.8
Permanent Ineff=
       T       T
#Block Obstruct= 8 ,-1
    2.11   62.38  141.16  113.13  141.67  118.96  300.26  308.72     118
  419.74   502.2  131.14  772.86   806.7   137.8  833.13  864.85  128.74
   873.3  903.96  136.36  914.54  963.17  135.46
Bank Sta=582.549,617.299
XS Rating Curve= 0 ,0
Exp/Cntr=0.3,0.1

Type RM Length L Ch R = 5 ,610.5529,,,
BEGIN DESCRIPTION:
E160
END DESCRIPTION:
IW Pilot Flow=0
#Inline Weir SE= 8
       0       0  546.46  110.72  590.88  110.72  593.75  110.69  596.27  110.66
  597.45  110.69  609.23  110.74  615.51  110.74
IW Dist,WD,Coef,Skew,MaxSub,Min_El,Is_Ogee,SpillHt,DesHd
1,3.24,1.7,0,0.98,, 0 ,,,0,0,

Type RM Length L Ch R = 1 ,538.3986,4.268,4.239,4.21
XS GIS Cut Line= 4
529340.4758741344779759.48771593529933.5982441884779827.40540168
530014.5516588064779859.52930789530255.6787853644779678.14392849
#Sta/Elev= 30
       0 112.838  37.388 113.208  44.584 112.201  75.677 111.791 132.671 112.597
 137.186 110.736 171.562  110.81 175.527 112.396  186.54 112.647 222.501 111.626
 302.941 111.746 429.502 112.387 468.339 113.617 473.987  111.92 476.437 113.402
 505.249 114.262 595.159 114.275 596.799  111.47 616.536  111.97 617.003 111.506
 617.477 108.835 625.041 108.565 628.958 108.724  629.46 109.404 629.867 113.521
 630.235     113 727.018 112.885 782.721 114.229 820.314 113.543 979.774 115.933
#Mann= 3 ,-1 , 0
       0      .1       0 616.536    .036       0 630.235      .1       0
Levee=-1,28.19,113.31,0,,,Levee 5,
#XS Ineff= 2 , 0
          597.36  123.62  661.67           125.3
Permanent Ineff=
       T       T
#Block Obstruct= 10 ,-1
   76.65  107.49  116.25  204.41  217.62  117.09  323.35  343.61  131.97
  406.17  426.43  131.79  470.48  493.39  132.95  504.85  597.36  133.56
  675.77  717.18  123.71  835.24  866.08  133.75  875.77  915.42  137.71
  932.16  959.47  137.76
Bank Sta=616.536,630.235
XS Rating Curve= 0 ,0
Exp/Cntr=0.5,0.3

Type RM Length L Ch R = 4 ,536.3362,,,
BEGIN DESCRIPTION:
E161
END DESCRIPTION:
Bridge Culvert--1,0,-1,-1, 0
Deck Dist Width WeirC Skew NumUp NumDn MinLoCord MaxHiCord MaxSubmerge Is_Ogee
0.01,4.04,1.44,0, 18, 18, , , 0.95, 0, ,,,
 596.556  597.11 612.393 615.966 616.414 616.426 616.703 629.614 629.822 631.197
 631.258 631.764 632.957  634.54 637.375 637.378 651.218 651.317
 109.034 109.134 111.906 111.982 111.991 117.049 117.049 117.049 117.049 117.049
 112.061 112.081 112.157 112.269 112.297 112.298 108.336 108.308
 109.034  38.514  38.367  38.333   82.93  84.073 111.623 111.635  38.135  38.142
  38.142  38.144   38.15  38.157   38.17   38.17  38.234 108.308
 597.959 598.513 613.796 617.369 617.817 617.829 618.106 631.017 631.225   632.6
 632.661 633.167  634.36 635.943 638.778 638.781 652.621  652.72
 109.034 109.134 111.906 111.982 111.991 117.049 117.049 117.049 117.049 117.049
 112.061 112.081 112.157 112.269 112.297 112.298 108.336 108.308
 109.034  38.514  38.367  38.333   82.93  84.073 111.623 111.635  38.135  38.142
  38.142  38.144   38.15  38.157   38.17   38.17  38.234 108.308
BR Coef=-1 , 0 , 0 ,, 0 ,,,0.8,-1,,0,
WSPro=,,,, 1 ,,,, 0 ,,,, 0 ,,,,-1 ,-1 ,-1 , 0 , 0 , 0 , 0 , 0
BC Mult= 1 ,0,616,0,617
BC Mult= 3 ,616,631,617,633
BC Mult= 1 ,631,1100,633,1100
BC Design=,, 0 ,, 0 ,,,,,,
BC Use User HTab Curves=0
BC User HTab FreeFlow(D)= 0

Type RM Length L Ch R = 1 ,534.1597,49.546,49.199,48.853
XS GIS Cut Line= 4
529338.7178591254779763.33882777529931.8402291794779831.25651352
530014.4106060734779863.34119268530253.9207703564779681.99504033
#Sta/Elev= 30
       0 124.644    .854 129.001   2.656 132.789  17.164 134.026  18.171 133.262
  19.178 126.726  20.184  113.08  46.141 112.068 134.087 112.487 138.955 110.466
 171.573 112.328 362.324 112.231 372.913 111.877 376.018 110.235 409.713 112.617
 427.655 112.354 431.109  110.64 434.877 112.558 454.736 113.118 618.362 111.884
 619.593 108.818 626.957 108.628 630.633 108.918  631.25  111.93 631.255 112.562
 847.666 115.291 974.526 115.229 983.401 116.176 984.561 118.742 986.003 128.288
#Mann= 3 ,-1 , 0
       0      .1       0 618.362    .036       0 631.255      .1       0
Levee=-1,26.43,113.21,0,,,Levee 5,
#XS Ineff= 2 , 0
          593.83   121.8  666.96          124.55
Permanent Ineff=
       T       T
#Block Obstruct= 11 ,-1
   78.41   96.04  116.62  201.76  220.26  117.93  325.99  360.35  132.77
  409.69  423.79  131.51  470.48  489.87  132.53  509.25  593.83  135.15
  681.06  717.18  123.39   846.7  874.89  133.05  884.58  889.87  133.09
  896.92  921.59  132.77  942.73   967.4  136.87
Bank Sta=618.362,631.25
XS Rating Curve= 0 ,0
Exp/Cntr=0.5,0.3

Type RM Length L Ch R = 1 ,484.9604,50.2,48.985,47.77
XS GIS Cut Line= 5
  529338.7178591 4779763.3388278   529549.483359  4779853.422232
  529891.9278945 4779872.8893995    530011.24978 4779908.0390048
  530256.1909945 4779693.1028995
#Sta/Elev= 30
34.17831133.330544.17062135.211255.16195132.762556.16134126.629157.16056113.0367
 72.1487111.935695.13078112.034898.12852117.1859104.1239115.6292107.1215111.9099
145.0919111.6481147.0905 118.377155.0841121.8044166.0756118.8004179.0655123.1108
193.0545118.5979223.0312 119.099226.0289111.8923 266.796 110.001 561.589 113.637
 580.801 110.365 659.214 111.544 660.263  109.95 667.961 108.709  675.67  111.52
1047.789 115.228 1052.75 117.9171053.458 122.3571054.374 132.6351056.263 135.503
#Mann= 3 ,-1 , 0
34.17831      .1       0 660.263    .036       0  675.67      .1       0
Levee=-1,61.32,112.98,0,,,Levee 5,
#XS Ineff= 2 , 0
          658.68  124.74  684.05          124.09
Permanent Ineff=
       T       T
#Block Obstruct= 9 ,-1
   72.95  207.22  123.71  328.81   356.3  129.92  368.99  519.12  130.25
   566.7  586.78  122.69  639.65  658.68  133.56     683  704.14  123.76
  726.34  772.86  123.15   858.5  890.22  135.38  933.57 1020.26  135.89
Bank Sta=659.214,675.67
XS Rating Curve= 0 ,0
Exp/Cntr=0.5,0.3

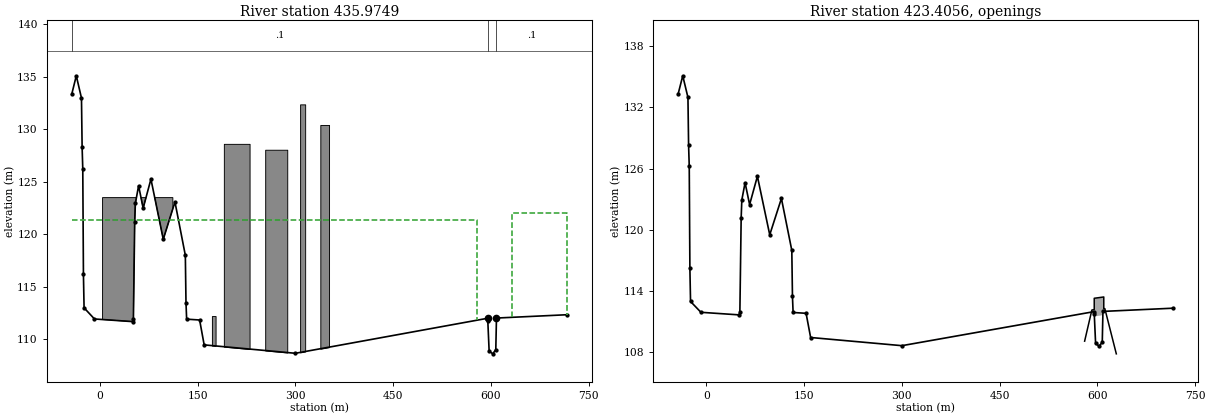
Type RM Length L Ch R = 1 ,435.9749,30.271,26.523,25.979
XS GIS Cut Line= 5
  529338.7178591 4779763.3388278  529522.5060944 4779902.5147313
  529716.0253771 4779941.8609755  530033.3876215 4779934.0441714
  530048.1290332 4779932.8157205
#Sta/Elev= 30
-43.0733133.3244-36.1013135.0827-28.1334132.9623-27.1374128.2688-26.1414126.2233
-25.1453116.2209-24.1495 112.983-8.21362111.922550.54966111.669751.54557111.9433
53.53761121.180154.53357122.921659.51349124.611166.48545122.470178.43729125.2399
97.36108 119.512115.2889123.0684131.2247117.9845132.2207113.4812133.2168111.9035
153.1365111.8251160.1084109.4549 300.122 108.655 595.109  111.99 595.289 111.756
 597.339 108.873 602.875 108.602 607.558 109.007   608.6  112.01  716.73 112.326
#Mann= 3 ,-1 , 0
-43.0733      .1       0 595.289    .036       0   608.6      .1       0
#XS Ineff= 2 , 0
          577.97  121.36  632.95          122.04
Permanent Ineff=
       T       T
#Block Obstruct= 6 ,-1
    4.23  112.07  123.48  171.98  177.62   112.2  190.31  229.78   128.6
  253.74  287.58  128.04  307.31  315.07  132.36  338.33  351.72   130.4
Bank Sta=595.109,608.6
XS Rating Curve= 0 ,0
Exp/Cntr=0.5,0.3

Type RM Length L Ch R = 4 ,423.4056,,,
BEGIN DESCRIPTION:
E162
END DESCRIPTION:
Bridge Culvert--1,0,-1,-1, 0
Deck Dist Width WeirC Skew NumUp NumDn MinLoCord MaxHiCord MaxSubmerge Is_Ogee
0.01,26.32,1.44,0, 14, 12, , , 0.95, 0, ,,,
 580.498 580.997 591.594 595.234 595.235 595.325 595.525 608.483 608.787 609.887
 609.893  611.53  628.95 629.111
 109.096 109.233 112.143 112.195 113.296 113.297 113.299 113.412 113.415 113.425
 112.276 112.278 107.896 107.855
 109.096  14.603  14.654  14.671  14.671  14.671 111.517 111.641  14.505  14.511
  14.511   14.52  14.619 107.855
 572.043 575.489 583.139 586.779  586.78  586.87  587.07 600.028 600.332 601.432
 601.438 601.896
 109.096 111.756 112.143 112.195 113.296 113.297 113.299 113.412 113.415 113.425
 112.276 112.278
 109.096  14.603  14.654  14.671  14.671  14.671 111.517 111.641  14.505  14.511
  14.511   14.52
BR Coef=-1 , 0 , 0 ,, 0 ,,,0.8,-1,,0,
WSPro=,,,, 1 ,,,, 0 ,,,, 0 ,,,,-1 ,-1 ,-1 , 0 , 0 , 0 , 0 , 0
BC Mult= 1 ,-200,595,-200,575
BC Mult= 3 ,595,610,575,602
BC Mult= 1 ,610,800,602,800
BC Design=,, 0 ,, 0 ,,,,,,
BC Use User HTab Curves=0
BC User HTab FreeFlow(D)= 0