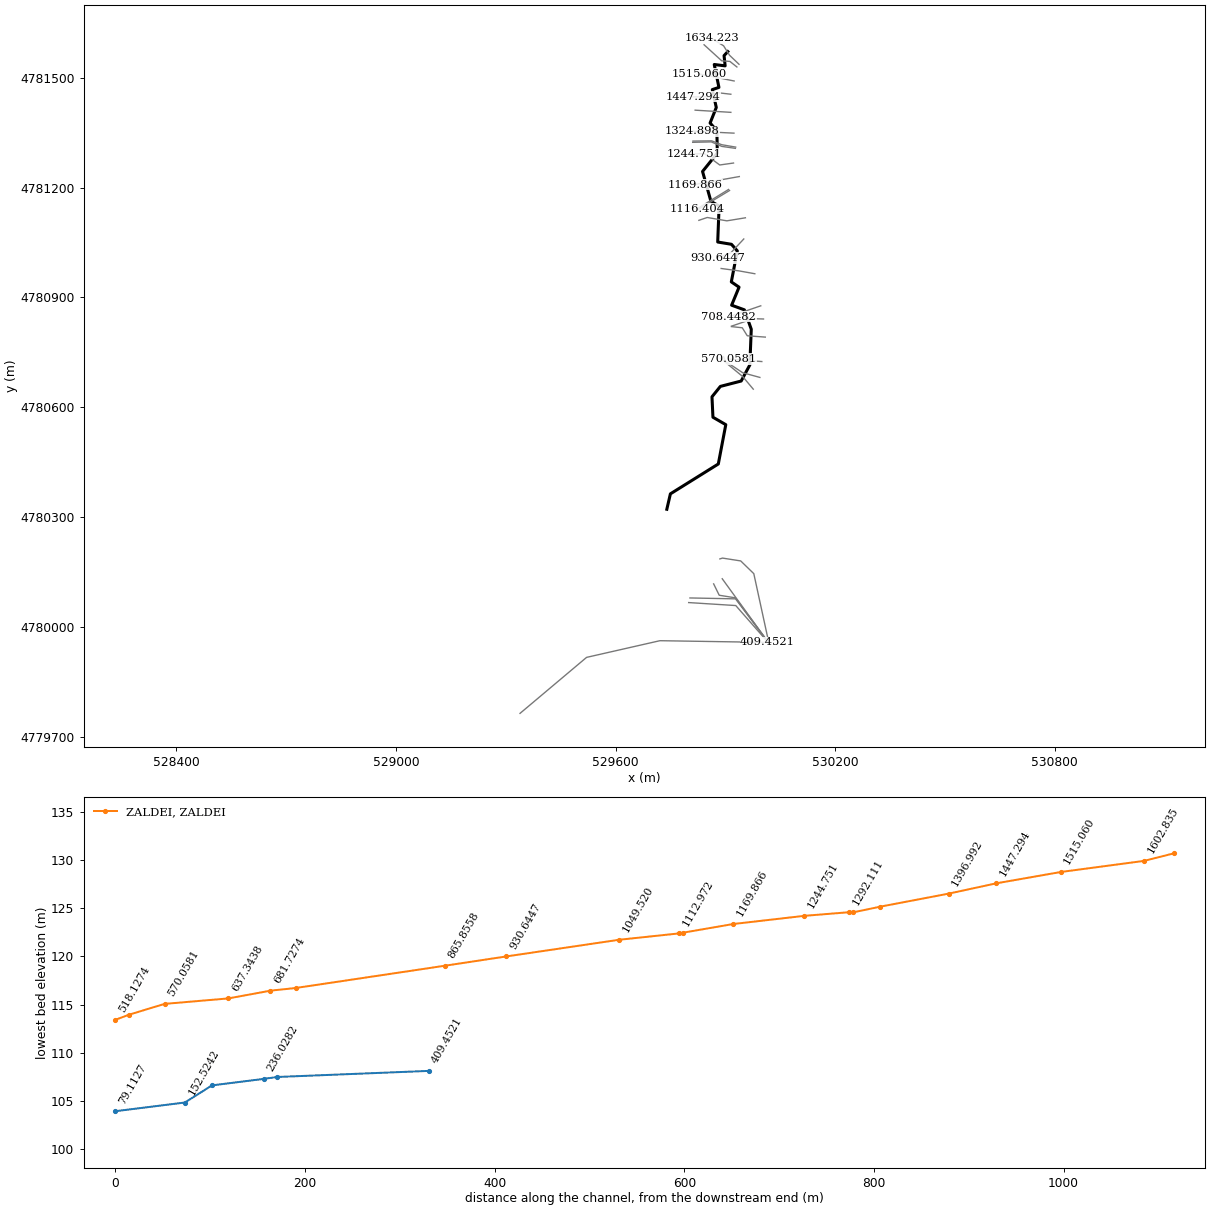
HEC-RAS study Durango.prj: Durango

--- Durango.g18 (geometry) --- (continued)

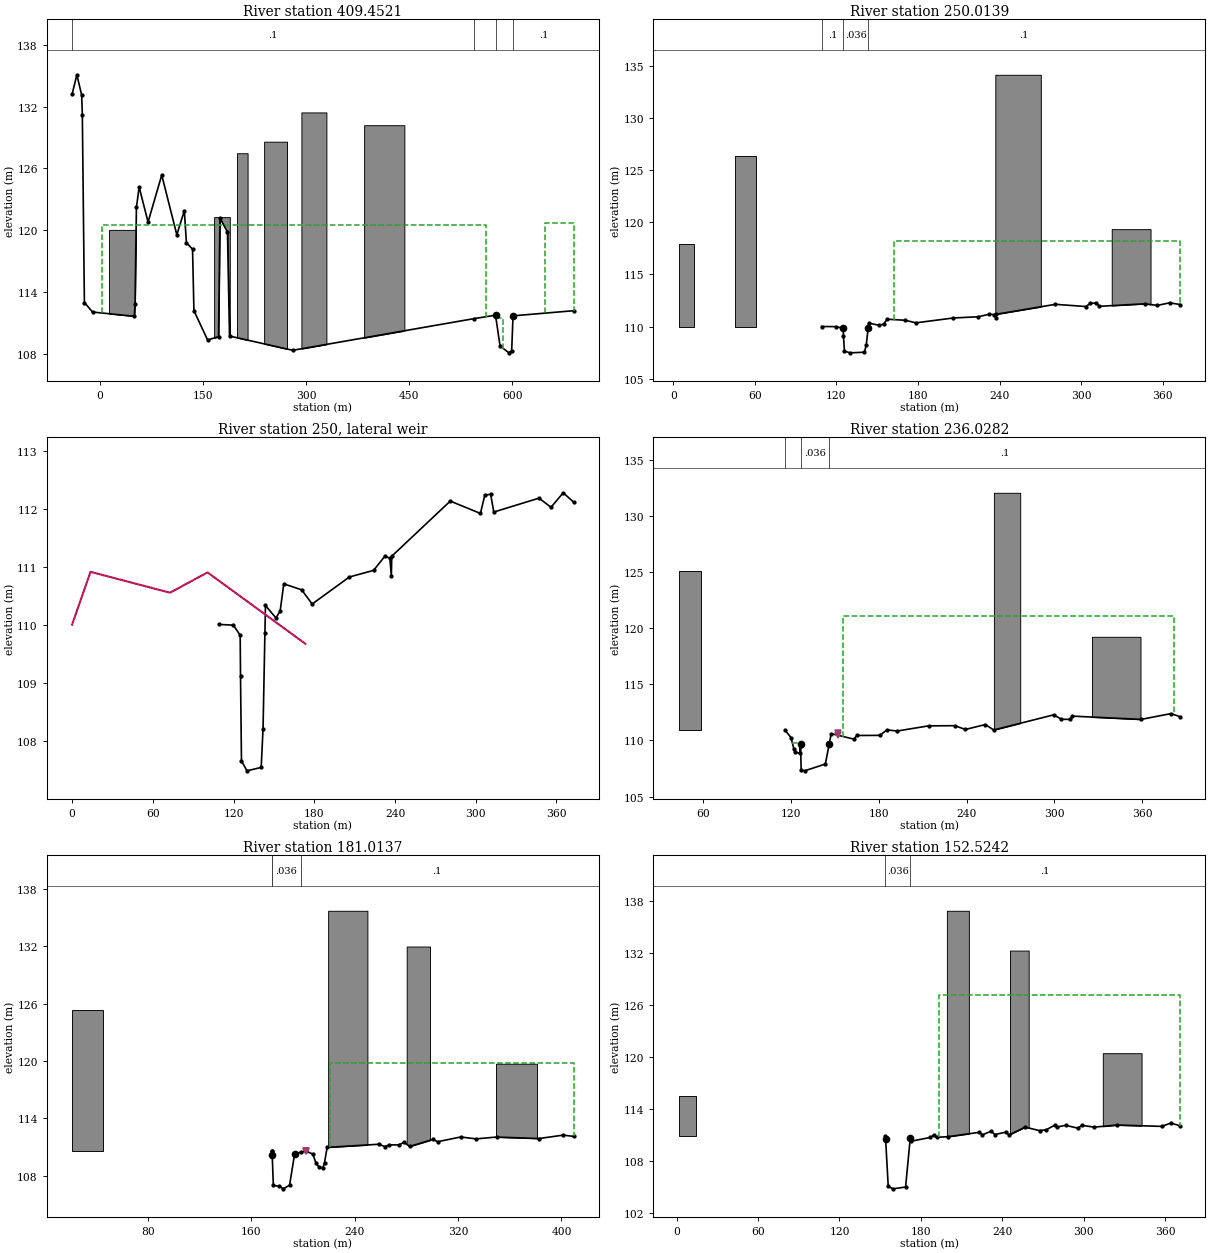
Type RM Length L Ch R = 1 ,409.4521,155.776,159.438,159.897
XS GIS Cut Line= 4
  529338.7178591 4779763.3388278  529520.5753641 4779916.3474176
  529721.0246765 4779961.9266511  530015.3155701 4779957.2228857
#Sta/Elev= 30
-40.8431 133.196-33.8684135.0917-26.8939133.1288-25.8975131.2055-22.9084112.9911
 -10.952112.067249.82646111.657850.82293112.849952.81567122.217756.80114124.1951
69.75388120.797189.68129125.3612111.6015119.5717122.5615121.9097125.5507118.8022
134.5178118.1618136.5107 112.205 156.438109.3527  172.38109.6815174.3727121.1847
185.3327119.8312188.3218109.7383 280.363 108.357 544.163 111.429  575.49 111.763
 582.103 108.765 595.093 108.109 599.017 108.322  600.98   111.7 689.513   112.2
#Mann= 4 ,-1 , 0
-40.8431      .1       0 544.163      .1       0  575.49    .036       0
  600.98      .1       0
#XS Ineff= 3 ,-1
    3.08  560.97  120.52   575.5  587.06  111.52  648.19  704.32  120.68
Permanent Ineff=
       T       T       T
#Block Obstruct= 6 ,-1
   12.95   94.36  120.04   165.9  188.72  121.28  199.21  214.63  127.48
  238.68  271.98   128.6  292.95  329.34  131.44  384.23  442.82   130.2
Bank Sta=575.49,600.98
XS Rating Curve= 0 ,0
Exp/Cntr=0.5,0.3

Type RM Length L Ch R = 1 ,250.0139,13.824,13.986,14.234
XS GIS Cut Line= 3
529799.5253113054780066.10345927  529928.2010995 4780057.9376079
  530018.8303771 4779954.7099672
#Sta/Elev= 30
 109.158 110.004 119.879 109.991 124.936 109.817 125.175 109.119 125.891 107.652
 129.996 107.481 140.546  107.54 141.923 108.204  143.32  109.86  143.72  110.33
  151.55 110.115 154.659 110.238 157.329 110.703 170.615   110.6 178.431 110.355
 206.052 110.821 224.088 110.935 232.354 111.176 236.155 111.147 237.266  110.84
 237.573 111.179 281.061 112.129 303.472 111.916 306.733 112.232 311.078 112.246
 313.393  111.94 347.051  112.18 355.909 112.022 365.015 112.272 372.908 112.107
#Mann= 3 ,-1 , 0
 109.158      .1       0 124.936    .036       0  143.32      .1       0
#XS Ineff= 2 , 0
       0                  162.47       0   118.2
Permanent Ineff=
       T       T
#Block Obstruct= 4 ,-1
    3.88   15.15  117.88   45.11   60.97  126.33  236.83  270.31  134.12
  322.47  351.01  119.33
Bank Sta=124.936,143.32
XS Rating Curve= 0 ,0
Exp/Cntr=0.5,0.3

Type RM Length L Ch R = 6 ,250     ,,,
Lateral Weir Pos= 0
Lateral Weir End=CORTA           ,MANA            ,244     ,
Lateral Weir Distance=0.1
Lateral Weir TW Multiple XS=0
Lateral Weir WD=1
Lateral Weir Coef=1.1
Lateral Weir WSCriteria= 0
Lateral Weir Flap Gates= 0
Lateral Weir Hagers EQN= 0 ,,,,,
Lateral Weir SS=0.05,0.05,
Lateral Weir Type= 0
Lateral Weir Connection Pos and Dist= 1 ,
Lateral Weir SE= 5
       0     110   13.72  110.91   72.79  110.55  100.65   110.9  173.42  109.67
Lateral Weir HW RS Station=250.0139,-0.1
Lateral Weir TW RS Station=221.1893,0
LW Div RC= 0 ,Falso,

Type RM Length L Ch R = 1 ,236.0282,59.069,55.014,50.874
XS GIS Cut Line= 3
529802.9885987114780078.71972836  529927.6494403 4780076.2486051
  530018.8303771 4779954.7099672
#Sta/Elev= 30
 116.128 110.909 120.129 110.254   122.2   109.2 123.129 108.967  126.13 108.845
 126.387  109.68 126.719  109.68 126.719 109.534 127.068 107.359 129.377 107.288
   143.6 107.891   146.2  109.66 147.595 110.605 163.128 110.114 165.111  110.44
 180.792 110.451 185.707 110.942 192.572 110.838 214.142 111.299 231.975 111.313
 239.231 110.978 252.854 111.416 258.541 110.932 299.539 112.282 304.797 111.886
 310.885 111.873 312.297 112.167 359.209 111.874 379.641 112.393 385.969 112.107
#Mann= 3 ,-1 , 0
 116.128      .1       0 126.719    .036       0   146.2      .1       0
Levee=0,,,-1,151.89,110.64,,Levee 45
#XS Ineff= 3 ,-1
                          120.98  126.72  109.79  155.77  381.32  121.08
Permanent Ineff=
       T       T       T
#Block Obstruct= 3 ,-1
   43.35    58.5  125.08  258.68  276.65  132.08  325.64  358.77  119.24
Bank Sta=126.719,146.2
XS Rating Curve= 0 ,0
Exp/Cntr=0.5,0.3

Type RM Length L Ch R = 1 ,181.0137,27.857,28.489,29.122
XS GIS Cut Line= 4
529867.7929792734780117.17036887  529882.9629365 4780086.1269614
  529926.8819324 4780079.0790513  530018.8303945 4779955.0140995
#Sta/Elev= 30
 175.631 110.551   175.8 110.551 176.095 110.108 176.967 106.956 181.653 106.882
 184.748 106.606 189.532 106.993 193.385 110.214 198.124 110.451 202.204 110.546
 207.467 110.252 210.081 109.275 212.291 108.903 215.316 108.796 216.578 109.348
 218.604 110.947 258.905 111.276  263.19  111.02 266.556 111.215 273.998 111.196
 278.127 111.468 282.576 111.045 300.336 111.773 304.258 111.539 321.895 112.033
 333.925 111.837 349.775 112.026 382.629 111.872 401.246 112.227   409.6 112.094
#Mann= 3 ,-1 , 0
 175.631      .1       0 176.095    .036       0 198.124      .1       0
Levee=0,,,-1,202.2,110.55,,Levee 45
#XS Ineff= 2 , 0
       0                  221.15       0  119.75
Permanent Ineff=
       T       T
#Block Obstruct= 4 ,-1
   21.15   45.37  125.35  219.38  249.78  135.71  280.18  298.24  131.97
  349.34  381.06   119.7
Bank Sta=176.095,193.385
XS Rating Curve= 0 ,0
Exp/Cntr=0.5,0.3

Type RM Length L Ch R = 1 ,152.5242,72.773,73.412,74.05
XS GIS Cut Line= 2
529891.2261719564780131.19742351530018.8303944674779955.01409951
#Sta/Elev= 30
 153.572   110.9  153.95  110.63 155.907 105.122 159.377 104.831 168.692 105.038
 172.106 110.647 172.524 110.319 187.029 110.764 189.449 111.036  191.95 110.773
 199.727 110.846 223.099 111.353 225.254  111.06 231.699 111.478 234.517 111.094
 242.785 111.379 244.856 111.045 256.743 111.953 267.361 111.547 272.462 111.651
 278.958 112.216 280.203 111.965 286.652 112.159 295.733 111.827 298.505 112.163
 307.471 111.949 324.653 112.192 357.372 112.036 364.093 112.418 371.112 112.094
#Mann= 2 ,-1 , 0
 153.572    .036       0 172.106      .1       0
#XS Ineff= 2 , 0
       0                  193.48       0   127.2
Permanent Ineff=
       T       T
#Block Obstruct= 4 ,-1
    1.41   14.45  115.52  199.12  215.33  136.91  245.64  259.38  132.32
  314.01  342.56  120.48
Bank Sta=153.95,172.106
XS Rating Curve= 0 ,0
Exp/Cntr=0.5,0.3

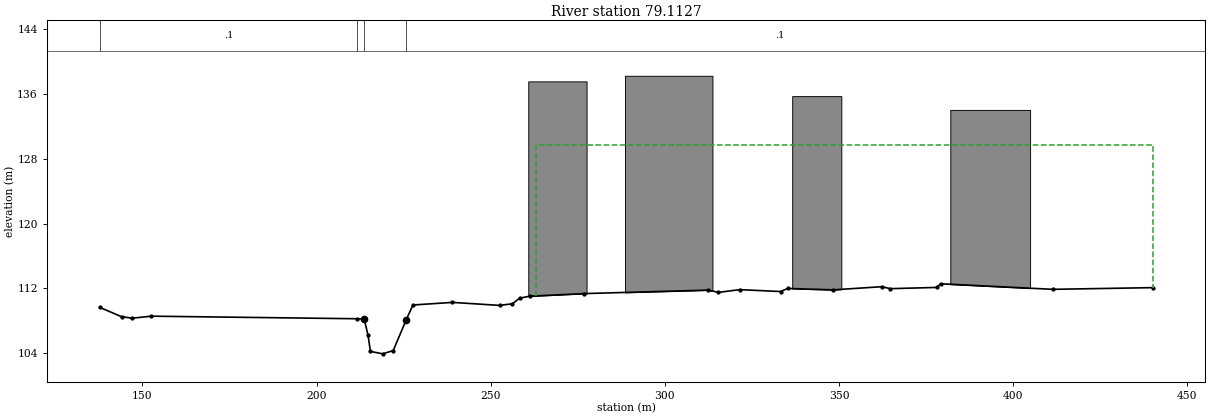
Type RM Length L Ch R = 1 ,79.1127 ,2.745,79.113,2.424
XS GIS Cut Line= 5
529884.7711181094780185.37600474529891.9294488114780187.66644447
529941.7404128934780179.86170102529977.4650783174780145.12543197
530018.8303770524779955.01406415
#Sta/Elev= 30
 137.743 109.665 144.043 108.507 147.123 108.326 152.631 108.573 211.671 108.256
 213.709   108.2 214.805 106.193 215.475 104.231 218.988 103.925 222.021  104.33
  225.78  108.15  227.69 109.954 239.011 110.273 252.592 109.904 256.235 110.104
 258.282 110.787 261.235 111.042 276.703 111.359 312.522 111.792  315.36 111.508
 321.507 111.847 333.249 111.615 335.264 111.993 348.341 111.823 362.391 112.212
 364.683 111.966  378.02 112.121 379.155 112.573 411.308 111.886 440.065 112.094
#Mann= 4 ,-1 , 0
 137.743      .1       0 211.671      .1       0 213.709    .036       0
  225.78      .1       0
#XS Ineff= 2 , 0
       0                     263       0  129.71
Permanent Ineff=
       T       T
#Block Obstruct= 4 ,-1
  260.79  277.53  137.55  288.55  313.66  138.24  336.56  350.66  135.73
  381.94  404.85  134.03
Bank Sta=213.709,225.78
XS Rating Curve= 0 ,0
Exp/Cntr=0.5,0.3

River Reach=ZALDEI          ,ZALDEI
Reach XY= 30
529906.4591250874781571.58886556529896.2269926294781560.51556704
529899.170334596 4781532.5766375 529869.395493094781536.26802227
529882.2078729534781473.68856711529864.0789712034781467.73358834
 529874.994000364781418.81025679529858.0825324774781376.38443457
529876.6094782544781355.36227653529877.7681511014781294.16394432
529837.4677692244781244.03711331529860.3789403334781162.22697346
529882.7149963534781149.63271312529878.8515152784781051.23841729
529916.4944804764781044.99002983529932.4267105244781027.02679177
529916.0409399274780942.33807657529937.165753379 4780927.8441089
  529916.85875384780878.62131407529951.6088079514780865.98752895
529970.5659223314780812.99945574529966.6501668324780715.41811962
529943.0098862314780671.42912907529886.1252745914780656.73712923
529863.1999197834780628.29369729529865.8496817654780572.49012575
529900.9456604944780552.19288379529880.5140470234780444.76570914
529749.5991199954780363.16857749529739.8320934474780321.04955443

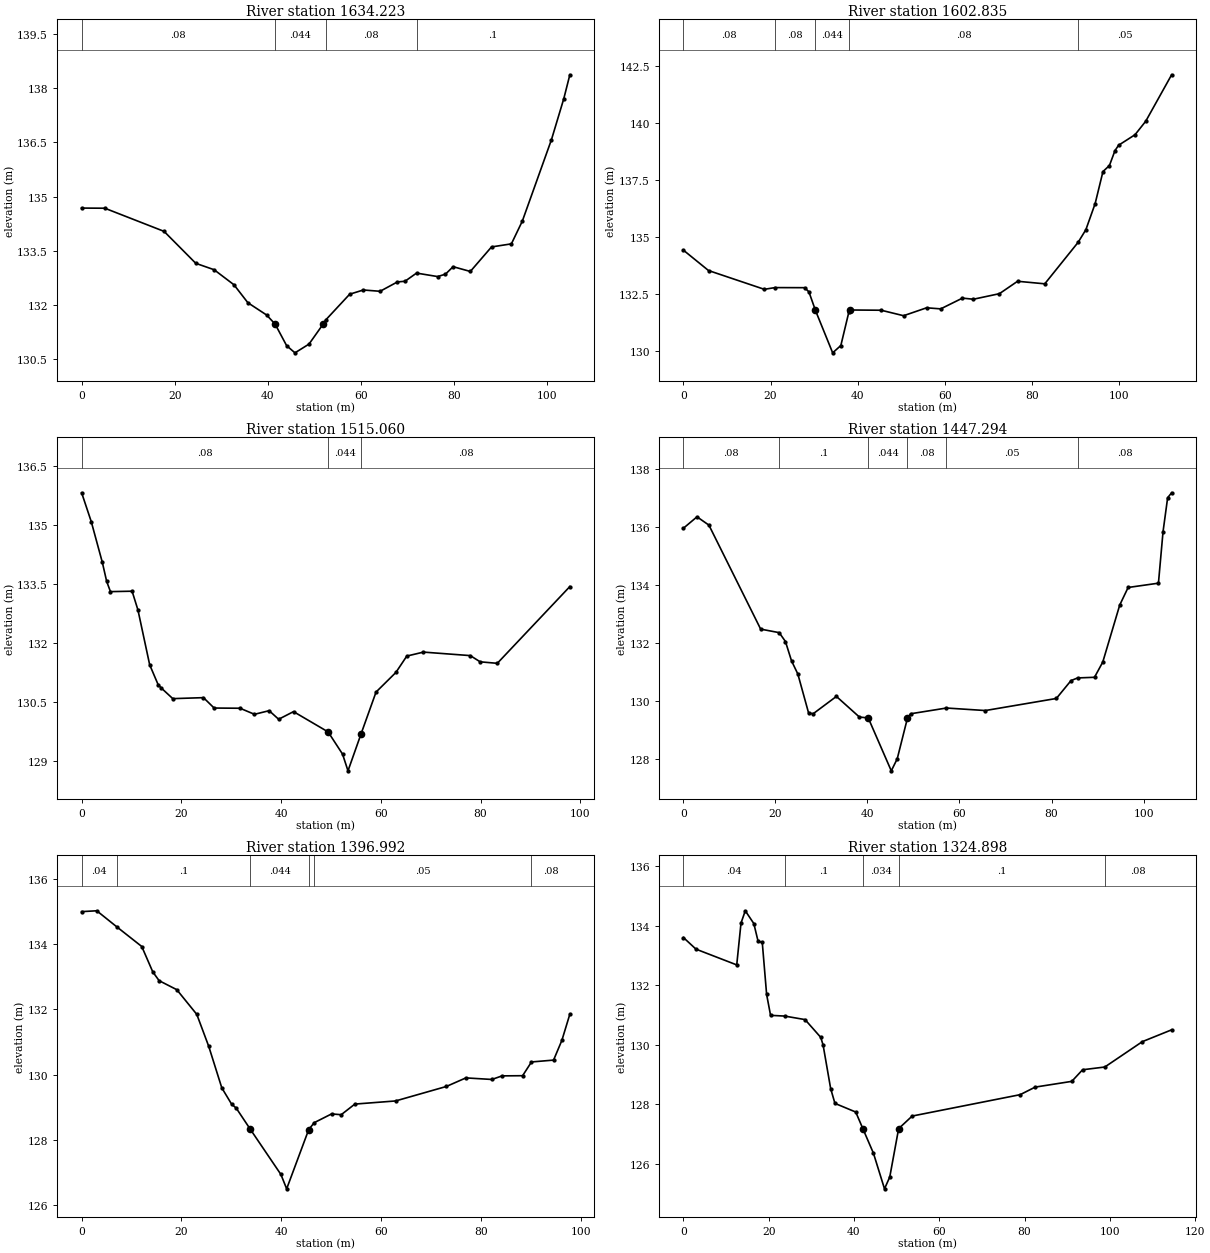
Type RM Length L Ch R = 1 ,1634.223,28.778,31.388,33.999
XS GIS Cut Line= 4
529937.0657684364781536.89882725529911.1564374544781561.61143811
529894.9383803974781587.31254102 529862.106708734781607.77458071
#Sta/Elev= 30
       0 134.682   4.977 134.678  17.709 134.038  24.522 133.155  28.459 132.978
  32.726 132.562  35.712 132.066  39.731 131.727  41.563 131.476   44.04 130.879
   45.83 130.681  48.847 130.923   51.91  131.48  52.395 131.584  57.578 132.301
  60.515 132.418  64.118 132.382  67.841 132.641  69.459 132.659  71.948 132.885
  76.471 132.789  78.161 132.855    79.8 133.062  83.503  132.93  88.054 133.608
  92.323 133.693  94.673 134.322 100.938 136.575 103.577 137.704 104.882 138.366
#Mann= 4 ,-1 , 0
       0     .08       0  41.563    .044       0  52.395     .08       0
  71.948      .1       0
Bank Sta=41.563,51.91
XS Rating Curve= 0 ,0
Exp/Cntr=0.3,0.1

Type RM Length L Ch R = 1 ,1602.835,88.086,87.775,87.463
XS GIS Cut Line= 4
529931.2821716974781529.56131776529912.123344114 4781544.7082304
529889.8168671254781546.36990405 529841.58434523 4781590.2392592
#Sta/Elev= 30
       0 134.418   5.758 133.522  18.558 132.696  21.021 132.772  27.785 132.768
  28.787 132.586  30.284  131.77  34.237 129.902  36.112 130.224  37.965 131.708
  38.137 131.787  45.366 131.776  50.502 131.535  55.787 131.883  59.019 131.836
  64.005 132.309  66.515  132.26  72.487 132.504  76.653  133.05  82.891 132.938
  90.544 134.764  92.321 135.319  94.445 136.466  96.239 137.876  97.725 138.142
  98.995 138.796  99.819 139.033 103.592 139.496 106.052  140.09  111.99 142.133
#Mann= 5 ,-1 , 0
       0     .08       0  21.021     .08       0  30.284    .044       0
  37.965     .08       0  90.544     .05       0
Bank Sta=30.284,38.137
XS Rating Curve= 0 ,0
Exp/Cntr=0.3,0.1

Type RM Length L Ch R = 1 ,1515.060,65.928,67.767,69.277
XS GIS Cut Line= 2
529923.6893838554781491.25924325 529827.717002664781510.62284179
#Sta/Elev= 30
       0 135.812    1.93 135.078   4.146 134.046   5.017 133.562   5.778 133.301
  10.118 133.312   11.29 132.836  13.644 131.443  15.337 130.939  15.928 130.858
  18.279 130.583  24.434 130.608   26.57 130.344  31.766 130.339  34.658 130.185
  37.605 130.277  39.509 130.059   42.49 130.253  49.425 129.738  52.324 129.174
  53.416 128.749  56.025 129.684   59.04  130.75  63.025 131.249  65.206 131.664
  68.547 131.765  77.941 131.676  79.922 131.518  83.357  131.48  97.906  133.43
#Mann= 3 ,-1 , 0
       0     .08       0  49.425    .044       0  56.025     .08       0
Bank Sta=49.425,56.025
XS Rating Curve= 0 ,0
Exp/Cntr=0.3,0.1

Type RM Length L Ch R = 1 ,1447.294,51.881,50.302,48.723
XS GIS Cut Line= 4
529914.7935944674781455.03299951529878.9182918594781459.24050571
529859.0491561534781447.97967035529811.9048944674781447.77799951
#Sta/Elev= 30
       0 135.963   2.955 136.357   5.542  136.07  16.789 132.476  20.818 132.354
  22.174 132.048  23.491 131.381   24.87 130.924  27.208 129.576  28.215 129.553
  33.249  130.15  38.256 129.436  40.167 129.407  45.177 127.578   46.47 127.994
    48.7 129.406   49.37  129.55  57.169 129.749  65.623 129.662   81.05 130.079
  84.239 130.697  85.669 130.789  89.343 130.811  91.138 131.337  94.832  133.31
   96.65 133.915 103.239 134.064 104.239 135.844 105.239 137.017 106.105 137.188
#Mann= 6 ,-1 , 0
       0     .08       0  20.818      .1       0  40.167    .044       0
    48.7     .08       0  57.169     .05       0  85.669     .08       0
Bank Sta=40.167,48.7
XS Rating Curve= 0 ,0
Exp/Cntr=0.3,0.1

Type RM Length L Ch R = 1 ,1396.992,72.062,72.094,72.126
XS GIS Cut Line= 2
529914.7935944674781405.56729951529817.1812944674781411.50309951
#Sta/Elev= 30
       0 134.995   3.029 135.021   7.002 134.534  12.045 133.927  14.247 133.151
  15.519 132.881  19.058 132.605  23.066 131.849  25.466 130.867  28.075 129.599
  30.028 129.103  30.971 128.977   33.79  128.33  39.912 126.948  41.067 126.507
  45.487 128.322  46.589 128.533  50.062 128.801  51.996 128.777  54.726 129.102
  62.882 129.198  73.068 129.642  76.964 129.904  82.175 129.856  84.216 129.966
   88.33 129.971  90.107 130.392  94.533 130.449    96.2 131.055  97.793 131.855
#Mann= 6 ,-1 , 0
       0     .04       0   7.002      .1       0   33.79    .044       0
  45.487      .1       0  46.589     .05       0  90.107     .08       0
Bank Sta=33.79,45.487
XS Rating Curve= 0 ,0
Exp/Cntr=0.3,0.1

Type RM Length L Ch R = 1 ,1324.898,29.98,29.118,28.257
XS GIS Cut Line= 2
 529923.259247844781348.71877596529808.9156704654781354.30976812
#Sta/Elev= 30
       0 133.601   2.952  133.21  12.503 132.681  13.504 134.086  14.505   134.5
  16.508 134.071  17.509 133.475  18.491 133.435  19.511 131.688  20.436 130.986
  23.755 130.961  28.522 130.843  32.201 130.246  32.753 129.989  34.529 128.523
   35.53 128.027  40.409 127.736   42.07  127.18  44.561 126.351  47.153 125.155
  48.387 125.553  50.467 127.178  53.639 127.601  78.969  128.32   82.48 128.574
  91.071 128.767    93.6 129.157  98.807 129.249 107.616 130.102  114.48 130.499
#Mann= 5 ,-1 , 0
       0     .04       0  23.755      .1       0   42.07    .034       0
  50.467      .1       0  98.807     .08       0
Bank Sta=42.07,50.467
XS Rating Curve= 0 ,0
Exp/Cntr=0.5,0.3

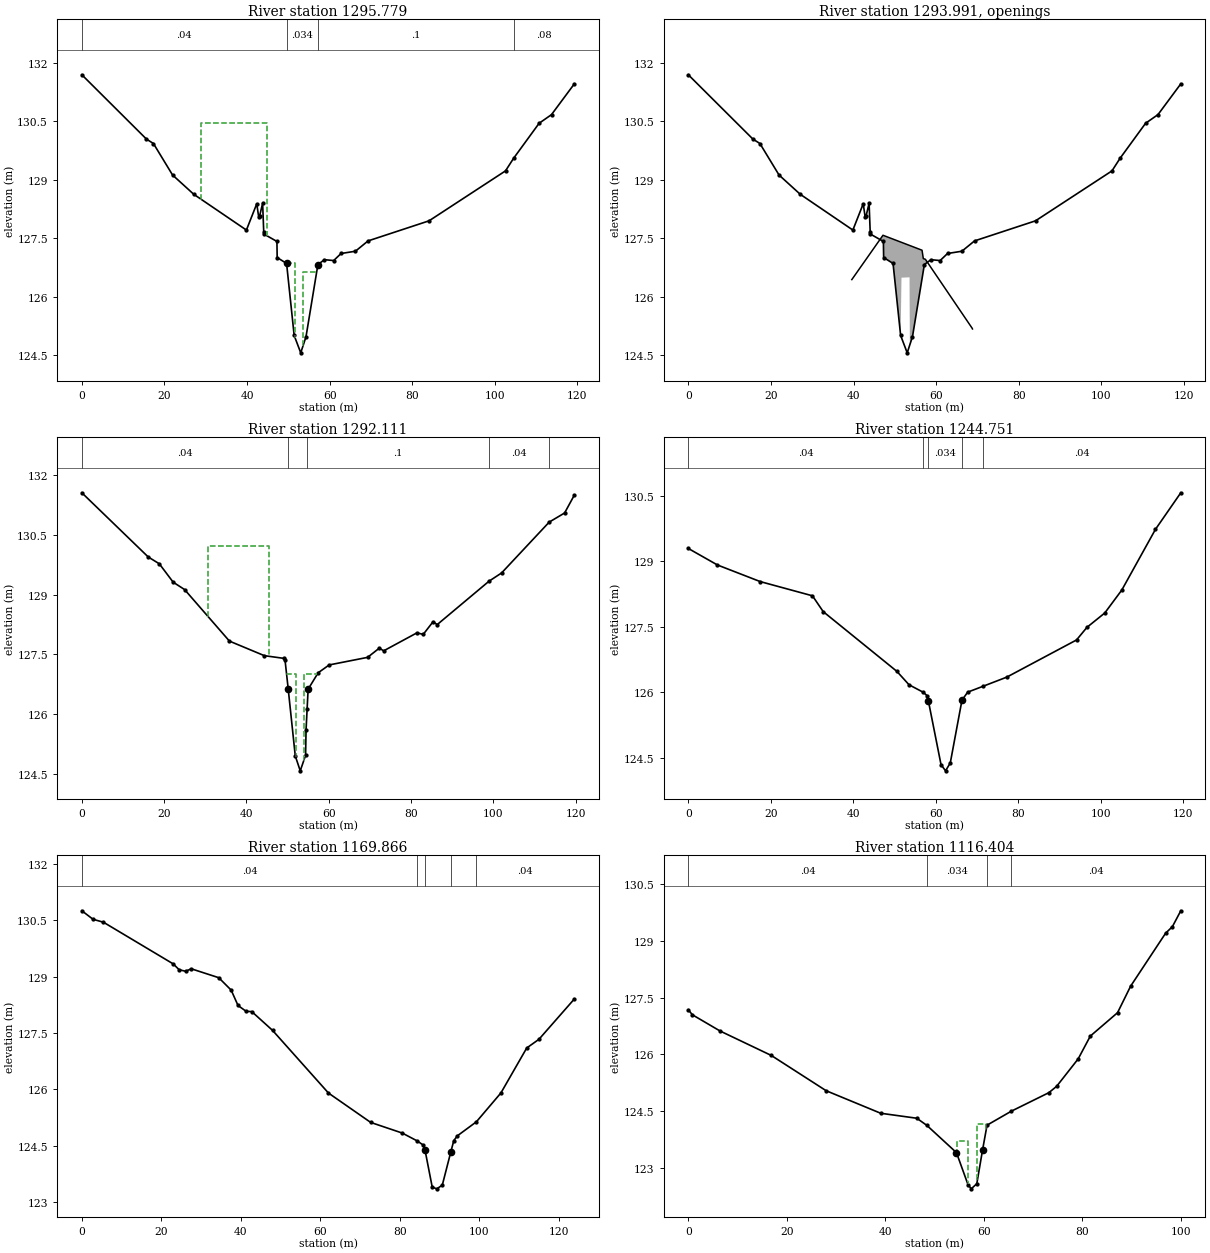
Type RM Length L Ch R = 1 ,1295.779,3.782,3.668,3.554
XS GIS Cut Line= 4
529927.9844574894781310.59309432529890.0485033454781317.09750845
529862.2287655354781327.70991507529811.2453745134781327.08166537
#Sta/Elev= 30
       0 131.687  15.645 130.037  17.333 129.924  21.974 129.115  27.085 128.623
  39.846 127.704  42.353 128.378   42.82 128.041  43.067 128.075  43.774  128.39
  44.044 127.647  44.112   127.6  47.237 127.412  47.298 126.999  49.575 126.848
  51.413     125  53.004 124.555  54.282  124.97   57.16  126.82  58.745 126.944
   60.98 126.922  62.768 127.103  66.241 127.161  69.306 127.426  84.073 127.941
 102.586 129.222  104.56 129.547 110.725 130.443 113.726 130.665 119.252 131.454
#Mann= 4 ,-1 , 0
       0     .04       0  49.575    .034       0   57.16      .1       0
  104.56     .08       0
#XS Ineff= 3 ,-1
   28.97   44.93  130.45   49.58   51.62  126.85   53.57   56.85  126.62
Permanent Ineff=
       T       T       T
Bank Sta=49.575,57.16
XS Rating Curve= 0 ,0
Exp/Cntr=0.5,0.3

Type RM Length L Ch R = 4 ,1293.991,,,
BEGIN DESCRIPTION:
E178
END DESCRIPTION:
Bridge Culvert--1,0,-1,-1, 0
Deck Dist Width WeirC Skew NumUp NumDn MinLoCord MaxHiCord MaxSubmerge Is_Ogee
0.01,3.47,1.44,0, 12, 13, , , 0.95, 0, ,,,
   39.59  39.919  47.135  51.399   51.62  53.567  53.646  56.594  56.907  57.407
  68.699  68.806
 126.434 126.483 127.571 127.398 127.389  127.31 127.307 127.187 126.972 126.954
 125.191 125.168
 126.434  93.181   93.14  93.116 126.483 126.492  93.045  93.052  93.053  93.054
  93.083 125.168
  39.911   40.24  47.456   51.72  51.941  53.888  53.967  56.915  57.228  57.728
  60.275   69.02  69.127
 126.434 126.483 127.571 127.398 127.389  127.31 127.307 127.187 126.972 126.954
 127.112 125.191 125.168
 126.434  93.181   93.14  93.116 126.483 126.492  93.045  93.052  93.053  93.054
  93.061  93.083 125.168
BR Coef=-1 , 0 , 0 ,, 0 ,,,0.8,0,,0,
WSPro=,,,, 1 ,,,, 0 ,,,, 0 ,,,,-1 ,-1 ,-1 , 0 , 0 , 0 , 0 , 0
BC Mult= 1 ,0,47,0,49
BC Mult= 3 ,47,58,49,58
BC Mult= 1 ,58,130,58,130
BC Design=,, 0 ,, 0 ,,,,,,
BC Use User HTab Curves=0
BC User HTab FreeFlow(D)= 0

Type RM Length L Ch R = 1 ,1292.111,47.997,47.36,46.722
XS GIS Cut Line= 4
529927.1956496354781307.14537362529889.9861771124781312.53410115
529861.3705578914781324.82509883529810.4565666594781323.63394467
#Sta/Elev= 30
       0 131.559  16.137 129.947  18.818 129.777  22.191 129.315  24.962  129.13
  35.862 127.836  44.339 127.471  49.222 127.401  49.365 127.367   50.15  126.63
  51.859 124.954  53.069  124.58  54.365  124.97  54.482 125.604  54.743 126.141
  54.983 126.629  57.423 127.041  60.096 127.238  69.426 127.428  72.291  127.66
  73.343 127.592  81.401 128.042  82.962 128.006  85.346 128.323  86.346  128.25
  98.943  129.34 101.998 129.547 113.566 130.823 117.307 131.052 119.669   131.5
#Mann= 5 ,-1 , 0
       0     .04       0   50.15    .034       0  54.743      .1       0
  98.943     .04       0 113.566     .08       0
#XS Ineff= 3 ,-1
   30.77   45.57  130.22   49.63   51.94     127   53.89   57.23     127
Permanent Ineff=
       T       T       T
Bank Sta=50.15,54.983
XS Rating Curve= 0 ,0
Exp/Cntr=0.5,0.3

Type RM Length L Ch R = 1 ,1244.751,72.612,74.885,77.157
XS GIS Cut Line= 4
529922.0485944674781267.06329951529884.3409929364781261.73268353
529842.7153417034781292.61303422529813.2239944674781292.12589951
#Sta/Elev= 23
       0 129.289   7.064 128.911  17.446 128.531  30.101 128.206  32.707 127.844
  50.577 126.477  53.511 126.171   56.91 126.002  57.904 125.921   58.21   125.8
  61.273 124.344  62.371 124.202  63.518 124.383  66.351 125.819  67.733 126.002
  71.394 126.134  77.221 126.346  94.129 127.196  96.648 127.484 100.974 127.813
 105.098 128.337 113.274 129.728 119.407 130.563
#Mann= 5 ,-1 , 0
       0     .04       0   56.91      .1       0   58.21    .034       0
  66.351      .1       0  71.394     .04       0
Bank Sta=58.21,66.351
XS Rating Curve= 0 ,0
Exp/Cntr=0.3,0.1

Type RM Length L Ch R = 1 ,1169.866,52.371,53.462,54.489
XS GIS Cut Line= 2
529937.8775944674781230.12889951529815.8621944674781208.36399951
#Sta/Elev= 30
       0 130.755   2.823 130.528   5.436  130.45   22.98 129.342  24.487 129.186
  26.114 129.145  27.535 129.211  34.455 128.974   37.58 128.643  39.304 128.234
   41.34 128.079  42.772 128.071  47.991 127.572  62.072 125.903  72.692 125.122
  80.628 124.839  84.355 124.632  85.853 124.524  86.363 124.387  88.177 123.401
  89.331 123.354  90.715 123.453   92.84  124.33  93.605 124.637  94.504 124.765
   99.29 125.138  105.47 125.907 111.963 127.103 115.038 127.334 123.942 128.407
#Mann= 5 ,-1 , 0
       0     .04       0  84.355      .1       0  86.363    .034       0
   92.84      .1       0   99.29     .04       0
Bank Sta=86.363,92.84
XS Rating Curve= 0 ,0
Exp/Cntr=0.5,0.3

Type RM Length L Ch R = 1 ,1116.404,3.536,3.432,3.41
XS GIS Cut Line= 2
529908.4724627954781194.80945496529823.3251716064781142.42997882
#Sta/Elev= 24
       0  127.18    .823 127.049   6.447  126.62  16.843 125.974  27.987 125.041
  39.047 124.446  46.379 124.314  48.424 124.125  54.432 123.405  56.772  122.56
  57.435 122.448  58.561 122.584   59.72  123.47  60.637 124.131  65.589 124.502
   73.19  124.99  74.765 125.158  79.137 125.883  81.603 126.486  87.129 127.104
  89.788 127.806  96.879 129.204   98.27  129.38  99.968 129.798
#Mann= 4 ,-1 , 0
       0     .04       0  48.424    .034       0  60.637      .1       0
  65.589     .04       0
#XS Ineff= 2 ,-1
   54.62    56.7   123.7   58.69   60.47  124.15
Permanent Ineff=
       T       T
Bank Sta=54.432,59.72
XS Rating Curve= 0 ,0
Exp/Cntr=0.5,0.3

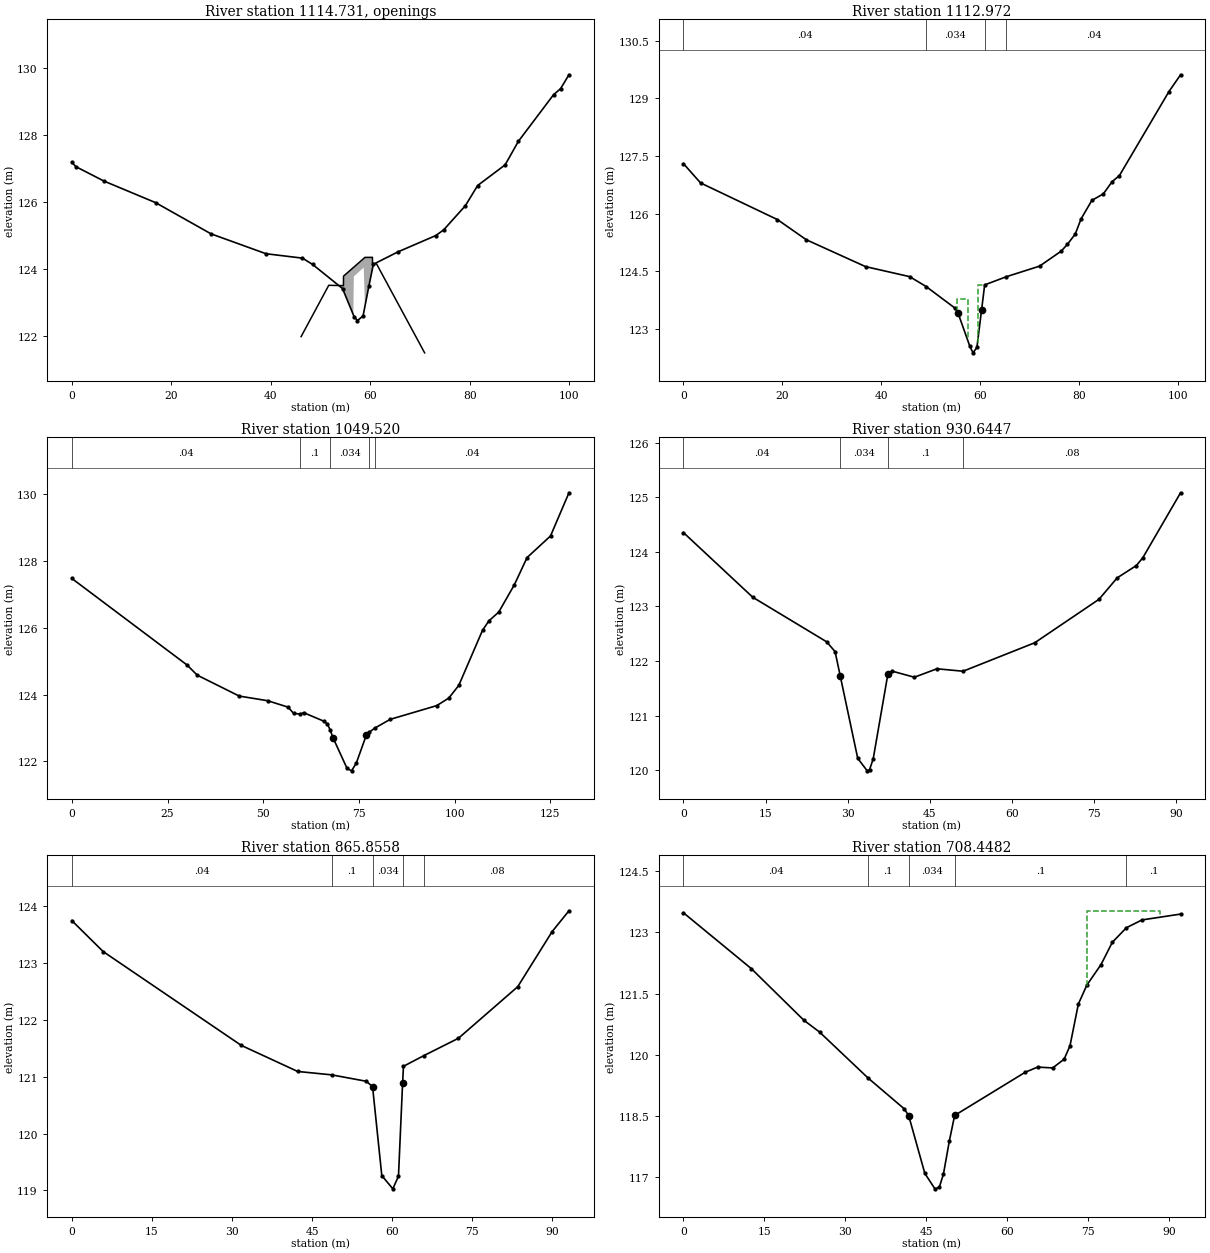
Type RM Length L Ch R = 4 ,1114.731,,,
BEGIN DESCRIPTION:
E179
END DESCRIPTION:
Bridge Culvert--1,0,-1,-1, 0
Deck Dist Width WeirC Skew NumUp NumDn MinLoCord MaxHiCord MaxSubmerge Is_Ogee
0.01,3.23,1.44,0, 15, 15, , , 0.95, 0, ,,,
  46.102  46.322  51.664  54.621  54.629   56.61  56.704  58.691  58.942   59.02
  60.451  60.468  61.269  70.768  70.941
 121.966 122.027 123.502 123.492 123.775 124.033 124.045 124.304 124.337 124.337
 124.338 124.155 124.144  121.53 121.482
 121.966  83.911  83.925  83.933  83.933  83.938 123.766 124.032  93.644  84.258
  84.242  84.242  84.233  84.128 121.482
  46.899  47.119  52.461  55.418  55.426  57.407  57.501  59.488  59.739  59.817
  61.248  61.265  62.066  71.565  71.738
 121.966 122.027 123.502 123.492 123.775 124.033 124.045 124.304 124.337 124.337
 124.338 124.155 124.144  121.53 121.482
 121.966  83.911  83.925  83.933  83.933  83.938 123.766 124.032  93.644  84.258
  84.242  84.242  84.233  84.128 121.482
BR Coef=-1 , 0 , 0 ,, 0 ,,,0.8,0,,0,
WSPro=,,,, 1 ,,,, 0 ,,,, 0 ,,,,-1 ,-1 ,-1 , 0 , 0 , 0 , 0 , 0
BC Mult= 1 ,0,54,0,55
BC Mult= 3 ,54,60,55,61
BC Mult= 1 ,60,110,61,130
BC Design=,, 0 ,, 0 ,,,,,,
BC Use User HTab Curves=0
BC User HTab FreeFlow(D)= 0

Type RM Length L Ch R = 1 ,1112.972,65.383,63.452,61.504
XS GIS Cut Line= 2
529911.2164564334781192.03892728529825.1843201514781139.96512382
#Sta/Elev= 26
       0 127.304   3.467 126.801  19.026 125.847   24.86 125.323  36.833 124.625
   45.76 124.364  49.096 124.107  54.972 123.541  55.517  123.43  57.945 122.549
  58.587 122.382  59.368 122.523  60.324 123.509  60.937 124.149  65.347 124.363
  72.042 124.637   76.43 125.028  77.669 125.204  79.256 125.469  80.442 125.867
  82.618 126.347  84.939 126.516  86.737 126.837  88.189 126.991  98.188 129.172
 100.564 129.614
#Mann= 4 ,-1 , 0
       0     .04       0  49.096    .034       0  60.937      .1       0
  65.347     .04       0
#XS Ineff= 2 ,-1
   55.43    57.5  123.77   59.49   60.94  124.15
Permanent Ineff=
       T       T
Bank Sta=55.517,60.324
XS Rating Curve= 0 ,0
Exp/Cntr=0.5,0.3

Type RM Length L Ch R = 1 ,1049.520,116.136,118.876,121.616
XS GIS Cut Line= 4
529954.5310568674781117.42948457529903.9083033074781109.11664909
529850.3150741324781118.26299602529827.4041741344781110.50428473
#Sta/Elev= 30
       0  127.48  30.113 124.887  32.769 124.584   43.74 123.958  51.179 123.819
  56.512 123.626   57.94 123.437  59.683 123.422   60.57 123.461  65.938 123.201
   66.77  123.12  67.472 122.945   68.22 122.712  71.896 121.792  73.066  121.72
  74.315 121.954  76.893  122.78  77.738 122.881  79.109 122.998  83.171 123.262
  95.307 123.672  98.462 123.898 101.071 124.277 107.299 125.933 108.954 126.211
 111.522 126.474 115.607 127.294 118.912 128.105 125.039 128.752 129.858 130.045
#Mann= 5 ,-1 , 0
       0     .04       0  59.683      .1       0  67.472    .034       0
  77.738      .1       0  79.109     .04       0
Bank Sta=68.22,76.893
XS Rating Curve= 0 ,0
Exp/Cntr=0.3,0.1

Type RM Length L Ch R = 1 ,930.6447,67.389,64.789,62.189
XS GIS Cut Line= 3
529950.0790944674781059.55459951529914.9584944674781021.96069951
529878.3538944674781007.61559951
#Sta/Elev= 20
       0 124.353  12.657 123.169  26.141 122.354  27.688 122.174   28.62 121.733
  31.822 120.221  33.553 119.992  33.976 120.011  34.647 120.211  37.319 121.758
  38.048 121.818  42.161 121.705   46.28  121.86  51.053 121.815  64.139 122.336
  75.865 123.131  79.194 123.524  82.704  123.75   83.87 123.892  90.762 125.081
#Mann= 4 ,-1 , 0
       0     .04       0   28.62    .034       0  37.319      .1       0
  51.053     .08       0
Bank Sta=28.62,37.319
XS Rating Curve= 0 ,0
Exp/Cntr=0.3,0.1

Type RM Length L Ch R = 1 ,865.8558,156.227,157.408,158.588
XS GIS Cut Line= 3
529980.2531944674780964.58039951529936.2286944674780972.49489951
529888.2469944674780978.92549951
#Sta/Elev= 17
       0 123.748   5.885 123.202  31.742 121.552  42.309 121.093  48.694 121.033
  55.176  120.92  56.343 120.825  58.073 119.261  60.141 119.027    61.2 119.251
   61.97  120.89  62.136 121.184  65.981 121.373  72.433 121.677  83.535 122.584
   89.99 123.555  93.141 123.921
#Mann= 5 ,-1 , 0
       0     .04       0  48.694      .1       0  56.343    .034       0
   61.97      .1       0  65.981     .08       0
Bank Sta=56.343,61.97
XS Rating Curve= 0 ,0
Exp/Cntr=0.3,0.1

Type RM Length L Ch R = 1 ,708.4482,26.724,26.721,26.718
XS GIS Cut Line= 2
529996.491631046 4780876.9487432529909.3596021984780846.97456568
#Sta/Elev= 25
       0 123.481  12.557 122.115  22.338 120.845  25.234 120.557  34.185 119.435
   40.91 118.677   41.75  118.51  44.739 117.094  46.615 116.714  47.417  116.75
  48.192 117.074  49.295 117.892  50.268 118.513  63.382 119.574  65.659 119.698
  68.444 119.678  70.559 119.891  71.651 120.221  73.198 121.243  74.779 121.709
  77.398 122.211  79.494 122.757    82.1 123.114  85.001 123.306  92.144 123.449
#Mann= 5 ,-1 , 0
       0     .04       0  34.185      .1       0   41.75    .034       0
  50.268      .1       0    82.1      .1       0
#XS Ineff= 1 ,-1
   74.71   88.37  123.53
Permanent Ineff=
       T
Bank Sta=41.75,50.268
XS Rating Curve= 0 ,0
Exp/Cntr=0.3,0.1

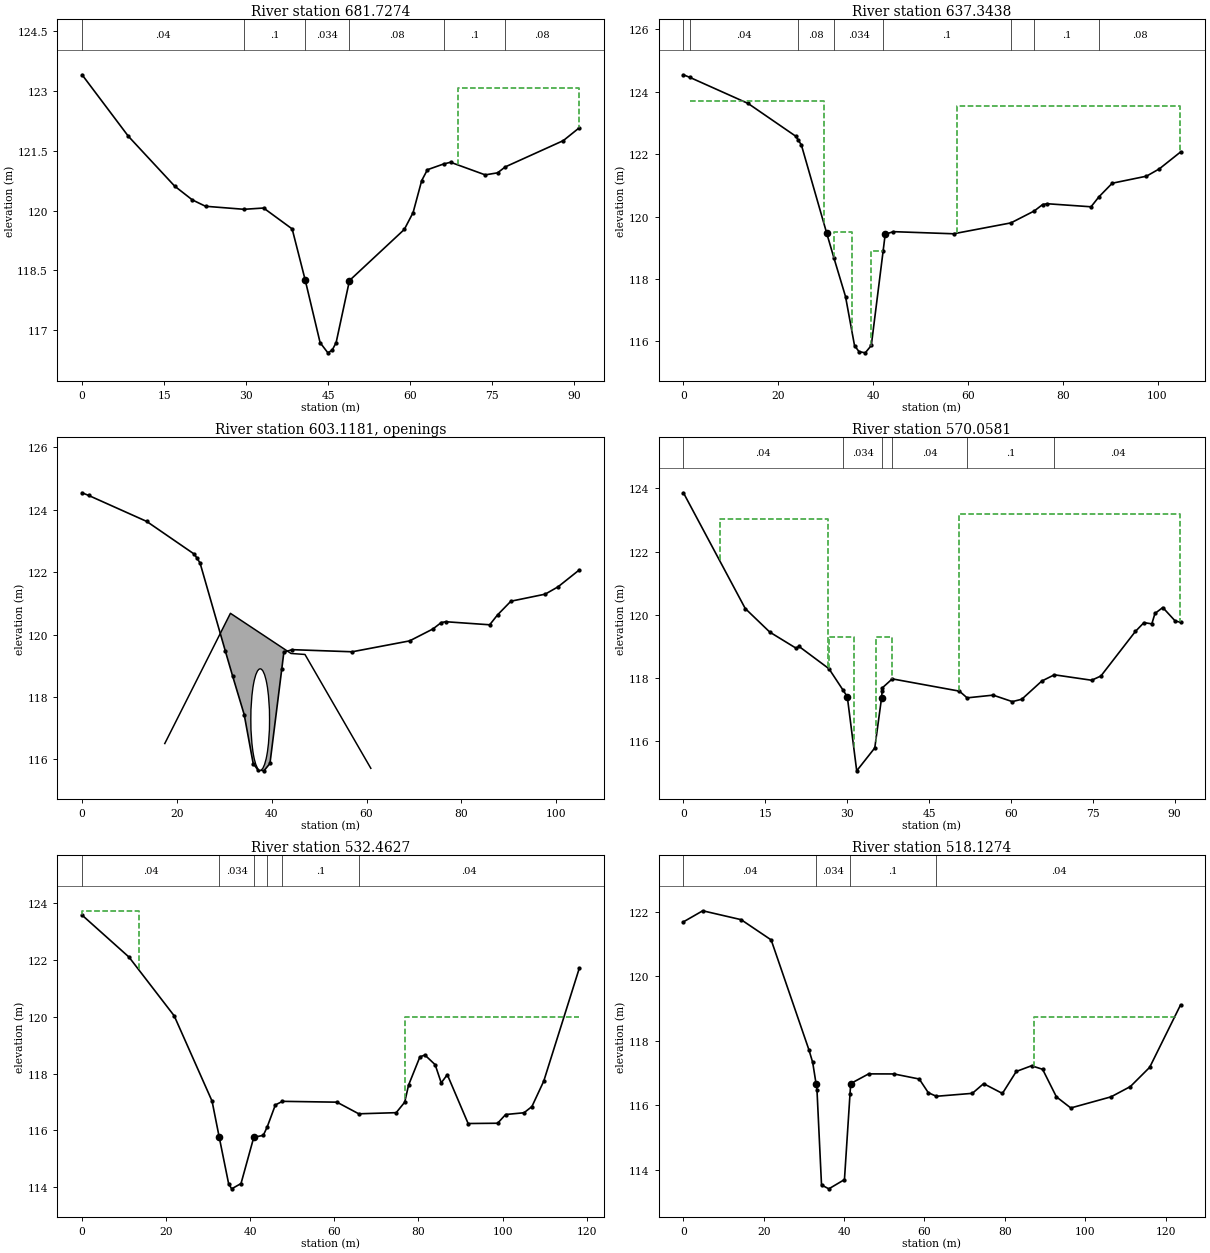
Type RM Length L Ch R = 1 ,681.7274,45.505,44.384,43.262
XS GIS Cut Line= 3
530004.0090309154780840.90743053529976.2667834664780841.80215985
 529916.506460014780821.30322054
#Sta/Elev= 25
       0 123.405   8.463 121.864  16.935 120.614  20.164 120.269  22.576 120.109
  29.627 120.033  33.203 120.065  38.427 119.541   40.83  118.25  43.539  116.69
  44.963 116.435  45.756 116.505  46.469 116.691  48.908 118.247  58.939 119.528
  60.548 119.951  62.123 120.753  63.168 121.025   66.11 121.168  67.397 121.212
   73.74 120.896  75.994 120.947  77.422 121.097  88.018 121.754  90.935 122.075
#Mann= 6 ,-1 , 0
       0     .04       0  29.627      .1       0   40.83    .034       0
  48.908     .08       0   66.11      .1       0  77.422     .08       0
#XS Ineff= 1 ,-1
   68.81   91.72  123.07
Permanent Ineff=
       T
Bank Sta=40.83,48.908
XS Rating Curve= 0 ,0
Exp/Cntr=0.5,0.3

Type RM Length L Ch R = 1 ,637.3438,67.287,67.286,67.285
XS GIS Cut Line= 4
530008.8942327414780791.43235636529959.6247228344780795.06919587
529945.9573337984780816.91433106 529916.442457764780820.14054868
#Sta/Elev= 27
       0 124.542   1.363 124.458   13.63 123.624  23.676 122.575  24.223 122.451
   24.88 122.293   30.24 119.457  31.731  118.68  34.189 117.437  36.088 115.867
  37.026 115.672  38.356 115.632   39.63 115.869   42.13 118.903   42.56 119.431
  44.295 119.515  56.968 119.447  69.083 119.796  74.001 120.178  75.776 120.385
  76.716  120.41  85.978 120.312  87.634 120.629  90.448 121.067  97.675 121.293
 100.391 121.528 104.863 122.068
#Mann= 8 ,-1 , 0
       0      .1       0   1.363     .04       0  24.223     .08       0
  31.731    .034       0   42.13      .1       0  69.083     .08       0
  74.001      .1       0  87.634     .08       0
#XS Ineff= 4 ,-1
    1.37    29.7 123.714   31.73   35.63   119.5   39.54   42.13   118.9
   57.65  104.78 123.532
Permanent Ineff=
       T       T       T       T
Bank Sta=30.24,42.56
XS Rating Curve= 0 ,0
Exp/Cntr=0.5,0.3

Type RM Length L Ch R = 4 ,603.1181,,,
BEGIN DESCRIPTION:
E181
END DESCRIPTION:
Bridge Culvert--1,0,-1,-1, 0
Deck Dist Width WeirC Skew NumUp NumDn MinLoCord MaxHiCord MaxSubmerge Is_Ogee
0.01,67.09,1.44,0, 22, 22, , , 0.95, 0, ,,,
  17.442  17.948  31.291  35.548  35.732   35.74  35.957  36.192  36.503    37.1
  37.573  38.172  38.648  39.197  39.488   39.67  39.718  39.892  44.065  47.015
  60.725  60.904
 116.507 116.659  120.68 120.251 120.232 120.232  120.21 120.186 120.155 120.094
 120.047 119.987 119.939 119.883 119.854 119.836 119.831 119.813 119.393 119.361
  115.76 115.713
  13.103  13.609  26.952  31.209  31.393  31.401  31.618  31.853  32.164  32.761
  33.234  33.833  34.309  34.858  35.149  35.331  35.379  35.553  39.726  42.676
  56.386  56.565
 116.507 116.659  120.68 120.251 120.232 120.232  120.21 120.186 120.155 120.094
 120.047 119.987 119.939 119.883 119.854 119.836 119.831 119.813 119.393 119.361
  115.76 115.713
BR Coef=-1 , 0 , 0 ,, 0 ,,,0.8,-1,,0,
WSPro=,,,, 1 ,,,, 0 ,,,, 0 ,,,,-1 ,-1 ,-1 , 0 , 0 , 0 , 0 , 0
Culvert=9,3.25,3.95,67,0.02,0.5,1,60,1,115.65,37.57,115.06,33.23,Culvert #1  , 0 ,0.1
Culvert Bottom n=0.02
Culvert Bottom Depth=0.036
BC Mult= 1 ,0,29,0,22
BC Mult= 2 ,29,43,22,47
BC Mult= 1 ,43,120,47,100
BC Design=,, 0 ,, 0 ,,,,,,
BC Use User HTab Curves=0
BC User HTab FreeFlow(D)= 0

Type RM Length L Ch R = 1 ,570.0581,38.124,37.595,37.066
XS GIS Cut Line= 2
529999.3545393734780724.65951932529908.5217337944780731.41956518
#Sta/Elev= 30
       0 123.857  11.329 120.196  15.832  119.45  20.641 118.942  21.172 118.999
  26.654 118.295  29.282 117.607  30.024 117.407  31.748 115.064   35.06 115.789
   36.31  117.38  36.404 117.588  36.458  117.69  38.261 117.972  50.566 117.584
  51.973 117.372  56.741 117.458  60.259 117.253  61.994 117.328  65.656 117.903
  67.958 118.101   74.79 117.929   76.49 118.063  82.812 119.473  84.379 119.751
  85.821 119.712  86.392  120.04  87.826 120.229  90.126 119.798  91.084 119.765
#Mann= 6 ,-1 , 0
       0     .04       0  29.282    .034       0  36.404     .01       0
  38.261     .04       0  51.973      .1       0  67.958     .04       0
#XS Ineff= 4 ,-1
    6.61   26.52  123.03   26.65   31.27   119.3    35.2    38.3   119.3
   50.48   91.01123.1828
Permanent Ineff=
       T       T       T       T
Bank Sta=30.024,36.31
XS Rating Curve= 0 ,0
Exp/Cntr=0.5,0.3

Type RM Length L Ch R = 1 ,532.4627,16.002,14.335,12.669
XS GIS Cut Line= 4
  529994.1035945 4780681.2655995  529947.1111945 4780694.1265995
  529900.1187945 4780725.2899995         529895.        4780738.
#Sta/Elev= 30
       0 123.577  11.159 122.099  21.906 120.031  30.909 117.028   32.61  115.76
  34.847 114.122  35.565 113.939  37.794 114.125  40.834 115.755  43.094 115.823
  44.016 116.115  45.963 116.894  47.656  117.02  60.605 116.991  65.797 116.581
  74.701 116.621  76.727 116.991  77.645 117.593  80.342 118.587  81.526 118.651
  83.968  118.31  85.411  117.67  86.853  117.96  91.806 116.239  98.821 116.249
 100.725 116.556 105.107 116.618106.9752116.8366109.7874117.7305118.2251 121.698
#Mann= 6 ,-1 , 0
       0     .04       0   32.61    .034       0  40.834      .1       0
  44.016     .04       0  47.656      .1       0  65.797     .04       0
#XS Ineff= 2 , 0
           13.64  123.73    76.9          119.98
Permanent Ineff=
       T       T
Bank Sta=32.61,40.834
XS Rating Curve= 0 ,0
Exp/Cntr=0.5,0.3

Type RM Length L Ch R = 1 ,518.1274,23.183,23.099,23.085
XS GIS Cut Line= 4
529976.0445735944780649.15342937529947.1793306744780683.63394488
529900.4897652774780722.13660456529886.4100887924780733.74744282
#Sta/Elev= 30
       0 121.683   4.806 122.026  14.351 121.751  21.837 121.123  31.228 117.721
  32.175 117.326   33.01  116.67   33.24 116.477   34.37  113.53   36.19  113.41
  40.079 113.696  41.469 116.363  41.641 116.673    46.1 116.972  52.394  116.97
  58.694 116.813  60.948 116.389  62.954 116.278  71.906 116.369  74.715 116.669
  79.397 116.366  82.847 117.047  86.646 117.224  89.399 117.114  92.832 116.261
   96.41 115.916106.4409116.2613 111.245116.5793 116.049117.1755123.7356119.1097
#Mann= 4 ,-1 , 0
       0     .04       0   33.01    .034       0  41.469      .1       0
  62.954     .04       0
#XS Ineff= 2 ,-1
    57.6   83.63  116.83   87.33  122.61  118.75
Permanent Ineff=
       T       T
Bank Sta=33.01,41.641
XS Rating Curve= 0 ,0
Exp/Cntr=0.5,0.3