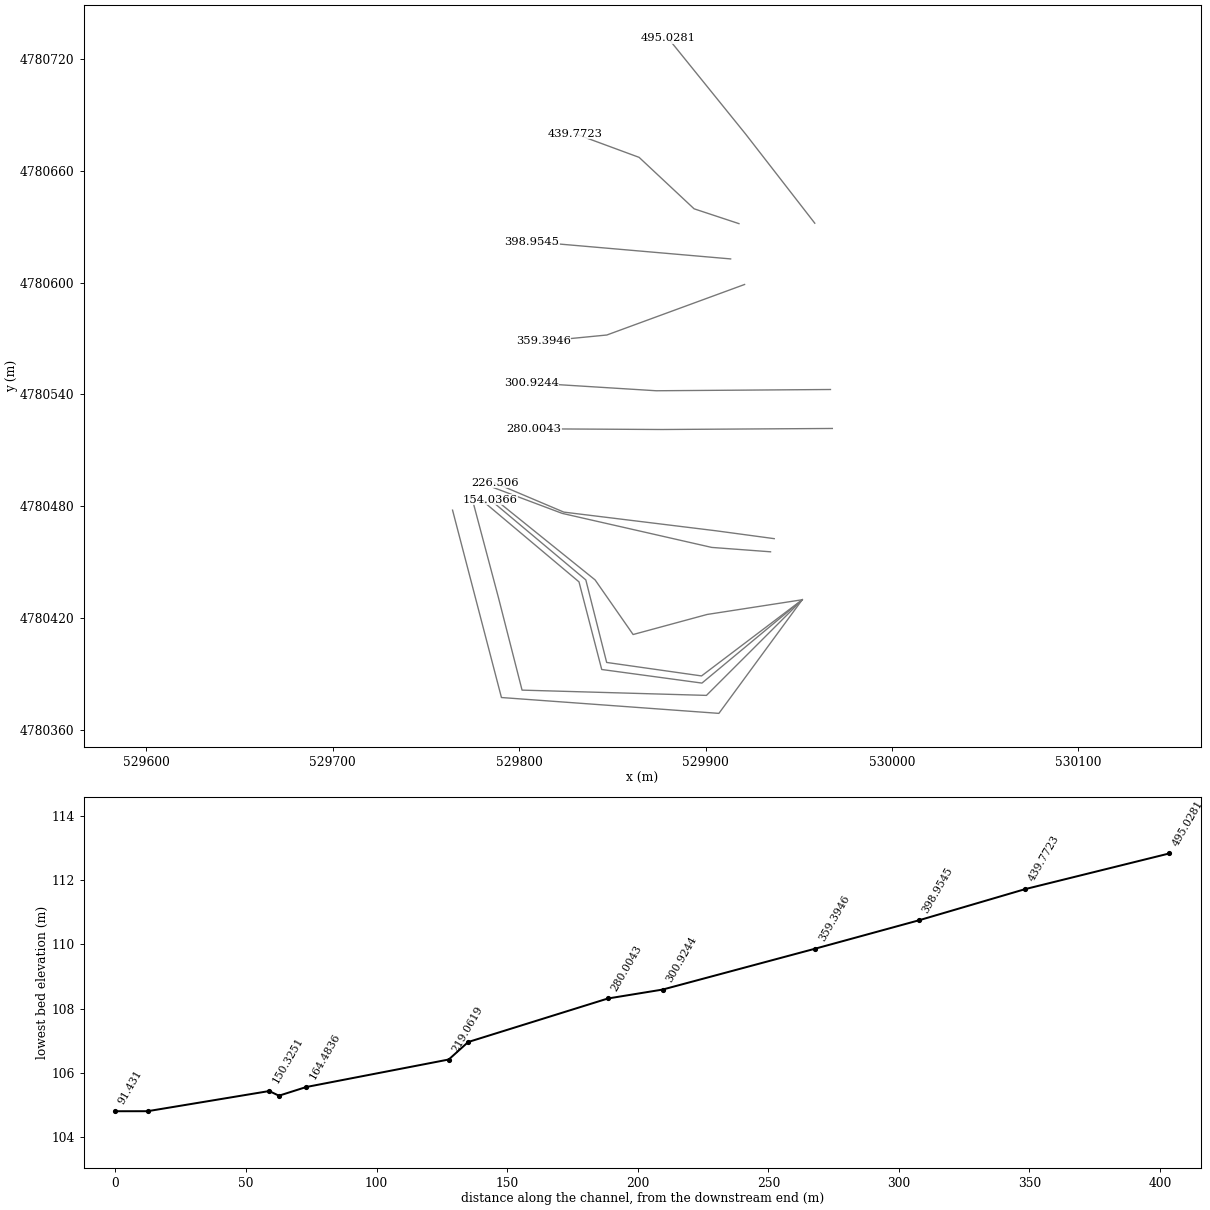
HEC-RAS study Durango.prj: Durango

--- Durango.g18 (geometry) --- (continued)

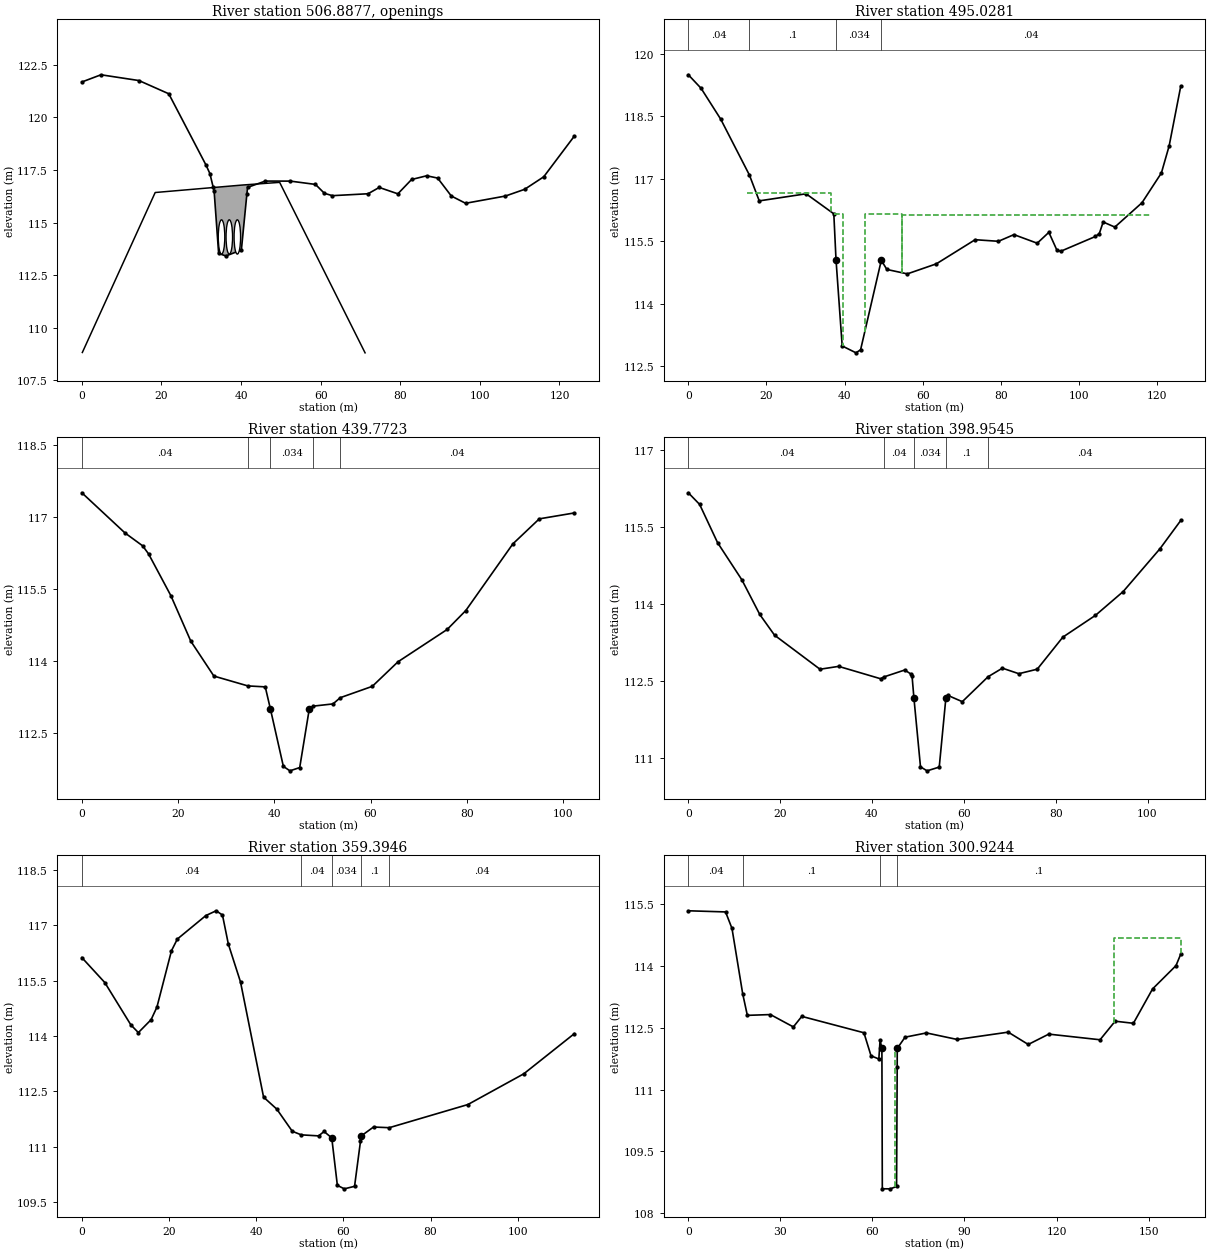
Type RM Length L Ch R = 4 ,506.8877,,,
BEGIN DESCRIPTION:
E182
END DESCRIPTION:
Bridge Culvert--1,0,-1,-1, 0
Deck Dist Width WeirC Skew NumUp NumDn MinLoCord MaxHiCord MaxSubmerge Is_Ogee
0.01,22.9,1.44,0, 7, 7, , , 0.95, 0, ,,,
    .123    .788  18.424   40.29  49.696  70.789  71.161
 108.822 109.098 116.428 116.783 116.911 108.945 108.805
 108.822   15.87  15.778  15.665  15.616  15.506 108.805
   3.389   4.054   21.69  43.556  52.962  74.055  74.427
 108.822 109.098 116.428 116.783 116.911 108.945 108.805
 108.822   15.87  15.778  15.665  15.616  15.506 108.805
BR Coef=-1 , 0 , 0 ,, 0 ,,,0.8,0,,0,
WSPro=,,,, 1 ,,,, 0 ,,,, 0 ,,,,-1 ,-1 ,-1 , 0 , 0 , 0 , 0 , 0
Multiple Barrel Culv=1,1.63,,20,0.02,0.5,1,1,1,113.5,113.45, 3,Culvert #1  , 0 ,0.01
  35.095  40.359  37.046   42.31  39.064  44.328
Culvert Bottom n=0.02
BC Mult= 1 ,0,33,0,36
BC Mult= 2 ,33,43,36,57
BC Mult= 1 ,43,150,57,150
BC Design=,, 0 ,, 0 ,,,,,,
BC Use User HTab Curves=0
BC User HTab FreeFlow(D)= 0

Type RM Length L Ch R = 1 ,495.0281,54.828,55.256,55.615
XS GIS Cut Line= 4
  529958.6022599 4780631.8485059  529921.4573275 4780679.7115339
  529921.4570507 4780679.7120941         529880.        4780731.
#Sta/Elev= 30
       0 119.491   3.256 119.168   8.284 118.428  15.625  117.09  18.155 116.468
  30.142 116.638  37.239 116.158    37.8  115.06  39.382 112.991  42.911 112.825
  44.093 112.899  49.392 115.043  50.815 114.824  56.056 114.71863.47947114.9584
73.41068115.537179.36955115.499183.34199 115.65989.30073115.452992.28019115.7138
94.26649115.301395.25946115.2577104.1977115.6145 105.191115.6852 106.184115.9617
109.1633115.8396116.1153116.4232 121.081117.1365123.0673117.7869126.0466119.2223
#Mann= 4 ,-1 , 0
       0     .04       0  15.625      .1       0    37.8    .034       0
  49.392     .04       0
#XS Ineff= 4 ,-1
   15.01   36.48  116.65   37.24   39.54  116.16   45.14    54.6  116.16
   54.64  118.54  116.14
Permanent Ineff=
       T       T       T       T
Bank Sta=37.8,49.392
XS Rating Curve= 0 ,0
Exp/Cntr=0.5,0.3

Type RM Length L Ch R = 1 ,439.7723,39.003,40.818,42.633
XS GIS Cut Line= 4
529917.9263944674780631.61439951529893.8780602844780639.56543033
529864.383240437 4780667.1608517529830.0010944674780679.84339951
#Sta/Elev= 24
       0 117.506   8.959  116.67  12.623 116.402  13.856 116.235  18.503 115.363
  22.647 114.415  27.444 113.688  34.508 113.483  38.122 113.463   39.21 112.996
  41.887 111.807  43.249 111.714  45.284 111.782  47.278 113.005  48.098 113.062
  52.199 113.108  53.722 113.238  60.373 113.474  65.721 113.986  75.936 114.659
  79.808 115.053  89.586 116.441  95.083 116.963 102.367 117.086
#Mann= 5 ,-1 , 0
       0     .04       0  34.508     .04       0   39.21    .034       0
  48.098      .1       0  53.722     .04       0
Bank Sta=39.21,47.278
XS Rating Curve= 0 ,0
Exp/Cntr=0.3,0.1

Type RM Length L Ch R = 1 ,398.9545,38.367,39.56,40.753
XS GIS Cut Line= 2
529913.4745149724780612.69371427529806.6285746214780621.96853548
#Sta/Elev= 29
       0  116.16   2.465 115.933   6.369 115.188  11.666 114.463  15.563 113.788
  18.774 113.385  28.678 112.721   32.74 112.777  41.861 112.536  42.717 112.575
  47.129 112.706    48.6  112.62  48.727 112.588   49.12  112.17  50.561 110.819
  51.992 110.741  54.643 110.814   56.09  112.16  56.448 112.214  59.666 112.089
  65.282 112.575  68.398 112.742  71.974 112.634  75.989 112.722  81.566 113.347
  88.663 113.771  94.713 114.236 102.701 115.068 107.248 115.621
#Mann= 5 ,-1 , 0
       0     .04       0  42.717     .04       0   49.12    .034       0
   56.09      .1       0  65.282     .04       0
Bank Sta=49.12,56.09
XS Rating Curve= 0 ,0
Exp/Cntr=0.3,0.1

Type RM Length L Ch R = 1 ,359.3946,59.425,58.47,57.515
XS GIS Cut Line= 3
529920.9429463494780598.98369179529847.0667944674780571.88449951
529812.9354944674780568.54559951
#Sta/Elev= 30
       0 116.129    5.26 115.453  11.248 114.304  12.965 114.096  15.887 114.446
  17.226 114.787  20.561 116.314  21.911 116.631  28.456 117.268  30.813 117.397
  32.262 117.281  33.612 116.493  36.399 115.468  41.692 112.347  44.727 112.022
  48.277 111.422  50.335 111.325  54.314 111.297  55.571 111.416  57.334 111.242
  58.619 109.957  60.208 109.862  62.565  109.93  63.927 111.153  63.992 111.287
  66.914 111.537  70.525 111.519  88.561 112.146   101.4  112.98 112.985 114.067
#Mann= 5 ,-1 , 0
       0     .04       0  50.335     .04       0  57.334    .034       0
  63.992      .1       0  70.525     .04       0
Bank Sta=57.334,63.992
XS Rating Curve= 0 ,0
Exp/Cntr=0.5,0.3

Type RM Length L Ch R = 1 ,300.9244,20.923,20.92,20.917
XS GIS Cut Line= 3
529967.0048106944780542.65778008529873.5565660574780541.98559198
529806.6285746214780546.15624116
#Sta/Elev= 30
       0 115.343   12.14 115.315  14.234 114.914   17.72 113.328  19.235 112.803
  26.765 112.822  34.235 112.522  36.986 112.778  57.235  112.38  59.552  111.82
  62.096 111.743    62.5   112.2   63.09     112  63.227  108.59  65.838 108.589
  67.875 108.647  68.077 111.553  68.093     112  70.644 112.273  77.612 112.376
  87.639 112.217 104.257 112.395 110.796 112.096 117.478 112.347 134.194  112.21
 139.115 112.661 145.059  112.61  151.31 113.445 158.945 114.011 160.508 114.293
#Mann= 4 ,-1 , 0
       0     .04       0   17.72      .1       0    62.5    .034       0
  67.875      .1       0
#XS Ineff= 2 ,-1
   67.23   68.09     112  138.61  161.76  114.68
Permanent Ineff=
       T       T
Bank Sta=63.09,68.093
XS Rating Curve= 0 ,0
Exp/Cntr=0.5,0.3

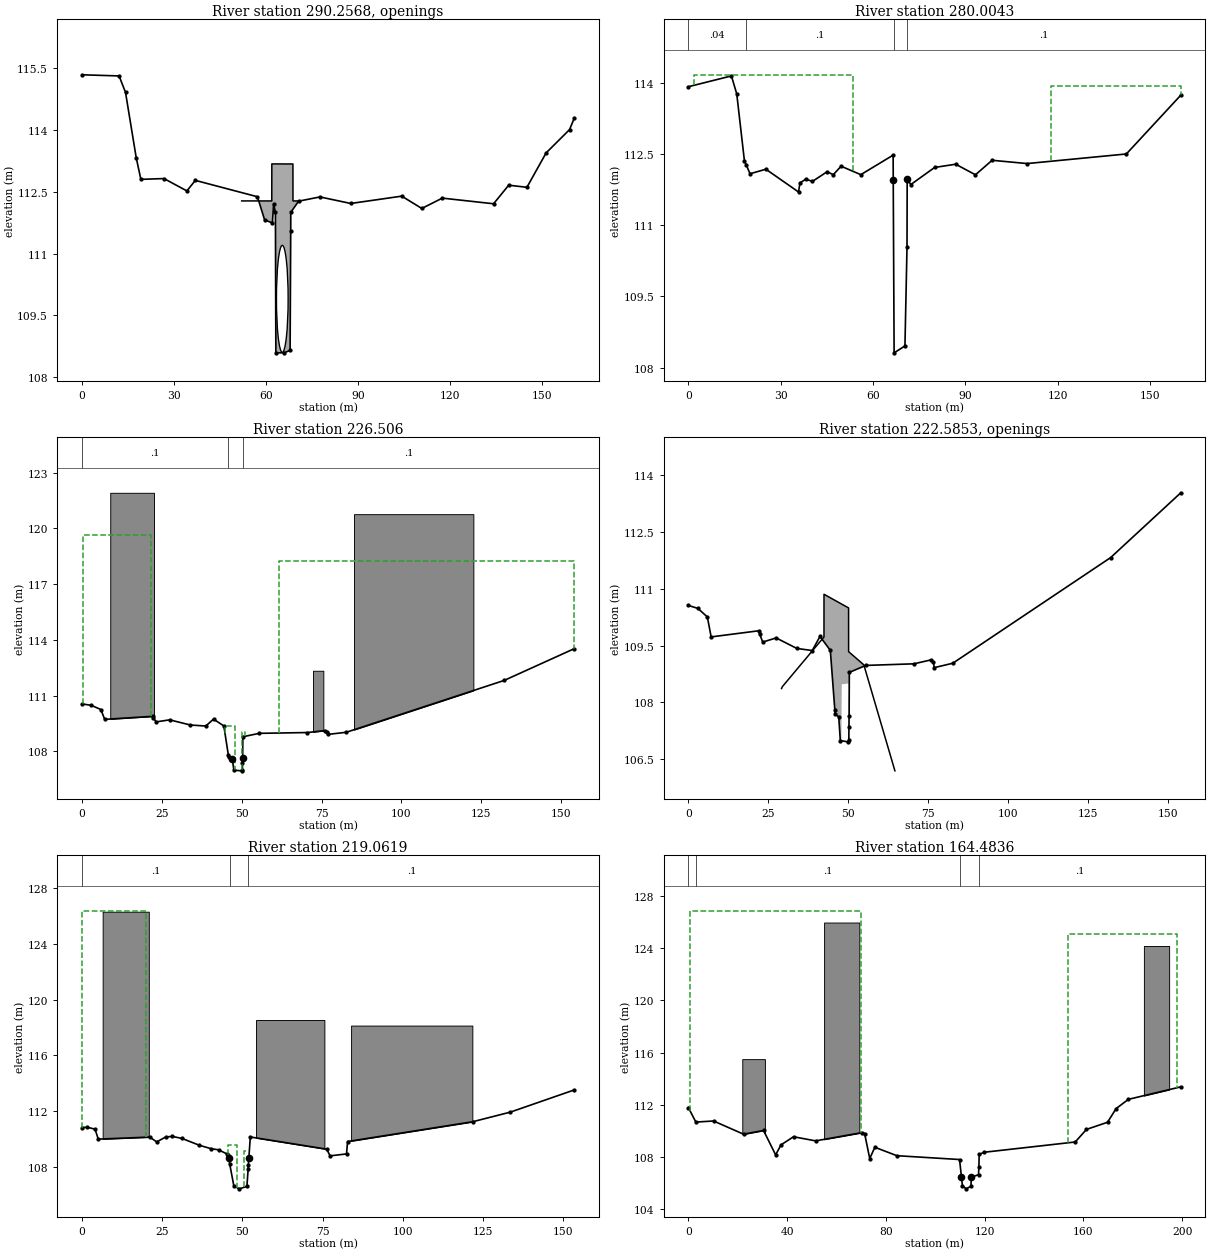
Type RM Length L Ch R = 4 ,290.2568,,,
BEGIN DESCRIPTION:
E183
END DESCRIPTION:
Bridge Culvert--1,0,-1,-1, 0
Deck Dist Width WeirC Skew NumUp NumDn MinLoCord MaxHiCord MaxSubmerge Is_Ogee
0.01,20.72,1.44,0, 22, 26, , , 0.95, 0, ,,,
  52.098  58.646  61.896  61.914  63.366  63.447  63.567   63.82  64.382  64.762
   65.14   65.54  65.978  66.383  66.686  66.977  67.224  67.244  67.621  68.796
  68.811  71.245
 112.279 112.279 112.279 113.178 113.178 113.178 113.178 113.178 113.178 113.178
 113.178 113.177 113.177 113.177 113.177 113.177 113.177 113.177 113.177 113.177
 112.279 112.279
  55.368  55.534  62.082  65.332   65.35  66.802  66.883  67.003  67.256  67.818
  68.198  68.576  68.976  69.414  69.819  70.122  70.413   70.66   70.68  71.057
  72.232  72.247   74.73  76.138  85.466  85.574
 109.984 110.041 112.279 112.279 113.178 113.178 113.178 113.178 113.178 113.178
 113.178 113.178 113.177 113.177 113.177 113.177 113.177 113.177 113.177 113.177
 113.177 112.279 112.279 112.279 109.466 109.433
BR Coef=-1 , 0 , 0 ,, 0 ,,,0.8,-1,,0,
WSPro=,,,, 1 ,,,, 0 ,,,, 0 ,,,,-1 ,-1 ,-1 , 0 , 0 , 0 , 0 , 0
Culvert=9,2.6,3.8,20,0.02,0.5,1,61,2,108.6,65.33,108.35,68.78,Culvert #1  , 0 ,0.1
Culvert Bottom n=0.02
Culvert Bottom Depth=0.036
BC Mult= 1 ,0,57,0,65
BC Mult= 2 ,57,70,65,76
BC Mult= 1 ,70,170,76,170
BC Design=,, 0 ,, 0 ,,,,,,
BC Use User HTab Curves=0
BC User HTab FreeFlow(D)= 0

Type RM Length L Ch R = 1 ,280.0043,53.845,53.498,53.152
XS GIS Cut Line= 3
529968.0089218354780521.75652513529876.7303302424780521.20158041
 529808.096653284780521.57257325
#Sta/Elev= 30
       0  113.92  13.996 114.148  15.728 113.768  18.224 112.355  18.806 112.274
  20.037 112.086  25.182 112.182   35.79 111.702  36.239  111.89  38.123 111.973
  40.304 111.925   45.08 112.129  47.068 112.066  49.611 112.245  56.014 112.067
  66.511 112.479   66.54  111.96  66.826 108.312  70.342 108.457  71.011 110.535
  71.069  111.94  71.077 111.982  72.239 111.858  79.981 112.219  86.828 112.287
   93.24 112.064   98.64  112.37 110.024 112.301  142.24 112.503 159.915 113.742
#Mann= 4 ,-1 , 0
       0     .04       0  18.806      .1       0  66.826    .034       0
  71.011      .1       0
#XS Ineff= 2 ,-1
     1.9   53.44 114.172  117.71  160.14  113.93
Permanent Ineff=
       T       T
Bank Sta=66.54,71.077
XS Rating Curve= 0 ,0
Exp/Cntr=0.5,0.3

Type RM Length L Ch R = 1 ,226.506 ,7.723,7.444,7.165
XS GIS Cut Line= 4
529936.8513223884780462.65998681529905.7830843034780466.86164798
529823.9864906984780476.90009993529786.8534285214780492.63304483
#Sta/Elev= 29
       0 110.558    2.98 110.479    5.95 110.254   7.145 109.727  22.243 109.891
  22.276 109.811   23.29 109.591  27.477   109.7  33.952 109.423  38.776 109.367
    41.2  109.74   44.43 109.371  45.846 107.797  45.898 107.693  47.063 107.619
   47.56 106.992  49.993 106.958  50.222 106.995  50.262 107.354   50.31  107.63
  50.381 108.791  55.543 108.975  70.587 109.017  76.033 109.123  76.701 109.067
   76.93 108.916  82.746 109.032 132.145  111.82  154.09 113.529
#Mann= 3 ,-1 , 0
       0      .1       0  45.846    .034       0  50.381      .1       0
#XS Ineff= 4 ,-1
     .28   21.71  119.65   44.76   48.01  109.37   50.17   51.14  109.04
    61.6  153.94  118.22
Permanent Ineff=
       T       T       T       T
#Block Obstruct= 3 ,-1
    8.88   22.56  121.91   72.32   75.56  112.34   85.15   122.5  120.76
Bank Sta=47.063,50.31
XS Rating Curve= 0 ,0
Exp/Cntr=0.5,0.3

Type RM Length L Ch R = 4 ,222.5853,,,
BEGIN DESCRIPTION:
E184
END DESCRIPTION:
Bridge Culvert--1,0,-1,-1, 0
Deck Dist Width WeirC Skew NumUp NumDn MinLoCord MaxHiCord MaxSubmerge Is_Ogee
0.01,7.24,1.44,0, 13, 13, , , 0.95, 0, ,,,
  29.173  29.424  42.445  42.451  47.874  48.015  50.148  50.157  50.169  50.238
  54.919  64.593  64.639
 108.365 108.415 109.725 110.852 110.598 110.591 110.492 109.338 109.337 109.332
  108.99 106.208 106.194
 108.365  46.318  46.086  46.085  45.989 108.476 108.499 108.499 108.499  45.888
   45.85  45.773 106.194
  29.503  29.754  42.775  42.781  48.204  48.345  50.478  50.487  50.499  50.568
  55.249  64.923  64.969
 108.365 108.415 109.725 110.852 110.598 110.591 110.492 109.338 109.337 109.332
  108.99 106.208 106.194
 108.365  46.318  46.086  46.085  45.989 108.476 108.499 108.499 108.499  45.888
   45.85  45.773 106.194
BR Coef=-1 , 0 , 0 ,, 0 ,,,0.8,-1,,0,
WSPro=,,,, 1 ,,,, 0 ,,,, 0 ,,,,-1 ,-1 ,-1 , 0 , 0 , 0 , 0 , 0
BC Mult= 1 ,0,42,0,42
BC Mult= 3 ,42,52,42,53
BC Mult= 1 ,52,160,53,160
BC Design=,, 0 ,, 0 ,,,,,,
BC Use User HTab Curves=0
BC User HTab FreeFlow(D)= 0

Type RM Length L Ch R = 1 ,219.0619,56.592,54.578,52.565
XS GIS Cut Line= 4
529934.8701192734780455.60854911529903.3373336844780457.95917414
529823.1282526954780476.21314073529786.1019870474780490.11088402
#Sta/Elev= 30
       0 110.812   1.708 110.832    4.11 110.696   5.113 109.981  21.158 110.129
  23.314 109.781  26.077 110.129  28.119  110.18   31.25 110.027  36.545 109.545
  40.244 109.296  42.588 109.214  45.195  108.92  45.534 108.858  45.793 108.631
  46.066 108.196  47.351 106.624  49.042 106.414  51.423 106.589  51.824 107.873
  51.878  108.15   52.03  108.64  52.481 110.136  76.301  109.26  77.326 108.781
  82.454  108.92  82.789 109.809 121.739 111.228 133.488 111.918 153.429 113.513
#Mann= 3 ,-1 , 0
       0      .1       0  46.066    .034       0  51.878      .1       0
#XS Ineff= 3 ,-1
     .14   20.02126.3667   45.53   48.35  109.55    50.5    52.2  109.15
Permanent Ineff=
       T       T       T
#Block Obstruct= 3 ,-1
    6.48   20.86   126.3   54.27   75.56  118.53   83.88  121.66  118.13
Bank Sta=45.793,52.03
XS Rating Curve= 0 ,0
Exp/Cntr=0.5,0.3

Type RM Length L Ch R = 1 ,164.4836,11.431,10.447,9.463
XS GIS Cut Line= 5
529951.8689309634780429.89509595529900.8607581254780422.00339017
529861.1645233424780411.24459756529840.7599166774780440.55303259
529785.481982259 4780485.0721744
#Sta/Elev= 30
       0 111.792   3.051 110.676  10.218 110.758  22.361 109.747  30.456 110.033
  35.362 108.159  37.539  108.93  42.599  109.55  51.544 109.235  70.357 109.868
  71.393 109.793  73.466  107.88  75.538 108.744  84.464 108.098 109.833 107.805
  110.62  106.45  111.01 105.797 112.501 105.558 114.413 105.751 114.663 106.432
 117.532 106.653  117.66 107.231 117.795   108.2  119.89 108.364 156.688 109.149
 161.225 110.112 169.759  110.66 173.235 111.707   178.2 112.417 199.431 113.375
#Mann= 4 ,-1 , 0
       0     .04       0   3.051      .1       0 109.833    .034       0
  117.66      .1       0
#XS Ineff= 2 ,-1
      .7   70.13  126.87  153.83  197.71   125.1
Permanent Ineff=
       T       T
#Block Obstruct= 3 ,-1
   21.85   31.01   115.5   54.98   69.25  125.97  184.49  194.71  124.17
Bank Sta=110.62,114.663
XS Rating Curve= 0 ,0
Exp/Cntr=0.5,0.3

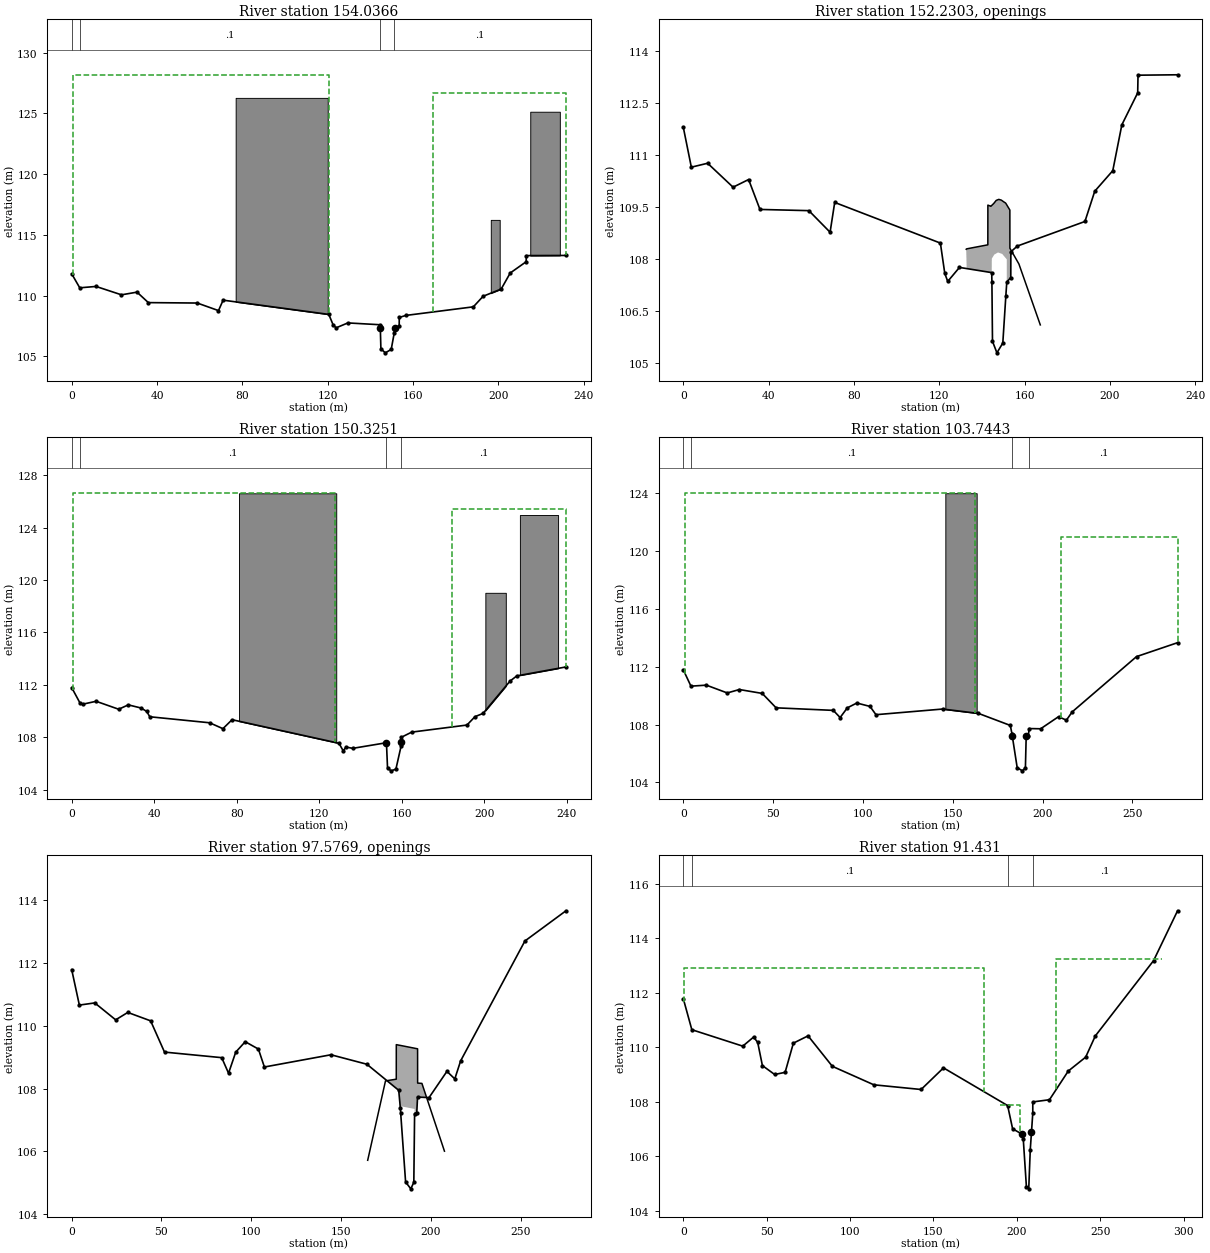
Type RM Length L Ch R = 1 ,154.0366,3.695,3.712,3.728
XS GIS Cut Line= 5
529951.8688944674780429.89509951529897.8653909364780389.03640177
529846.976218642 4780396.2669203529835.803125614  4780440.532689
529784.4979188814780483.54827538
#Sta/Elev= 30
       0 111.792   3.777 110.639  11.408 110.752   23.34 110.062  30.627 110.283
  35.945 109.421  58.876 109.386  68.824 108.764   70.99 109.623 120.537 108.451
 122.599 107.575 123.984 107.347 129.478  107.75 144.602   107.6  144.69  107.33
  144.96  105.62 147.041 105.288 149.798  105.57 151.206 106.916 151.665 107.328
  153.54 107.458 153.569   108.2  156.62 108.366 188.302 109.074 192.897 109.945
 201.355 110.538 205.598 111.858 213.033 112.781 213.192  113.29 231.726 113.302
#Mann= 4 ,-1 , 0
       0     .04       0   3.777      .1       0 144.602    .034       0
 151.206      .1       0
#XS Ineff= 2 ,-1
     .44  120.48  128.17  169.16   232.6  126.67
Permanent Ineff=
       T       T
#Block Obstruct= 3 ,-1
   76.87  120.04  126.27  196.48  200.66  116.23  214.98  228.85  125.13
Bank Sta=144.69,151.665
XS Rating Curve= 0 ,0
Exp/Cntr=0.5,0.3

Type RM Length L Ch R = 4 ,152.2303,,,
BEGIN DESCRIPTION:
E185
END DESCRIPTION:
Bridge Culvert--1,0,-1,-1, 0
Deck Dist Width WeirC Skew NumUp NumDn MinLoCord MaxHiCord MaxSubmerge Is_Ogee
0.01,3.51,1.44,0, 25, 25, , , 0.95, 0, ,,,
 132.642 132.854 142.775 142.797 144.195 144.391  144.64 145.522 145.783 146.715
 147.554 147.915 149.113 149.543 150.312 151.116 151.508 151.655 151.844 153.113
 153.126 153.423 157.354 167.255 167.373
 108.274 108.285 108.401 109.546 109.512 109.524 109.539 109.591 109.611 109.682
 109.702 109.711 109.689  109.67 109.637 109.605 109.567 109.552 109.532 109.403
 108.302 108.272 107.848 106.114 106.093
 108.274  53.446  53.227  53.227  53.196  53.192 108.002 108.092 108.119 108.152
 108.181 108.173 108.147 108.137  108.08 108.021 107.993 107.982  52.994  52.984
  52.984  52.982  52.951  52.873 106.093
 140.547 140.759  150.68 150.702   152.1 152.296 152.545 153.427 153.688  154.62
 155.459  155.82 157.018 157.448 158.217 159.021 159.413  159.56 159.749 161.018
 161.031 161.328 165.259  175.16 175.278
 108.274 108.285 108.401 109.546 109.512 109.524 109.539 109.591 109.611 109.682
 109.702 109.711 109.689  109.67 109.637 109.605 109.567 109.552 109.532 109.403
 108.302 108.272 107.848 106.114 106.093
 108.274  53.446  53.227  53.227  53.196  53.192 108.002 108.092 108.119 108.152
 108.181 108.173 108.147 108.137  108.08 108.021 107.993 107.982  52.994  52.984
  52.984  52.982  52.951  52.873 106.093
BR Coef=-1 , 0 , 0 ,, 0 ,,,0.8,0,,0,
WSPro=,,,, 1 ,,,, 0 ,,,, 0 ,,,,-1 ,-1 ,-1 , 0 , 0 , 0 , 0 , 0
BC Mult= 1 ,0,137,0,146
BC Mult= 3 ,137,155,146,162
BC Mult= 1 ,155,250,162,250
BC Design=,, 0 ,, 0 ,,,,,,
BC Use User HTab Curves=0
BC User HTab FreeFlow(D)= 0

Type RM Length L Ch R = 1 ,150.3251,46.619,46.581,46.518
XS GIS Cut Line= 5
529951.8688944674780429.89509951529898.0775065694780385.19648778
529844.3287805754780392.48585639529832.1345755834780439.48787744
529781.0203245284780482.44102406
#Sta/Elev= 30
       0 111.792   3.928 110.643   5.328 110.522  11.829 110.745  22.765 110.138
  27.431 110.471  33.625 110.231  36.386 109.966  37.833 109.563  66.838 109.104
  73.273 108.654  77.716 109.338 129.506 107.539 131.572 106.958 132.937 107.253
  136.14  107.15 152.515  107.58 153.048 105.626 154.842 105.433 157.099 105.565
  159.65 107.348  159.69   107.6 159.776     108 164.759  108.39 191.522  108.93
 195.419 109.571 199.337  109.82 212.399 112.287 215.691 112.685 239.504 113.368
#Mann= 4 ,-1 , 0
       0     .04       0   3.928      .1       0 152.515    .034       0
  159.69      .1       0
#XS Ineff= 2 ,-1
     .66  127.75  126.67  184.14  239.65   125.4
Permanent Ineff=
       T       T
#Block Obstruct= 3 ,-1
   81.06  128.19  126.63  200.44  210.35  119.03  217.18  235.68  124.97
Bank Sta=152.515,159.69
XS Rating Curve= 0 ,0
Exp/Cntr=0.5,0.3

Type RM Length L Ch R = 1 ,103.7443,12.313,12.313,12.363
XS GIS Cut Line= 5
529951.8689309634780429.89509595529900.489765277 4780378.5972269
529801.6003678864780381.42073808529788.917586548 4780431.1014923
529775.4651753514780481.73323877
#Sta/Elev= 30
       0 111.792   4.266 110.661  12.856  110.73  24.479 110.191  31.227 110.427
  43.945 110.159  51.673 109.163  83.523 108.986  87.329  108.49   91.33 109.161
  96.615 109.494 103.952  109.26 107.283 108.688 144.356 109.078  164.36 108.776
 182.082 107.945 182.972 107.383 183.162 107.227 185.907 105.025 188.807 104.806
 190.485 105.014  190.92 107.206 192.129 107.233 192.557 107.729 198.968 107.714
 208.915 108.549 213.303 108.309 216.545 108.883 252.337 112.703 275.196 113.666
#Mann= 4 ,-1 , 0
       0     .04       0   4.266      .1       0 182.972    .034       0
 192.557      .1       0
#XS Ineff= 2 ,-1
    1.06  162.56  124.03  210.13  278.85     121
Permanent Ineff=
       T       T
#Block Obstruct= 1 ,-1
   145.9  163.35     124
Bank Sta=183.162,190.92
XS Rating Curve= 0 ,0
Exp/Cntr=0.5,0.3

Type RM Length L Ch R = 4 ,97.5769 ,,,
BEGIN DESCRIPTION:
E186
END DESCRIPTION:
Bridge Culvert--1,0,-1,-1, 0
Deck Dist Width WeirC Skew NumUp NumDn MinLoCord MaxHiCord MaxSubmerge Is_Ogee
0.01,12.11,1.44,0, 14, 14, , , 0.95, 0, ,,,
 164.802 165.411 174.716 180.711 180.729 182.283 182.716  190.92 190.975 192.587
 192.605 194.995   207.4 207.541
 105.716 105.871 108.246   108.3 109.401 109.383 109.379 109.287 109.286 109.268
 108.176 108.166 106.031 106.006
 105.716  12.834  12.937  13.002  13.003   13.02 107.444 107.351  13.391  13.425
  13.426  13.476  13.739 106.006
 182.642 183.251 192.556 198.551 198.569 200.123 200.556  208.76 208.815 210.427
 210.445 212.835  225.24 225.381
 105.716 105.871 108.246   108.3 109.401 109.383 109.379 109.287 109.286 109.268
 108.176 108.166 106.031 106.006
 105.716  12.834  12.937  13.002  13.003   13.02 107.444 107.351  13.391  13.425
  13.426  13.476  13.739 106.006
BR Coef=-1 , 0 , 0 ,, 0 ,,,0.8,0,,0,
WSPro=,,,, 1 ,,,, 0 ,,,, 0 ,,,,-1 ,-1 ,-1 , 0 , 0 , 0 , 0 , 0
BC Mult= 1 ,0,179,0,193
BC Mult= 3 ,179,195,193,213
BC Mult= 1 ,195,300,213,300
BC Design=,, 0 ,, 0 ,,,,,,
BC Use User HTab Curves=0
BC User HTab FreeFlow(D)= 0

Type RM Length L Ch R = 1 ,91.431  ,46.536,47.507,48.532
XS GIS Cut Line= 4
529951.8689309634780429.89509595529907.1676365494780368.95141284
529790.5459466784780377.45274854529764.3223888684780477.95739569
#Sta/Elev= 30
       0 111.792   5.127  110.65  35.672 110.046  42.139 110.378  44.608 110.187
  47.441 109.332  54.794 109.005  61.062 109.084  66.008 110.156   74.82 110.424
  89.386 109.305 114.257 108.626 142.609 108.454 156.031 109.248 194.488 107.863
 197.467 107.011 203.137 106.813 203.878 106.622 205.746 104.882 207.146 104.805
 208.054 106.237  208.78  106.88 209.565 107.581 209.571 107.997 219.576 108.078
 230.845 109.131 241.279 109.642 247.073 110.422 282.009 113.188 296.381 115.018
#Mann= 4 ,-1 , 0
       0     .04       0   5.127      .1       0 194.488    .034       0
 209.571      .1       0
#XS Ineff= 3 ,-1
     .53  180.26  112.93  190.04  201.67  107.87  223.61  287.05  113.23
Permanent Ineff=
       T       T       T
Bank Sta=203.137,208.78
XS Rating Curve= 0 ,0
Exp/Cntr=0.5,0.3