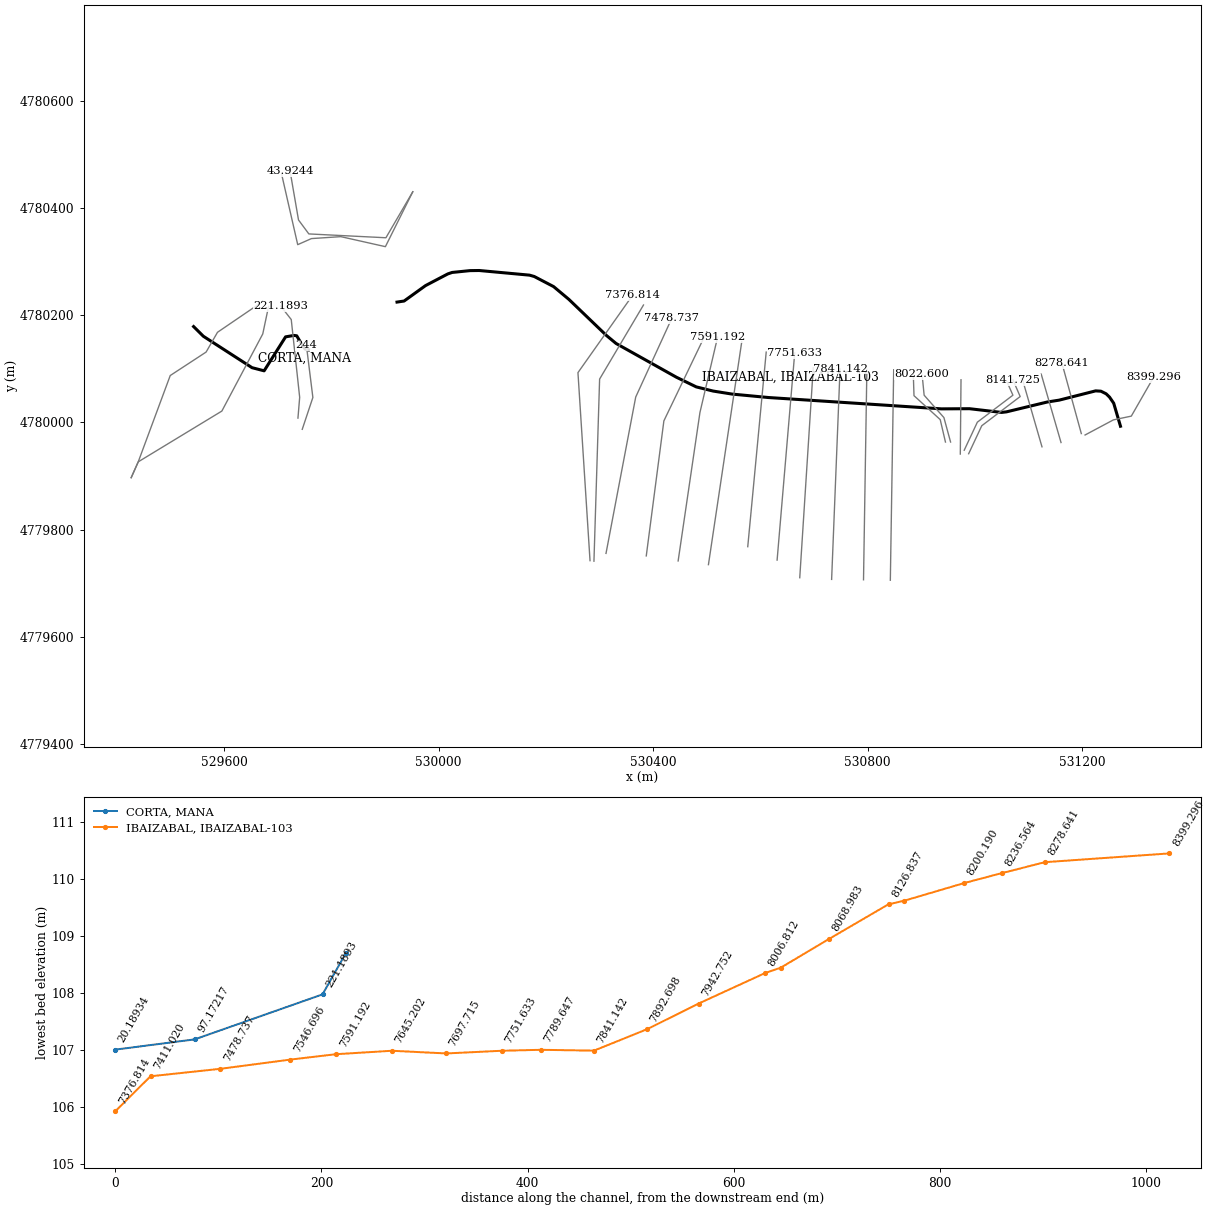
HEC-RAS study Durango.prj: Durango

--- Durango.g18 (geometry) --- (continued)

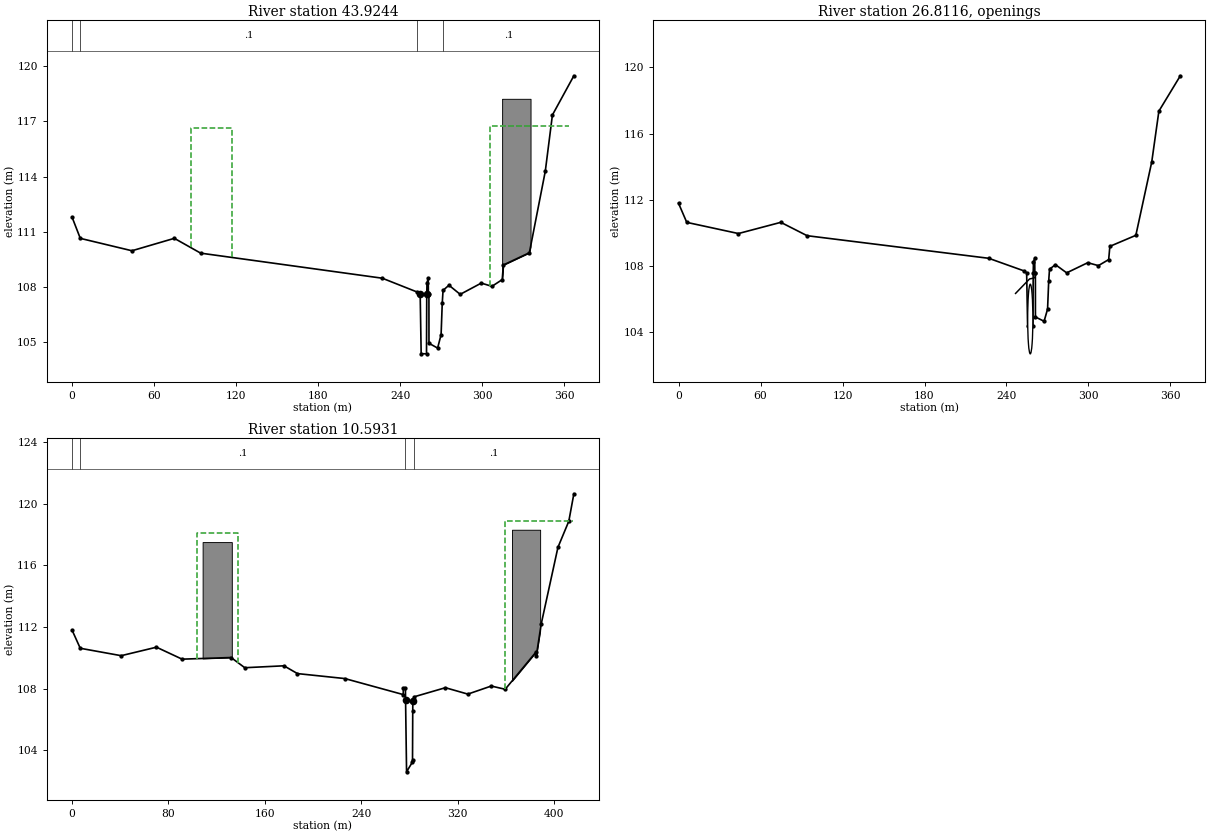
Type RM Length L Ch R = 1 ,43.9244 ,29.919,33.331,36.263
XS GIS Cut Line= 5
529951.8689309634780429.89509595529901.7987287954780344.17316274
529758.1332086974780351.32274952529738.8764973014780377.32082088
529723.2543950064780467.72026496
#Sta/Elev= 30
       0 111.792   6.022  110.64  43.813 109.966  74.838 110.642    94.1 109.836
 227.019 108.473 252.504 107.722 254.746   107.6  255.47  104.37  259.38  104.36
  259.55   107.6 259.739 108.226  260.64 108.463 260.758 107.587 261.145 107.607
 261.178 104.934 267.508 104.673 270.056 105.408 270.891 107.108 271.485 107.811
 275.796 108.091 284.034 107.595 299.461 108.207 307.255 108.031 314.777 108.396
 315.643 109.193 334.655 109.858 346.303 114.291 351.516 117.349  367.21 119.482
#Mann= 4 ,-1 , 0
       0     .04       0   6.022      .1       0 252.504    .034       0
 271.485      .1       0
Levee=0,,,-1,275.8,,,
#XS Ineff= 2 ,-1
    86.7     117  116.65   305.9   363.7  116.74
Permanent Ineff=
       T       T
#Block Obstruct= 1 ,-1
  314.71  335.51  118.23
Bank Sta=254.746,259.55
XS Rating Curve= 0 ,0
Exp/Cntr=0.5,0.3

Type RM Length L Ch R = 4 ,26.8116 ,,,
BEGIN DESCRIPTION:
E187
END DESCRIPTION:
Bridge Culvert--1,0,-1,-1, 0
Deck Dist Width WeirC Skew NumUp NumDn MinLoCord MaxHiCord MaxSubmerge Is_Ogee
0.01,33.13,1.44,0, 21, 25, , , 0.95, 0, ,,,
 246.636 246.757 255.429 255.552 255.718 255.954 256.273 256.682 256.853 257.183
 257.561 257.945 258.372  258.76 258.993 259.232 259.352 259.419 260.002  260.34
 260.559
 106.355 106.365 107.105 107.115 107.129 107.149 107.177 107.211 107.226 107.232
 107.239 107.245 107.253  107.26 107.264 107.268  107.27 107.272 107.282 107.288
 107.334
 269.601 269.722 278.394 278.517 278.683 278.919 279.238 279.647 279.818 280.148
 280.526  280.91 281.337 281.725 281.958 282.197 282.317 282.384 282.967 283.305
 283.524  283.54  283.91 293.601 293.736
 106.355 106.365 107.105 107.115 107.129 107.149 107.177 107.211 107.226 107.232
 107.239 107.245 107.253  107.26 107.264 107.268  107.27 107.272 107.282 107.288
 107.334 107.584 107.605 105.144  105.11
BR Coef=-1 , 0 , 0 ,, 0 ,,,0.8,0,,0,
WSPro=,,,, 1 ,,,, 0 ,,,, 0 ,,,,-1 ,-1 ,-1 , 0 , 0 , 0 , 0 , 0
Culvert=9,4.2,3.8,33,0.02,0.5,1,60,1,102.71,257.4,102.65,280.45,Culvert #1  , 0 ,0.2
Culvert Bottom n=0.02
Culvert Bottom Depth=0.036
BC Mult= 1 ,0,254,0,276.8
BC Mult= 2 ,254,259.5,276.8,282.9
BC Mult= 1 ,259.5,450,282.9,450
BC Design=,, 0 ,, 0 ,,,,,,
BC Use User HTab Curves=0
BC User HTab FreeFlow(D)= 0

Type RM Length L Ch R = 1 ,10.5931 ,0.717,10.593,0.526
XS GIS Cut Line= 6
529951.8689309634780429.89509595529900.8169160564780327.58129156
529817.7433632714780346.25106084529762.9253917314780342.62653683
529737.3809712844780331.31531477529707.6163544394780461.68704897
#Sta/Elev= 30
       0 111.792    6.79 110.615  40.769 110.134  70.062 110.685  91.337 109.909
 132.006 110.015 143.359 109.354 175.887 109.478 187.108 108.973 226.436 108.651
 274.882 107.613  275.02 108.028 276.725 108.012  276.84 107.286 277.673 102.603
 282.563 103.242 282.613 103.369 282.793 106.516 282.878 107.203 284.149 107.473
 309.905 108.058 328.541 107.643 347.979 108.166 359.539 107.956 385.184 110.377
 385.378  110.13 389.489 112.207 403.328 117.159 412.356 118.854 416.546 120.632
#Mann= 4 ,-1 , 0
       0     .04       0    6.79      .1       0 276.725    .034       0
 284.149      .1       0
Levee=0,,,-1,303.15,,,
#XS Ineff= 2 ,-1
  103.96  137.89  118.07  359.03  415.42  118.87
Permanent Ineff=
       T       T
#Block Obstruct= 2 ,-1
  108.37   132.6   117.5   365.2  388.55   118.3
Bank Sta=276.84,282.878
XS Rating Curve= 0 ,0
Exp/Cntr=0.5,0.3

River Reach=CORTA           ,MANA
Reach XY= 30
529757.298750791 4780135.1965144529750.9744146574780136.68459349
529739.8138214784780154.16952281529735.5355940924780161.42390837
529730.4382934574780162.13012695529714.7758789064780159.46429443
529711.043701172 4780153.5546875529704.1121215824780142.58007813
529703.5791015634780141.73571777529696.647521973 4780130.7611084
529695.0480957034780128.22827148529688.6497192384780118.09790039
529686.5170898444780114.72088623529684.9174804694780112.18847656
 529674.786926274780096.14831543 529652.293090824780101.98010254
529613.137329102  4780127.253479529612.3040771484780127.79107666
529611.4711303714780128.32891846529600.640686035 4780135.3192749
 529591.476684574780141.23449707529588.9772949224780142.84747314
529586.4780883794780144.46087646529581.4793090824780147.68707275
529572.3153076174780153.60229492529569.815917969  4780155.215271
529567.3167114264780156.82867432529562.3178710944780160.05487061
529561.484924316 4780160.5927124529543.3300327784780178.63578216

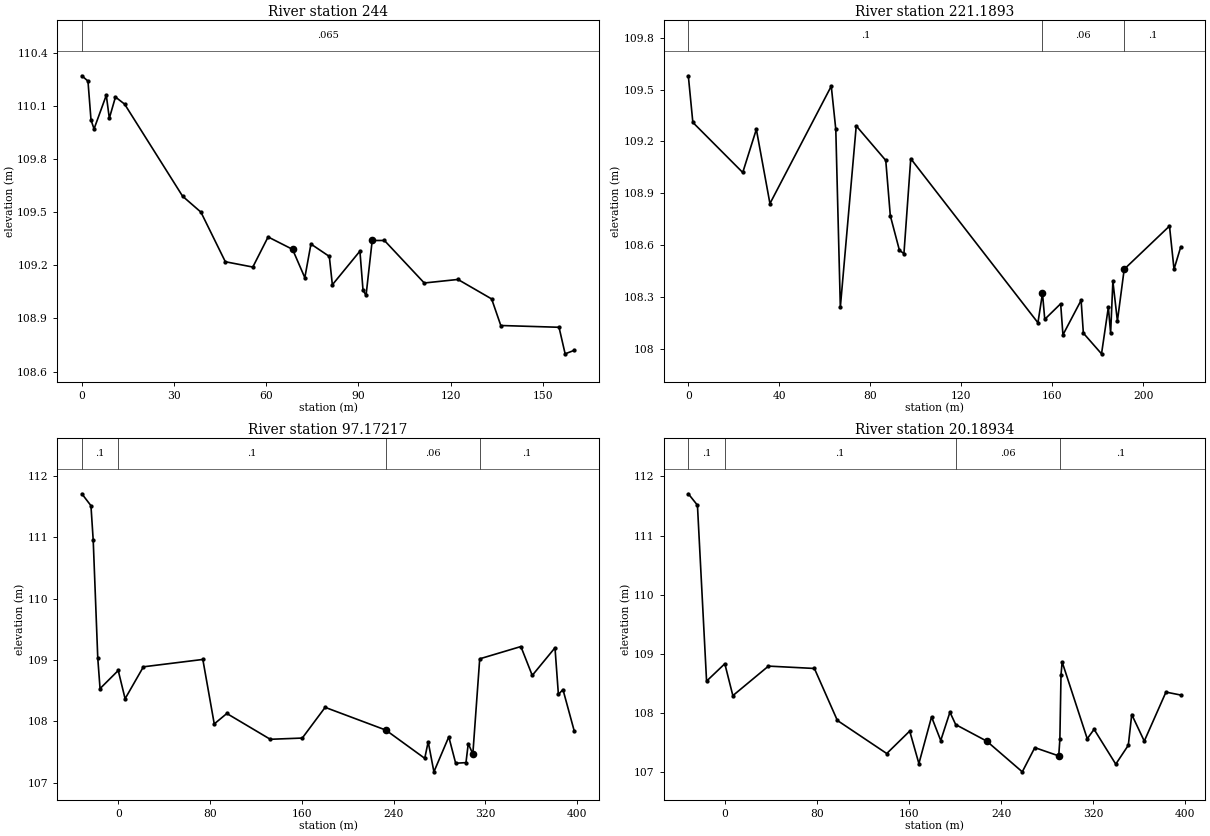
Type RM Length L Ch R = 1 ,244     ,23,22.8,22.6
XS GIS Cut Line= 3
      529745.839      4779987.14      529765.626     4780046.502
       529753.58       4780143.4
#Sta/Elev= 30
       0  110.27    1.99  110.24    2.98  110.02    3.97  109.97    7.95  110.16
    8.94  110.03   10.93  110.15   13.91  110.11   32.78  109.59   38.74   109.5
   46.68  109.22   55.62  109.19   60.59  109.36   68.55  109.29   72.54  109.13
   74.53  109.32   80.51  109.25    81.5  109.09   90.47  109.28   91.47  109.06
   92.46  109.03   94.46  109.34   98.44  109.34   111.4   109.1  122.36  109.12
  133.32  109.01   136.3  108.86  155.24  108.85  157.23   108.7  160.22  108.72
#Mann= 1 ,-1 , 0
       0    .065       0
#XS Ineff= 2 , 0
       0   68.55     130   94.46       0     130
Permanent Ineff=
       T       T
Bank Sta=68.55,94.46
XS Rating Curve= 0 ,0
Exp/Cntr=0.3,0.1

Type RM Length L Ch R = 1 ,221.1893,149.57,124.02,99.8
XS GIS Cut Line= 4
529737.8262939454780008.01849365529741.0327148444780046.76647949
529725.329711914 4780191.7177124529705.7024339054780216.79686809
#Sta/Elev= 30
       0  109.58    1.99  109.31   23.93  109.02   29.91  109.27   35.89  108.84
   62.85  109.52   64.84  109.27   66.84  108.24   73.83  109.29   86.81  109.09
   88.81  108.77   92.81  108.57    94.8  108.55    97.8   109.1  153.72  108.15
  155.72  108.32  156.72  108.17  163.71  108.26  164.71  108.08   172.7  108.28
  173.69  108.09  181.68  107.97  184.68  108.24  185.68  108.09  186.67  108.39
  188.66  108.16  191.65  108.46  211.56  108.71  213.55  108.46  216.53  108.59
#Mann= 3 ,-1 , 0
       0      .1       0  155.72     .06       0  191.65      .1       0
#XS Ineff= 2 , 0
       0  153.74     130  192.51       0     130
Permanent Ineff=
       T       T
Bank Sta=155.72,191.65
XS Rating Curve= 0 ,0
Exp/Cntr=0.3,0.1

Type RM Length L Ch R = 1 ,97.17217,119.45,76.98,72.27
XS GIS Cut Line= 5
         529427.        4779897.      529440.129     4779926.513
  529595.9902954 4780021.1397095  529672.2192993 4780164.8500977
   529683.068652 4780216.2412281
#Sta/Elev= 30
-31.7089111.7073-23.7816111.5138-21.7998110.9474-17.8362109.0329-15.8545108.5354
       0  108.83    5.98  108.37   21.92  108.89   73.73  109.01   83.69  107.96
   94.65  108.13  132.51  107.71  160.41  107.73  180.33  108.23  233.21  107.86
  267.14   107.4  270.14  107.67  275.13  107.18   288.1  107.75  294.09  107.32
  303.07  107.33  305.07  107.64  309.06  107.47  315.05  109.02  350.93  109.22
  360.84  108.75  380.66   109.2  383.63  108.44   387.6  108.52  397.51  107.84
#Mann= 4 ,-1 , 0
-31.7089      .1       0       0      .1       0  233.21     .06       0
  315.05      .1       0
#XS Ineff= 2 , 0
       0  232.98     135  320.65       0  135.47
Permanent Ineff=
       T       T
Bank Sta=233.21,309.06
XS Rating Curve= 0 ,0
Exp/Cntr=0.3,0.1

Type RM Length L Ch R = 1 ,20.18934,26.77,20.19,30.33
XS GIS Cut Line= 6
         529427.        4779897.      529440.129     4779926.513
  529499.7669067  4780087.371521  529566.6234741 4780131.1094971
  529587.8676758 4780167.9743042  529672.2192993  4780225.458313
#Sta/Elev= 30
-31.7089111.7073-23.7816111.5138-15.8545108.5354       0  108.83    6.98  108.29
   37.91  108.79   77.82  108.75   97.77  107.87  140.67  107.31  160.62  107.69
   168.6  107.14  179.59  107.93  187.58  107.53  195.57  108.01  200.56   107.8
  227.52  107.52  258.42     107   269.3  107.41  290.08  107.27  291.07  107.55
  292.06  108.64  293.05  108.86  314.85  107.56   320.8  107.72  339.63  107.13
  350.53  107.45   353.5  107.97   364.4  107.52  383.23  108.35  396.12   108.3
#Mann= 4 ,-1 , 0
-31.7089      .1       0       0      .1       0  200.56     .06       0
  291.07      .1       0
#XS Ineff= 2 , 0
       0  226.23     135  293.63       0     130
Permanent Ineff=
       T       T
Bank Sta=227.52,290.08
XS Rating Curve= 0 ,0
Exp/Cntr=0.3,0.1

River Reach=IBAIZABAL       ,IBAIZABAL-103
Reach XY= 30
 531271.005100254779992.86631992531258.3793598084780035.70140406
531250.6364128594780047.08332118531244.2598285754780053.30538145
531234.5430965614780058.16162525 531224.674508944780058.76871526
531156.6719062144780041.49930407531134.5740462214780038.01649594
531058.4755926844780019.66984694531049.251237527 4780018.6059428
 530989.562306654780025.54774895 530937.392648094780025.25059866
530614.9122581484780046.37180679530547.2338541754780052.77346339
530511.6666615684780058.43414908 530480.314165354780066.17583917
530443.2749077644780084.20037127530330.7690465044780147.13629793
530312.7953774224780162.08694367530242.9163618244780229.23712532
530214.381693129 4780253.1138445530178.3187465894780271.94628795
530169.4824168124780274.47954855530075.6930675544780283.13330224
530058.5194264464780282.91180011530025.1986610484780279.51314373
530017.1395077334780276.77518415529975.6585020534780255.02402829
 529935.701905944780226.24725467529922.4819193484780224.27112185

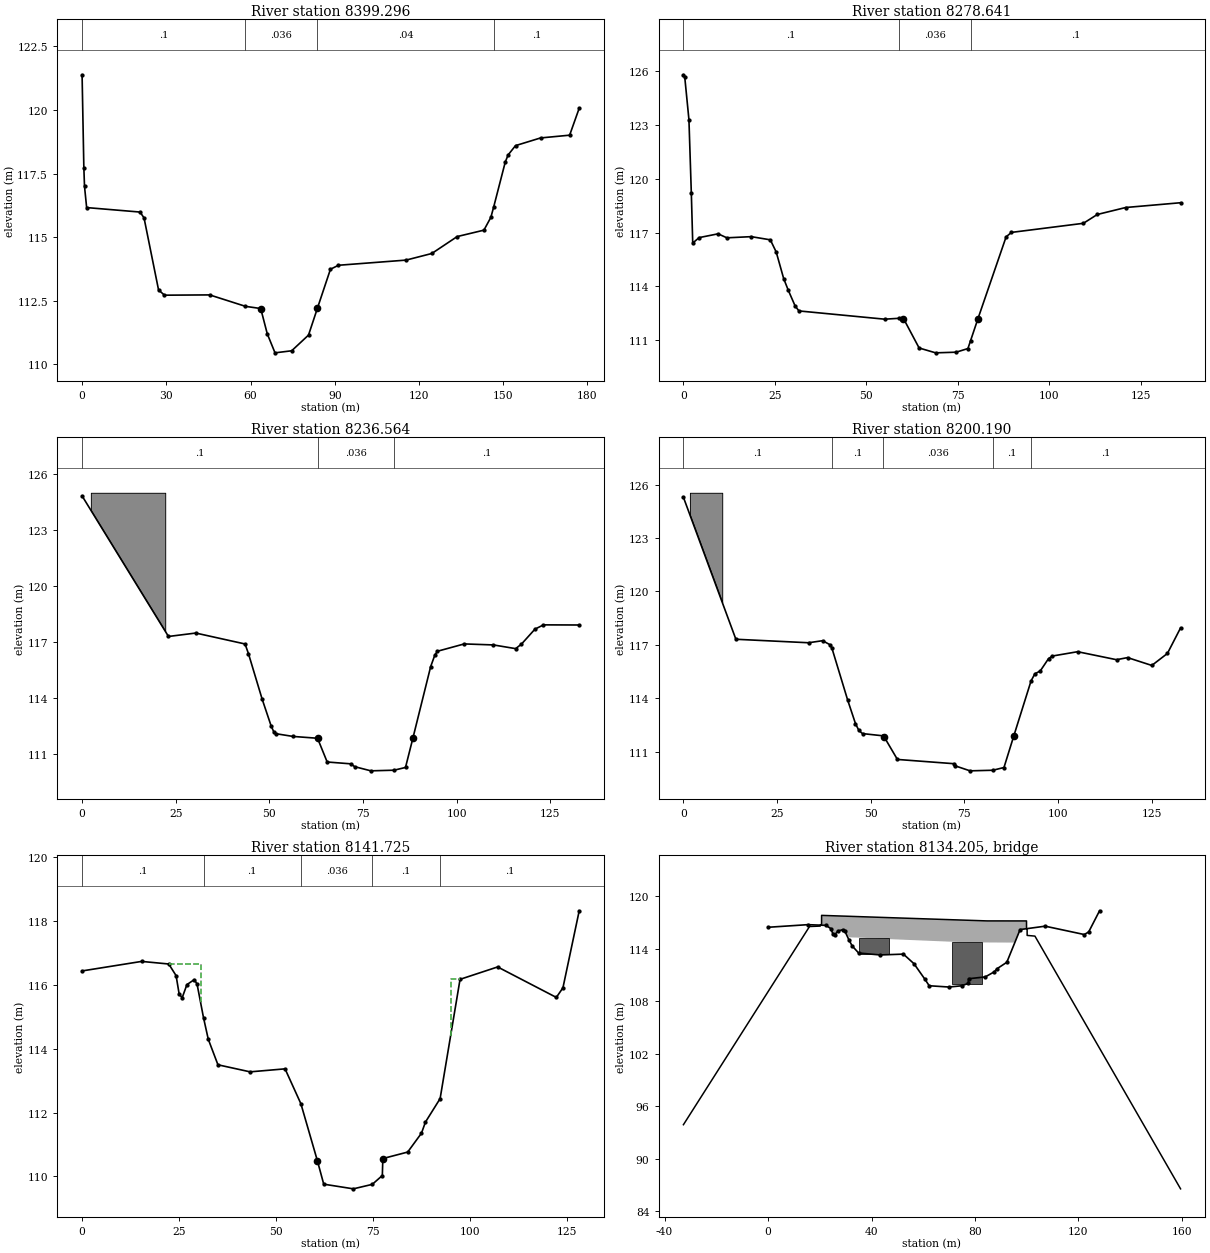
Type RM Length L Ch R = 1 ,8399.296,102.496,120.656,139.214
XS GIS Cut Line= 4
531205.0119575084779976.55092008531257.7753848424780004.69141466
531291.192222154 4780011.7265383531332.5235735654780083.83655566
#Sta/Elev= 30
       0 121.384    .628 117.735     .86 116.998   1.624  116.16  20.635 115.984
  22.062 115.756  27.236 112.921  29.346 112.714  45.441 112.725  58.201 112.275
  63.622 112.189  65.962 111.192  68.717 110.446  74.649 110.527  80.646 111.144
  83.839 112.208  88.455 113.734  91.318 113.891 115.398 114.094 124.558 114.354
   133.6  115.02 143.119 115.272 145.596 115.776 146.608 116.188 150.716 117.948
 151.724 118.229 154.372 118.597 163.282 118.899 173.651 119.008 177.063  120.07
#Mann= 4 ,-1 , 0
       0      .1       0  58.201    .036       0  83.839     .04       0
 146.608      .1       0
Bank Sta=63.622,83.839
XS Rating Curve= 0 ,0
Exp/Cntr=0.3,0.1

Type RM Length L Ch R = 1 ,8278.641,41.919,42.077,42.235
XS GIS Cut Line= 2
531197.9767944674779979.18909951531161.9217944674780110.21829951
#Sta/Elev= 30
       0 125.793    .353 125.684   1.506 123.292   2.162  119.18   2.543 116.412
   4.295 116.716   9.482 116.927  11.878 116.704  18.546 116.769  23.755 116.592
  25.361 115.915  27.412 114.426  28.682 113.772  30.547 112.899  31.584 112.628
   55.03 112.168  58.967 112.218  60.157 112.203  64.432 110.562  68.941 110.292
  74.556 110.328   77.77 110.531  78.482 110.962  80.483 112.178  88.214 116.759
  89.665 117.006  109.33 117.513  113.14 118.005 120.912 118.394 135.899  118.66
#Mann= 3 ,-1 , 0
       0      .1       0  58.967    .036       0  78.482      .1       0
Bank Sta=60.157,80.483
XS Rating Curve= 0 ,0
Exp/Cntr=0.3,0.1

Type RM Length L Ch R = 1 ,8236.564,36.381,36.374,36.367
XS GIS Cut Line= 2
531160.1630442744779962.48067279 531123.228645144780089.99228884
#Sta/Elev= 28
       0 124.811  23.071  117.29  30.359 117.473   43.52 116.888  44.429 116.369
  48.075 113.942  50.497 112.494  51.181 112.192  51.704 112.088  56.341  111.94
  62.875 111.843  65.447 110.572  71.819 110.473  72.765 110.323  77.121 110.099
  83.302 110.133  86.364  110.28   88.35  111.86  93.083 115.677   94.21   116.3
  94.907   116.5 102.049 116.891 109.845 116.837 115.776 116.639 117.303 116.876
 120.935 117.683 123.212 117.911 132.752 117.904
#Mann= 3 ,-1 , 0
       0      .1       0  62.875    .036       0  83.302      .1       0
#Block Obstruct= 1 ,-1
    2.34    22.2  124.98
Bank Sta=62.875,88.35
XS Rating Curve= 0 ,0
Exp/Cntr=0.3,0.1

Type RM Length L Ch R = 1 ,8200.190,74.806,58.464,37.343
XS GIS Cut Line= 2
531124.6684944674779954.50559951531087.7340944674780082.01719951
#Sta/Elev= 30
       0 125.286  14.008 117.314  33.404 117.118  37.161 117.233  39.168 117.004
  39.635 116.828  43.867 113.893  45.949 112.574  46.848 112.194   47.82 112.017
  53.237 111.893  53.559 111.847   57.14 110.565  72.373 110.324  72.555 110.206
  76.538 109.925  82.625 109.958  85.597 110.112   88.21  111.88  92.824 114.971
   93.84 115.373  95.284 115.534  97.493 116.225  98.521 116.372 105.267 116.615
 115.646 116.166 118.608 116.284 125.073 115.844 129.238 116.516 132.752 117.951
#Mann= 5 ,-1 , 0
       0      .1       0  39.635      .1       0  53.237    .036       0
  82.625      .1       0  92.824      .1       0
#Block Obstruct= 1 ,-1
    1.73   10.36  125.54
Bank Sta=53.559,88.21
XS Rating Curve= 0 ,0
Exp/Cntr=0.5,0.3

Type RM Length L Ch R = 1 ,8141.725,14.804,14.889,19.651
XS GIS Cut Line= 4
530987.9874804214779941.59480175531012.4478258844779993.81654986
531084.020563601  4780048.203195  531070.61706734780079.15951769
#Sta/Elev= 30
       0 116.434  15.354 116.732  22.345 116.651  24.242 116.287  25.023 115.716
  25.804 115.593  27.029 116.005  28.927 116.162  29.646 116.024  31.313 114.969
  32.543 114.294  35.034 113.496  43.326 113.275  52.338 113.369   56.42 112.278
  60.701 110.482  62.312 109.759  69.955 109.613  74.827 109.753  77.424  110.03
  77.553 110.561  83.961 110.764  87.512 111.354  88.546 111.704  92.323 112.437
  97.463 116.171 107.155 116.559 122.292 115.605 123.994 115.905 128.194 118.317
#Mann= 5 ,-1 , 0
       0      .1       0  31.313      .1       0   56.42    .036       0
  74.827      .1       0  92.323      .1       0
#XS Ineff= 2 ,-1
   22.34   30.66  116.65   95.04   97.46  116.17
Permanent Ineff=
       T       T
Bank Sta=60.701,77.553
XS Rating Curve= 0 ,0
Skew Angle= 45
Exp/Cntr=0.5,0.3

Type RM Length L Ch R = 3 ,8134.205,,,
BEGIN DESCRIPTION:
E38
END DESCRIPTION:
Bridge Culvert--1,0,-1,-1, 0
Deck Dist Width WeirC Skew NumUp NumDn MinLoCord MaxHiCord MaxSubmerge Is_Ogee
0.01,14.69,1.44,45, 27, 27, , , 0.95, 0, ,,,
 -32.737 -31.959  16.023  20.171  20.187  20.686  20.696  22.226  22.724  36.593
  44.857  50.733  64.234   72.52   80.96  84.673  95.044  95.758  96.867  99.945
  99.957 100.181 100.191 101.435 103.198  158.66  159.52
  93.898  94.259 116.519 116.569  116.73 116.733 117.793 117.778 117.773 117.636
 117.554 117.496 117.363 117.282 117.199 117.162  117.16  117.16  117.16 117.159
 116.256 116.264 115.505 115.473 115.426  87.018  86.577
  93.898-224.542-224.302-224.281-224.281-224.278-224.278-224.271 115.369 115.235
 115.107 115.034 114.867 114.766 114.705   114.7 114.687 112.337-220.543-220.562
-220.562-220.564-220.564-220.572-220.583-220.936  86.577
  -37.12 -36.342   11.64  15.788  15.805  16.303  16.314  17.843  18.342  32.211
  40.474   46.35  59.851  68.138  76.578  80.291  90.661  91.375  92.485  95.563
  95.574  95.798  95.809  97.053  98.815 154.277 155.137
  93.898  94.259 116.519 116.569  116.73 116.733 117.793 117.778 117.773 117.636
 117.554 117.496 117.363 117.282 117.199 117.162  117.16  117.16  117.16 117.159
 116.256 116.264 115.505 115.473 115.426  87.018  86.577
  93.898-224.542-224.302-224.281-224.281-224.278-224.278-224.271 115.369 115.235
 115.107 115.034 114.867 114.766 114.705   114.7 114.687 112.337-220.543-220.562
-220.562-220.564-220.564-220.572-220.583-220.936  86.577
Pier Skew, UpSta & Num, DnSta & Num=  ,40.85, 7 ,36.465, 7 , 5 , 5 , 0 ,,
     1.4     1.4    .742    .742    1.47   11.57   11.57
     108 114.191 114.191  114.53  114.53  115.17     116
     1.4     1.4    .742    .742    1.47   11.57   11.57
     108 114.191 114.191  114.53  114.53  115.17     116
Pier Skew, UpSta & Num, DnSta & Num=  ,76.792, 7 ,72.408, 7 , 5 , 5 , 0 ,,
     1.4     1.4    .742    .742    1.47   11.57   11.57
     108   113.6   113.6  113.94  113.94  114.58     116
     1.4     1.4    .742    .742    1.47   11.57   11.57
     108   113.6   113.6  113.94  113.94  114.58     116
BR Coef=-1 , 1 , 0 ,, 0 ,,,0.8,-1,0.6,0,
WSPro=,,,, 1 ,,,, 0 ,,,, 0 ,,,,-1 ,-1 ,-1 , 0 , 0 , 0 , 0 , 0
BC Design=,, 0 ,, 0 ,,,,,,
BC Use User HTab Curves=0
BC User HTab FreeFlow(D)= 0

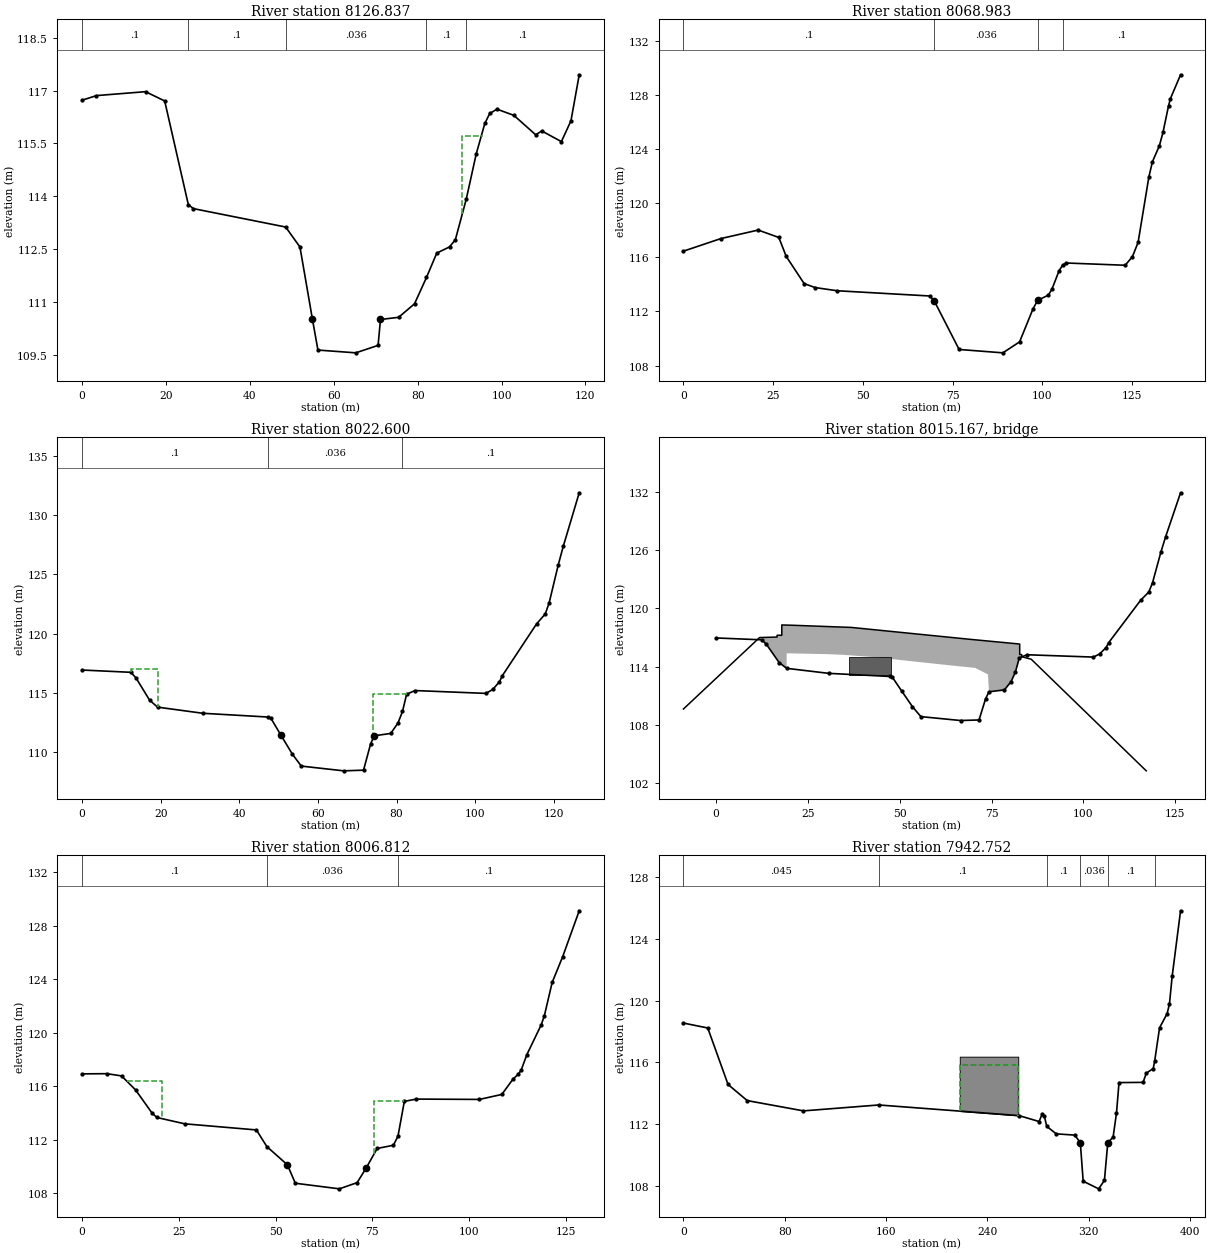
Type RM Length L Ch R = 1 ,8126.837,44.895,57.853,70.915
XS GIS Cut Line= 4
530979.7466078234779948.20881783531004.2069532874780000.43056594
531070.4790292334780050.70902068531059.6844523964780075.18769875
#Sta/Elev= 30
       0 116.728   3.433 116.859  15.136  116.97  19.693 116.706  25.324 113.764
  26.536 113.649  48.532 113.126   51.94 112.559  54.918 110.504  56.226 109.632
  65.242 109.553  70.564 109.765  71.138   110.5  75.459 110.562  79.248 110.945
  82.105 111.694  84.549 112.385  87.599 112.562  88.989 112.766  91.581 113.915
  93.972 115.207  96.008 116.067  97.178 116.351  98.915 116.473 102.945 116.297
 108.138 115.746 109.592 115.854 114.266 115.552 116.547 116.143 118.515  117.45
#Mann= 5 ,-1 , 0
       0      .1       0  25.324      .1       0  48.532    .036       0
  82.105      .1       0  91.581      .1       0
#XS Ineff= 1 ,-1
   90.66    95.6   115.7
Permanent Ineff=
       T
Bank Sta=54.918,71.138
XS Rating Curve= 0 ,0
Skew Angle= 45
Exp/Cntr=0.5,0.3

Type RM Length L Ch R = 1 ,8068.983,35.664,46.383,57.131
XS GIS Cut Line= 2
530972.4259944674779940.96619951530973.7450944674780079.47019951
#Sta/Elev= 30
       0 116.455  10.429 117.385  20.823 118.014  26.584 117.466   28.64 116.066
  33.627 114.061  36.677 113.766  42.802  113.53  68.627 113.143   69.88  112.78
  76.813 109.191   89.01 108.942  93.659 109.752  97.376 112.176  98.679 112.818
  101.68 113.206  102.68  113.65  104.68 115.019  105.68 115.432  106.68  115.58
 123.076 115.413 125.104  116.05 126.681 117.104 129.681  121.94 130.681  123.07
 132.599 124.236 133.608 125.223 135.152 127.182 135.681 127.726  138.51 129.488
#Mann= 4 ,-1 , 0
       0      .1       0   69.88    .036       0  98.679      .1       0
  105.68      .1       0
Bank Sta=69.88,98.679
XS Rating Curve= 0 ,0
Exp/Cntr=0.5,0.3

Type RM Length L Ch R = 1 ,8022.600,12.996,15.788,18.552
XS GIS Cut Line= 4
530954.2923882774779963.42275946530941.8689622534780008.97935219
530905.0266021834780050.67492781530901.1201248884780090.23969927
#Sta/Elev= 30
       0 116.942  12.395  116.75  13.701 116.283  17.153  114.41  19.189 113.814
  30.683 113.296  47.249  112.98 47.9653 112.90950.53634  111.4753.45528 109.863
55.74418 108.84366.54099 108.44271.58125 108.49873.36175 110.68174.27391 111.397
78.49039 111.59580.32392 112.45881.49277 113.44782.54211 114.89784.65282 115.212
102.7272 114.972104.4372 115.302106.1582 115.952106.9012 116.472115.5812 120.827
117.8002 121.672118.8052  122.62121.1072 125.807122.3852 127.374126.4412 131.888
#Mann= 3 ,-1 , 0
       0      .1       0  47.249    .036       081.49277      .1       0
#XS Ineff= 2 ,-1
    12.4    19.2     117   74.02   82.54   114.9
Permanent Ineff=
       T       T
Bank Sta=50.53634,74.27391
XS Rating Curve= 0 ,0
Exp/Cntr=0.5,0.3

Type RM Length L Ch R = 3 ,8015.167,,,
BEGIN DESCRIPTION:
E39
END DESCRIPTION:
Bridge Culvert--1,0,-1,-1, 0
Deck Dist Width WeirC Skew NumUp NumDn MinLoCord MaxHiCord MaxSubmerge Is_Ogee
0.01,15.59,1.44,45, 28, 28, , , 0.95, 0, ,,,
  -8.899  -7.288  11.829  16.601  16.608  17.874  17.884  18.402  19.216  20.719
  30.521  34.663   36.84   43.06  53.867  64.871  69.073  70.742  70.766  74.017
   75.44  82.644  82.655    83.2  83.209  85.798 116.064 117.099
 109.627 110.199 116.984 117.036 117.222 117.218  118.28 118.275 118.266 118.251
 118.114 118.056 118.026  117.79  117.38 116.963 116.804 116.744 116.743 116.626
 116.575 116.316 115.246 115.225  115.01 114.747  103.64 103.261
 109.627-148.999-148.732-148.665-148.665-148.647-148.647 -148.64 115.363 115.351
 115.272 115.203 115.142 114.966 114.518 114.076 113.915 113.851 113.811 113.186
-145.227-145.416-145.416 -145.43-145.431-145.498-146.291 103.261
  -7.544  -5.932  13.185  17.956  17.964   19.23   19.24  19.758  20.571  22.074
  31.876  36.018  38.196  44.415  55.222  66.226  70.428  72.098  72.121  75.372
  76.796  83.999  84.011  84.555  84.565  87.154  117.42 118.454
 109.627 110.199 116.984 117.036 117.222 117.218  118.28 118.275 118.266 118.251
 118.114 118.056 118.026  117.79  117.38 116.963 116.804 116.744 116.743 116.626
 116.575 116.316 115.246 115.225  115.01 114.747  103.64 103.261
 109.627-148.999-148.732-148.665-148.665-148.647-148.647 -148.64 115.363 115.351
 115.272 115.203 115.142 114.966 114.518 114.076 113.915 113.851 113.811 113.186
-145.227-145.416-145.416 -145.43-145.431-145.498-146.291 103.261
Pier Skew, UpSta & Num, DnSta & Num=  ,41.86, 7 ,40.86, 7 , 5 , 5 , 0 ,,
     1.4     1.4    .742    .742    1.47   11.57   11.57
     108 114.191 114.191  114.53  114.53  115.17     116
     1.4     1.4    .742    .742    1.47   11.57   11.57
     108 114.191 114.191  114.53  114.53  115.17     116
BR Coef=-1 , 1 , 0 ,, 0 ,,,0.8,-1,0.6,0,
WSPro=,,,, 1 ,,,, 0 ,,,, 0 ,,,,-1 ,-1 ,-1 , 0 , 0 , 0 , 0 , 0
BC Design=,, 0 ,, 0 ,,,,,,
BC Use User HTab Curves=0
BC User HTab FreeFlow(D)= 0

Type RM Length L Ch R = 1 ,8006.812,77.644,64.06,50.476
XS GIS Cut Line= 4
530944.7401540454779963.36309695530934.9808627114780005.23766011
530886.129190816 4780049.7970365530884.8040253724780089.62602768
#Sta/Elev= 30
       0 116.938   6.423 116.951  10.198 116.784  13.802 115.741   18.03 114.024
    19.3 113.677  26.505 113.20345.01257 112.74647.71442 111.50253.01561 110.141
55.07258  108.76 66.4471 108.34271.04117 108.80773.41634 109.92276.20659 111.361
80.39973   111.681.58202 112.27883.22321  114.8886.30761 115.052102.6094 115.027
108.3934 115.399111.2584 116.533112.6744 116.919113.3964 117.217114.8794 118.381
118.5794 120.604119.3994 121.299121.4014 123.773124.1274 125.705128.3895  129.13
#Mann= 3 ,-1 , 0
       0      .1       047.71442    .036       081.58202      .1       0
#XS Ineff= 2 ,-1
    11.6   20.57   116.4   75.37   83.22   114.9
Permanent Ineff=
       T       T
Bank Sta=53.01561,73.41634
XS Rating Curve= 0 ,0
Exp/Cntr=0.5,0.3

Type RM Length L Ch R = 1 ,7942.752,50.054,50.054,50.054
XS GIS Cut Line= 2
530842.0074944674779705.81479951530848.2608944674780098.21829951
#Sta/Elev= 30
       0 118.547  19.214 118.227  35.231 114.569  50.351 113.526  94.753 112.859
 154.153 113.242  264.86 112.554 280.783  112.17 283.114 112.635 284.862  112.53
 286.862 111.851 294.344 111.371  308.92  111.29  313.32   110.8 315.576 108.304
 327.796  107.81 332.351 108.359 334.998 110.795 339.201  111.16  341.87 112.715
  343.87 114.691 362.872 114.706 365.402 115.301 370.873 115.601 372.038 116.099
 375.874  118.24 381.875 119.161   383.7   119.8 385.875 121.607 392.453 125.819
#Mann= 6 ,-1 , 0
       0    .045       0 154.153      .1       0 286.862      .1       0
  313.32    .036       0 334.998      .1       0 372.038      .1       0
#XS Ineff= 1 ,-1
  217.96  264.08  115.86
Permanent Ineff=
       F
#Block Obstruct= 1 ,-1
  218.15  264.32  116.37
Bank Sta=313.32,334.998
XS Rating Curve= 0 ,0
Exp/Cntr=0.3,0.1

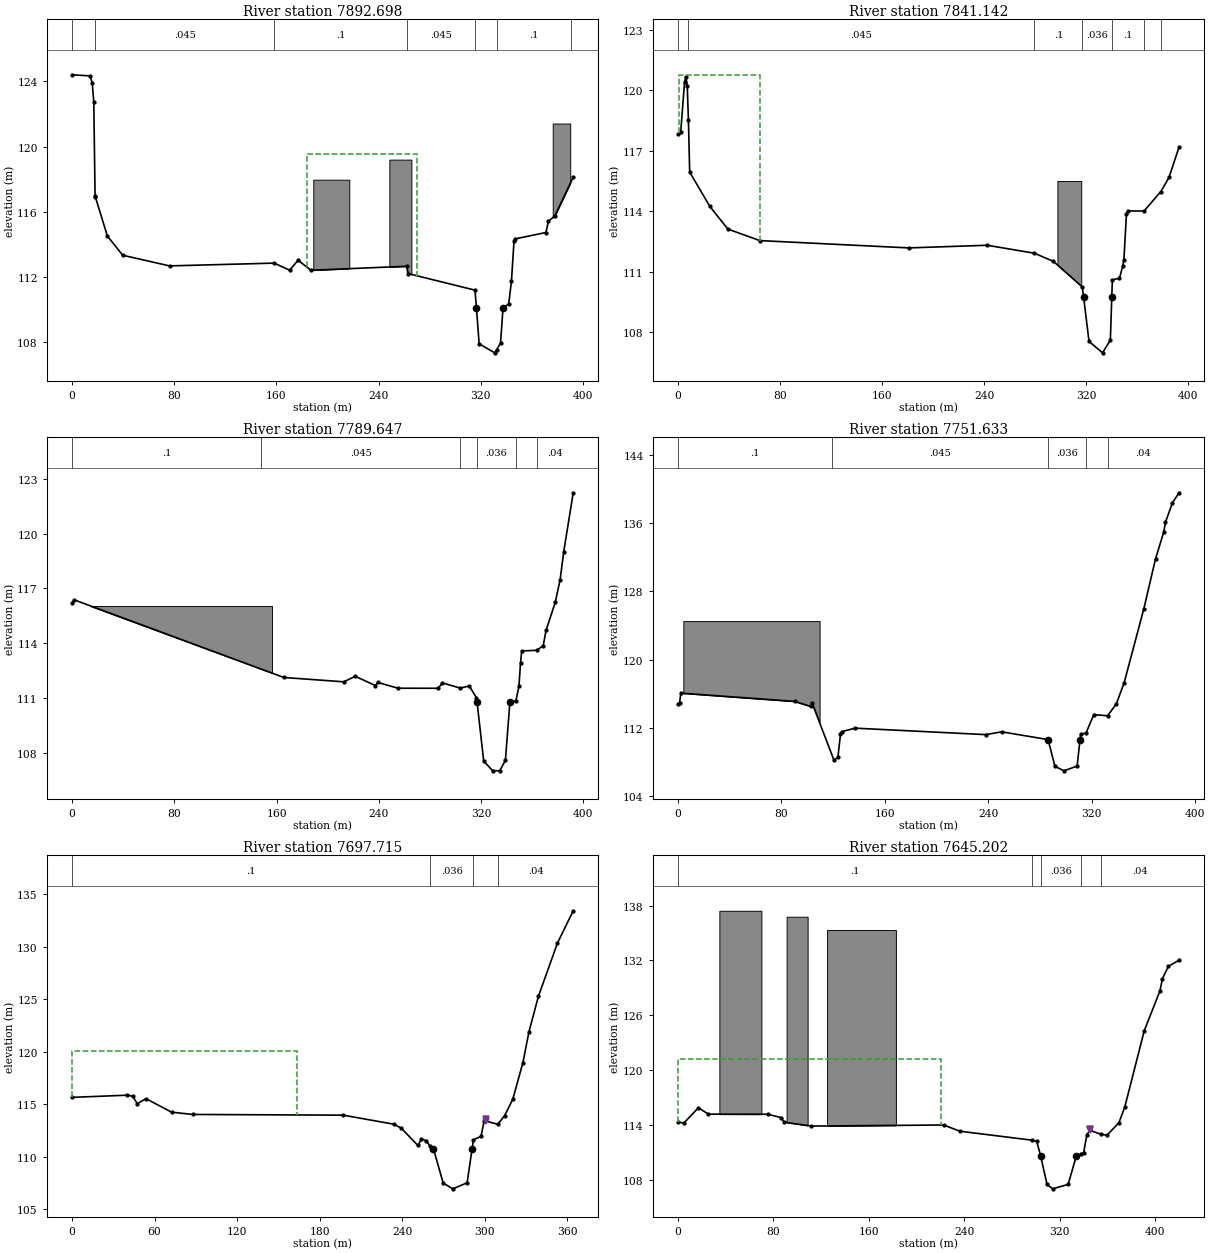
Type RM Length L Ch R = 1 ,7892.698,51.828,51.556,51.284
XS GIS Cut Line= 2
530792.0138399954779706.61147743530798.2672832344780099.01504071
#Sta/Elev= 30
       0 124.399  14.054 124.331  15.779 123.913  17.032 122.728  18.032 116.976
  18.328 116.897  27.648 114.521  39.678 113.339  76.348 112.687 158.297 112.857
 170.371 112.425  176.99 113.033 187.054  112.42 261.924 112.664 263.089 112.217
 315.537   111.2  316.66  110.12 318.787 107.915 330.997 107.359 332.605 107.562
 335.548 107.967 337.478 110.111 341.945 110.362 344.074 111.749 346.074 114.195
 346.844 114.342 371.077 114.733 373.077 115.427 378.078 115.755 392.454 118.128
#Mann= 7 ,-1 , 0
       0      .1       0  18.328    .045       0 158.297      .1       0
 261.924    .045       0 315.537    .036       0 332.605      .1       0
 390.374      .1       0
#XS Ineff= 1 ,-1
  183.61  269.96  119.52
Permanent Ineff=
       T
#Block Obstruct= 3 ,-1
   188.9  217.09  117.97  248.46  265.73   119.2  376.39  390.13  121.41
Bank Sta=316.66,337.478
XS Rating Curve= 0 ,0
Exp/Cntr=0.3,0.1

Type RM Length L Ch R = 1 ,7841.142,51.768,51.495,51.222
XS GIS Cut Line= 2
530732.5721944674779707.37809951530748.2735944674780099.81179951
#Sta/Elev= 30
       0 117.821   2.265 117.965   5.267  120.42   6.268 120.689   7.365 120.215
   8.287 118.531    9.27 115.953   25.08 114.245  39.224 113.123  64.252 112.552
 180.892 112.189 242.457  112.32 279.448 111.924 294.322 111.519  316.97  110.25
 317.969 109.757 322.197  107.55 332.775 106.982 338.934  107.61  340.04  109.75
 340.507   110.6  346.09  110.69 348.542 111.276 349.542 111.595 351.544 113.868
 352.545 114.023 365.295 114.019  378.53 114.986 384.896 115.688 392.748  117.19
#Mann= 7 ,-1 , 0
       0      .1       0   8.287    .045       0 279.448      .1       0
  316.97    .036       0 340.507      .1       0 365.295     .04       0
  378.53      .1       0
#XS Ineff= 1 ,-1
    1.06   64.49  120.78
Permanent Ineff=
       T
#Block Obstruct= 1 ,-1
  297.44  316.12  115.51
Bank Sta=317.969,340.04
XS Rating Curve= 0 ,0
Exp/Cntr=0.3,0.1

Type RM Length L Ch R = 1 ,7789.647,38.246,38.013,37.781
XS GIS Cut Line= 2
530673.1645246294779710.50484827530698.3136037924780101.81066908
#Sta/Elev= 30
       0 116.214   1.883 116.366 165.669 112.116 212.574 111.877 221.592  112.18
 237.222 111.675 239.375 111.841 255.028 111.526  286.48 111.524 289.724 111.819
 303.761 111.532 310.776 111.653 316.362 111.008  316.89  110.76 322.066  107.53
 328.987  107.01 334.566 106.997 339.046  107.57 342.537  110.75 347.256 110.829
 349.677 111.657 350.858 112.899 351.818  113.57 363.646 113.605 368.636 113.862
 370.841 114.693 378.006 116.226 381.894 117.486 384.695 119.021 392.113 122.241
#Mann= 6 ,-1 , 0
       0      .1       0 147.866    .045       0 303.761      .1       0
  316.89    .036       0 347.256      .1       0 363.646     .04       0
#Block Obstruct= 1 ,-1
     7.4  156.83  116.06
Bank Sta=316.89,342.537
XS Rating Curve= 0 ,0
Exp/Cntr=0.3,0.1

Type RM Length L Ch R = 1 ,7751.633,54.028,53.918,53.808
XS GIS Cut Line= 2
530630.9537944674779743.33539951530663.7843944674780129.48549951
#Sta/Elev= 30
       0 114.761   1.311 114.892   2.314 116.075  90.217 115.109 102.675  114.52
 103.679 114.971  120.74  108.22 123.751  108.55 125.758 111.253 126.762 111.561
  136.99 111.976 238.054  111.22 250.407 111.545 286.285 110.639 291.568  107.51
 298.565  106.98 308.734 107.543  310.98  110.62 311.476 111.308  315.46 111.366
 321.679 113.559 332.318 113.425 339.071 114.825 345.074  117.28  360.25 125.908
 369.371 131.796 375.656   134.9 377.035 136.079 382.486  138.36 387.543 139.525
#Mann= 5 ,-1 , 0
       0      .1       0 118.859    .045       0 286.285    .036       0
  315.46      .1       0 332.318     .04       0
#XS Ineff= 1 ,-1
      80  149.07  111.86
Permanent Ineff=
       T
#Block Obstruct= 1 ,-1
    4.23  109.61124.5067
Bank Sta=286.285,310.98
XS Rating Curve= 0 ,0
Exp/Cntr=0.3,0.1

Type RM Length L Ch R = 1 ,7697.715,53.122,52.514,51.906
XS GIS Cut Line= 2
530576.2361544164779768.34919824530610.6300922334780131.04890613
#Sta/Elev= 30
       0 115.641   40.22 115.848  44.119 115.741  47.448 115.031  53.726 115.519
  72.331 114.231  87.678 114.014 197.173 113.946 233.799 113.089 239.216 112.725
 251.415 111.059 253.984 111.651 257.552 111.527  260.13 110.996 262.753 110.734
 269.792  107.48 276.888 106.933 287.203  107.51  290.75  110.69 291.814   111.6
 297.293 111.932  299.63 113.422  309.46 113.081 314.412 113.889 320.368 115.456
 327.756 118.952 332.189 121.904 339.018 125.258 352.868 130.333 364.327 133.402
#Mann= 4 ,-1 , 0
       0      .1       0  260.13    .036       0 291.814      .1       0
  309.46     .04       0
Levee=0,,,-1,300.97,113.56,,Levee 3
#XS Ineff= 2 , 0
          163.17  120.08
Permanent Ineff=
       T       T
Bank Sta=262.753,290.75
XS Rating Curve= 0 ,0
Exp/Cntr=0.3,0.1

Type RM Length L Ch R = 1 ,7645.202,54.932,54.009,53.087
XS GIS Cut Line= 2
530502.9511721934779734.87580691530565.0802546964780150.47327099
#Sta/Elev= 30
       0 114.281   5.168 114.202  17.168 115.852    25.7 115.157  75.281  115.15
  86.708  114.78  89.098 114.285 111.996 113.854 222.882 113.971 236.447 113.291
 296.966 112.307 300.905 112.182 304.186 110.574 309.551  107.46 314.318  106.98
 327.249  107.47 334.053 110.566 338.106 110.826 340.231  110.93 342.908 112.901
 345.476  113.39 354.662 112.962 359.719 112.854  369.78 114.208  374.69 115.921
 391.063   124.3 404.208 128.652  406.23 129.981 411.272 131.339 420.216  132.02
#Mann= 5 ,-1 , 0
       0      .1       0 296.966      .1       0 304.186    .036       0
 338.106      .1       0 354.662     .04       0
Levee=0,,,-1,345.37,113.49,,Levee 3
#XS Ineff= 2 , 0
          220.26  121.24
Permanent Ineff=
       T       T
#Block Obstruct= 3 ,-1
    34.8   70.04  137.43   91.19  108.81  136.78  125.11  182.82  135.33
Bank Sta=304.186,334.053
XS Rating Curve= 0 ,0
Exp/Cntr=0.3,0.1

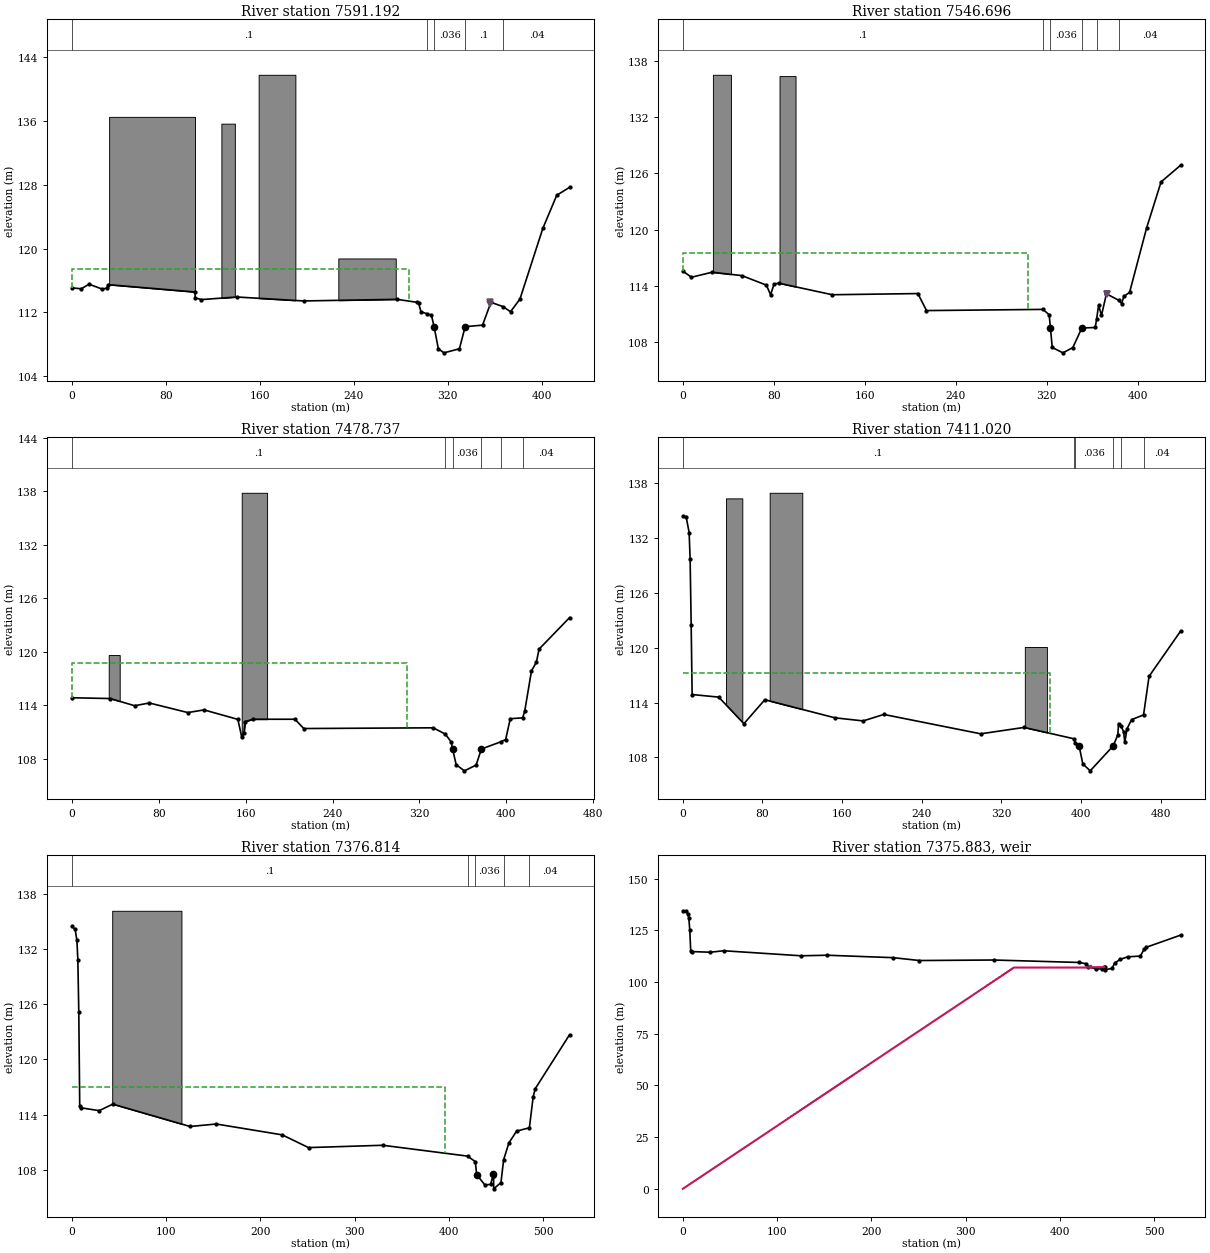
Type RM Length L Ch R = 1 ,7591.192,46.968,44.496,42.024
XS GIS Cut Line= 3
530446.4772071944779741.77206447530487.1245882524780018.48692782
530519.9832182234780158.74931431
#Sta/Elev= 30
       0 115.073   7.953 114.956  14.658 115.527  26.028 114.908   30.19 115.057
  30.786 115.476 104.941 114.548 104.984 113.821 110.252 113.599 140.359 113.925
 197.268  113.43 276.731  113.63 293.954 113.261 295.249 113.132 297.303 112.062
 302.087  111.84 306.147 111.652  308.47  110.18 312.039  107.43 316.869  106.92
 329.974  107.43 334.877   110.2 349.684 110.395 356.819  113.26 367.386 112.703
 373.479 112.074 381.523 113.664  401.01 122.537 412.862 126.687 423.744 127.682
#Mann= 5 ,-1 , 0
       0      .1       0 302.087      .1       0  308.47    .036       0
 334.877      .1       0 367.386     .04       0
Levee=0,,,-1,356.39,113.27,,Levee 3
#XS Ineff= 2 , 0
          287.22  117.43
Permanent Ineff=
       T       T
#Block Obstruct= 4 ,-1
   31.72  104.85  136.52  127.31  138.77  135.67  159.03  190.31   141.8
  226.87  275.77  118.76
Bank Sta=308.47,334.877
XS Rating Curve= 0 ,0
Exp/Cntr=0.3,0.1

Type RM Length L Ch R = 1 ,7546.696,67.747,67.959,68.171
XS GIS Cut Line= 3
530387.0694944674779751.15219951530419.9000944674780002.85329951
530499.6314944674780168.56959951
#Sta/Elev= 30
       0 115.566   7.552 114.905  25.705 115.443  51.925 115.081  73.504 114.061
  77.137  113.03  80.163 114.157  84.196 114.277 131.417 113.036 206.735 113.162
 214.289 111.343   316.7 111.469 322.209  110.89  323.32  109.46 324.901   107.4
 334.253 106.825 342.964 107.384  350.94 109.479 362.718 109.535 363.931 110.445
  365.68 111.909 368.212 110.831 372.558 113.132 383.586 112.432 385.891 112.089
 387.875  112.85 392.936 113.295 407.922 120.188 420.632 125.102 437.733  126.87
#Mann= 6 ,-1 , 0
       0      .1       0   316.7      .1       0  323.32    .036       0
  350.94      .1       0 363.931      .1       0 383.586     .04       0
Levee=0,,,-1,373.13,113.12,,Levee 3
#XS Ineff= 2 , 0
          303.96  117.55
Permanent Ineff=
       T       T
#Block Obstruct= 2 ,-1
   26.43   42.29  136.55   85.02   99.12  136.41
Bank Sta=323.32,350.94
XS Rating Curve= 0 ,0
Exp/Cntr=0.3,0.1

Type RM Length L Ch R = 1 ,7478.737,68.903,67.717,66.53
XS GIS Cut Line= 3
530312.0281775434779755.84231176530367.3959390114780047.24859474
530434.7171042654780194.12066321
#Sta/Elev= 30
       0 114.859  35.422 114.772  57.773 113.965  71.311 114.274 106.799 113.198
 121.656 113.498 152.853 112.432 156.328  110.47 158.409  110.88 159.604 112.184
 166.729  112.45 205.382  112.45 213.515 111.408 332.681 111.489 343.777 110.787
 349.246 109.906  350.47  109.15 353.801  107.35 361.437 106.663 372.185  107.31
 377.041 109.109 395.003 109.924 399.356 110.174 403.637 112.508 415.025 112.609
 416.957 113.373 423.167 117.883 427.693 118.849 430.104 120.311 458.186 123.846
#Mann= 6 ,-1 , 0
       0      .1       0 343.777      .1       0  350.47    .036       0
 377.041      .1       0 395.003      .1       0 415.025     .04       0
#XS Ineff= 2 , 0
          308.37  118.77
Permanent Ineff=
       T       T
#Block Obstruct= 2 ,-1
   33.92   44.05  119.65  156.39  179.74  137.85
Bank Sta=350.47,377.041
XS Rating Curve= 0 ,0
Exp/Cntr=0.3,0.1

Type RM Length L Ch R = 1 ,7411.020,35.105,34.205,33.306
XS GIS Cut Line= 3
530289.5548944674779741.33239951530300.1075944674780080.77709951
530381.8908944674780218.84139952
#Sta/Elev= 30
       0 134.352   3.253  134.32   6.312 132.576   7.302 129.665   8.357 122.461
   9.314  114.87  36.025 114.589  61.339 111.682  82.349 114.302 152.789 112.326
 181.202 111.988 201.879 112.696 299.287 110.579 342.873 111.276 392.611 110.045
 394.344 109.604  398.12  109.28 401.893 107.291 409.293 106.532 432.417 109.259
 437.054 110.456 437.802 111.703 440.468 111.407 442.894 110.799 444.056 109.635
  446.38  111.14 450.876 112.125 462.922 112.646 468.448 116.859 500.078 121.792
#Mann= 6 ,-1 , 0
       0      .1       0 392.611      .1       0 394.344    .036       0
 432.417      .1       0 440.468      .1       0 462.922     .04       0
#XS Ineff= 2 , 0
          368.46  117.23
Permanent Ineff=
       T       T
#Block Obstruct= 3 ,-1
   43.35   59.74  136.31   87.22     120  136.92  343.61  365.81  120.07
Bank Sta=398.12,432.417
XS Rating Curve= 0 ,0
Exp/Cntr=0.3,0.1

Type RM Length L Ch R = 1 ,7376.814,34.147,31.949,29.75
XS GIS Cut Line= 3
530282.2402555094779742.31347439530259.7400505954780092.78814103
530361.8606125274780237.34189459
#Sta/Elev= 30
       0 134.465   3.459 134.163   5.339 132.953   6.341 130.864   7.343 125.204
   8.345 114.952   9.347  114.74  28.999 114.423  43.417 115.134 125.478 112.701
 153.195 112.972 223.245 111.791 251.147 110.405 329.957 110.658 419.906 109.479
 428.174 108.879  429.62  107.47  438.26  106.35  444.43   106.4 447.222  107.48
 447.585 107.328 447.682 105.918 455.384 106.596  458.25  109.08 463.802 110.913
  472.06 112.202  485.56  112.56 489.589 115.923 491.819 116.818 528.184  122.68
#Mann= 5 ,-1 , 0
       0      .1       0 419.906      .1       0 428.174    .036       0
  458.25      .1       0  485.56     .04       0
#XS Ineff= 1 ,-1
       0  396.48  116.95
Permanent Ineff=
       T
#Block Obstruct= 1 ,-1
   42.82   116.3  136.17
Bank Sta=429.62,447.222
XS Rating Curve= 0 ,0
Exp/Cntr=0.3,0.1

Type RM Length L Ch R = 5 ,7375.883,,,
BEGIN DESCRIPTION:
E40
END DESCRIPTION:
IW Pilot Flow=0
#Inline Weir SE= 12
       0       0  351.43  107.02  429.05  107.02  432.37  107.06  432.41  107.88
  433.22  107.88  433.26  107.09  437.51  107.15  439.16  107.14   440.4  107.17
   442.8  107.18   447.3  107.25
IW Dist,WD,Coef,Skew,MaxSub,Min_El,Is_Ogee,SpillHt,DesHd
0.1,1.75,1.7,0,0.98,, 0 ,,,0,0,