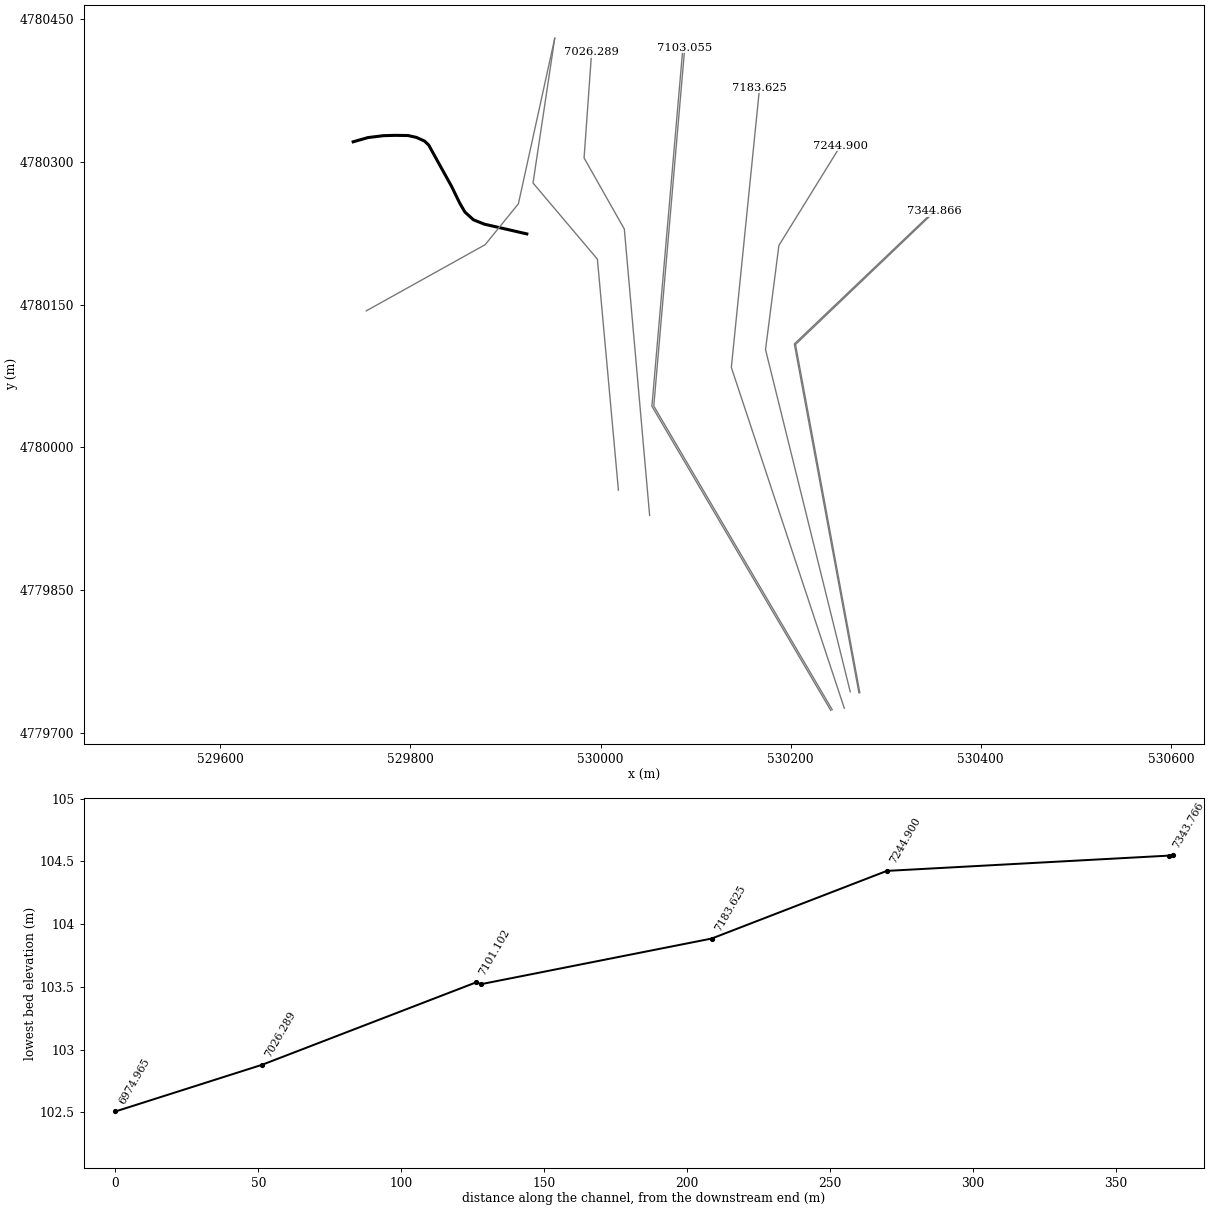
HEC-RAS study Durango.prj: Durango

--- Durango.g18 (geometry) --- (continued)

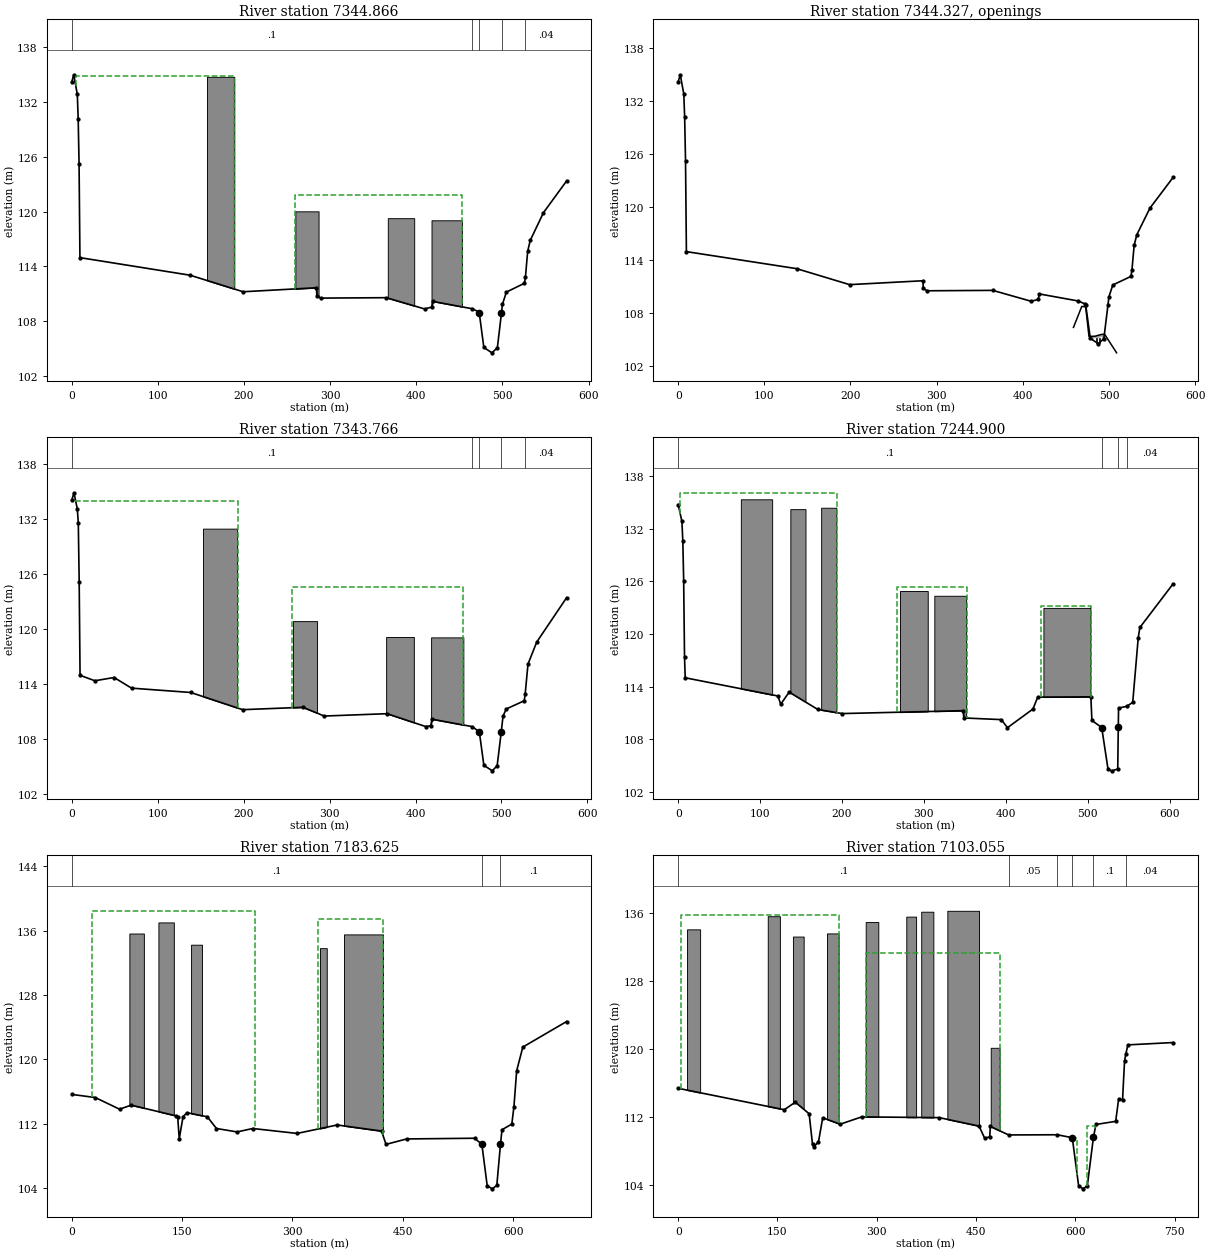
Type RM Length L Ch R = 1 ,7344.866,1.114,1.1,1.086
XS GIS Cut Line= 3
530272.7577618014779742.26675046530205.1073883214780108.10899786
530351.5381697454780247.84713404
#Sta/Elev= 30
       0 134.167   2.414 134.943   6.482 132.791   7.499 130.163   8.516 125.232
   9.533 114.959 137.415 113.037 198.961 111.229  284.11 111.668 284.488 110.805
  288.89 110.535 365.101 110.581  409.67  109.35  417.94 109.556 419.166 110.177
 464.617 109.377 472.486 109.033 473.004 108.941 478.356 105.145 487.813 104.553
 494.083 105.125 498.833 108.914  499.97  109.85 504.449 111.188 525.518 112.159
 526.658 112.845 529.251 115.662 532.293 116.857 547.594 119.879 574.452 123.343
#Mann= 5 ,-1 , 0
       0      .1       0 464.617      .1       0 472.486    .036       0
  499.97      .1       0 526.658     .04       0
#XS Ineff= 2 ,-1
    4.76  188.72  134.77  259.56  452.51  121.84
Permanent Ineff=
       T       T
#Block Obstruct= 4 ,-1
     157  188.72  134.72  259.56  286.52  120.02  366.87  397.53  119.27
  417.62  453.04  119.04
Bank Sta=473.004,498.833
XS Rating Curve= 0 ,0
Exp/Cntr=0.5,0.3

Type RM Length L Ch R = 4 ,7344.327,,,
BEGIN DESCRIPTION:
E41
END DESCRIPTION:
Bridge Culvert--1,0,-1,-1, 0
Deck Dist Width WeirC Skew NumUp NumDn MinLoCord MaxHiCord MaxSubmerge Is_Ogee
0.01,0.9,1.44,0, 18, 18, , , 0.95, 0, ,,,
 458.811 459.169 468.458 472.987 476.804 481.954 482.402 483.705 485.462 485.966
 488.953 489.385 490.974  491.84 492.098 494.888 508.687 508.893
 106.396 106.484 108.768 108.704 105.386 105.394 105.395 105.396 105.444 105.458
 105.539 105.551 105.594 105.603 105.605 105.632 103.553 103.522
 106.396  41.907  41.907  41.907  41.907  41.907 105.153 105.169  105.19 105.146
 105.233 105.246 105.313  105.35  41.819  41.832  41.899 103.522
 460.058 460.416 469.705 474.234 478.051 483.201 483.649 484.952 486.709 487.213
   490.2 490.632 492.221 493.087 493.345 496.135 509.934  510.14
 106.396 106.484 108.768 108.704 105.386 105.394 105.395 105.396 105.444 105.458
 105.539 105.551 105.594 105.603 105.605 105.632 103.553 103.522
 106.396  41.907  41.907  41.907  41.907  41.907 105.153 105.169  105.19 105.146
 105.233 105.246 105.313  105.35  41.819  41.832  41.899 103.522
Pier Skew, UpSta & Num, DnSta & Num=  ,485.71, 2 ,486.96, 2 , 0 , 0 , 0 ,,
     .45     .45
     103   105.3
     .45     .45
     103   105.3
Pier Skew, UpSta & Num, DnSta & Num=  ,489.17, 2 ,490.42, 2 , 0 , 0 , 0 ,,
     .45     .45
     103   105.3
     .45     .45
     103   105.3
BR Coef=-1 , 0 , 0 ,, 0 ,,,0.8,-1,,0,
WSPro=,,,, 1 ,,,, 0 ,,,, 0 ,,,,-1 ,-1 ,-1 , 0 , 0 , 0 , 0 , 0
BC Mult= 1 ,0,473,0,473
BC Mult= 3 ,473,498,473,498
BC Mult= 1 ,498,600,498,600
BC Design=,, 0 ,, 0 ,,,,,,
BC Use User HTab Curves=0
BC User HTab FreeFlow(D)= 0

Type RM Length L Ch R = 1 ,7343.766,95.973,98.866,101.759
XS GIS Cut Line= 3
530271.8038783184779742.11216819 530203.871547394780108.64592843
530350.9434607954780248.64397456
#Sta/Elev= 30
       0 134.021   2.572 134.846   6.489 133.099   7.657 131.542   8.674 125.176
   9.691 114.953  26.981 114.361  49.285 114.717  69.586 113.558 138.452 113.084
 198.859 111.211 269.034 111.471 293.797 110.517 366.852 110.774 411.796 109.374
 417.731 109.455 419.181 110.174 465.959 109.365 474.261 108.797 479.527 105.148
 489.424 104.546 495.023 105.122  499.82  108.83 501.853 110.526 505.678 111.291
 526.537 112.184  527.63 112.937 530.861 116.175 541.029 118.577 575.827 123.418
#Mann= 5 ,-1 , 0
       0      .1       0 465.959      .1       0 474.261    .036       0
  499.82      .1       0  527.63     .04       0
#XS Ineff= 2 ,-1
    4.23  192.95  133.93  256.38  455.69  124.55
Permanent Ineff=
       T       T
#Block Obstruct= 4 ,-1
  152.78  192.42  130.94  257.44  285.46  120.86  365.81  398.06  119.13
  418.15  455.68  119.09
Bank Sta=474.261,499.82
XS Rating Curve= 0 ,0
Exp/Cntr=0.5,0.3

Type RM Length L Ch R = 1 ,7244.900,56.151,61.275,66.399
XS GIS Cut Line= 4
530262.6845944674779743.13999951530173.5729944674780102.71299951
530187.6432944674780212.14819951530252.5995658884780317.09788837
#Sta/Elev= 30
       0 134.759   4.545 132.838   5.668 130.592   6.698 126.068   7.728 117.374
   8.599 115.025 121.765 112.951 125.177 112.012 135.479 113.395 170.508 111.416
 200.385 110.949 347.711 111.279 348.842 110.448 394.435  110.26  402.04 109.342
 433.099 111.464 438.938 112.823 503.831 112.855 505.087 110.162 517.062 109.361
 524.819 104.581 529.204 104.424 536.637 104.625   537.3  109.38 537.648 111.569
 547.658 111.778 554.931 112.224 561.667 119.606 563.687 120.759 604.212 125.728
#Mann= 4 ,-1 , 0
       0      .1       0 517.062    .036       0   537.3      .1       0
 547.658     .04       0
#XS Ineff= 3 ,-1
    2.47  193.66136.1034  267.67  352.78  125.33  442.82  503.88   123.2
Permanent Ineff=
       T       F       T
#Block Obstruct= 6 ,-1
   76.48  114.71  135.36  136.92  155.42  134.24  174.54  193.04   134.4
  270.75  304.67  124.91  312.69  351.54  124.37   445.9  503.26  122.99
Bank Sta=517.062,537.3
XS Rating Curve= 0 ,0
Exp/Cntr=0.3,0.1

Type RM Length L Ch R = 1 ,7183.625,80.408,80.571,80.733
XS GIS Cut Line= 3
530256.4311587414779725.94303627530137.6157371894780083.95266174
530167.319592577  4780377.864494
#Sta/Elev= 30
       0 115.626  31.927  115.24  65.007 113.785  80.811 114.293 142.233 112.949
  144.03 112.785 146.137 110.118  151.31 112.857 156.673 113.351  184.27 112.845
 196.712 111.387 224.829 110.961 245.988 111.387  306.29 110.774 360.845 111.825
 421.123 111.067 427.153 109.413  455.19 110.089 547.535 110.176 557.401  109.43
 564.663 104.282 571.494 103.885 577.744 104.313  582.71  109.42 584.812 111.234
 598.138  111.94 601.034 114.115 604.694 118.556 613.095 121.509  672.62  124.69
#Mann= 3 ,-1 , 0
       0      .1       0 557.401    .036       0  582.71      .1       0
#XS Ineff= 2 ,-1
   27.75  249.16138.4566  334.89  423.08  137.39
Permanent Ineff=
       T       T
#Block Obstruct= 5 ,-1
   78.33   98.06  135.63   117.8  138.77  137.01   162.2     177  134.24
  337.36  346.61  133.81  370.04  423.08  135.52
Bank Sta=557.401,582.71
XS Rating Curve= 0 ,0
Exp/Cntr=0.5,0.3

Type RM Length L Ch R = 1 ,7103.055,1.956,1.953,1.95
XS GIS Cut Line= 3
530243.6922635844779724.41284076530056.0275436314780043.41714922
530088.5975392294780419.71572118
#Sta/Elev= 30
       0  115.38 160.373 112.854 176.885 113.744 197.849 112.383  202.98 108.764
 204.953 108.489 211.948 109.046 218.383 111.902 244.801 111.146 277.221 112.007
 394.425 111.922 454.649 110.921 463.026 109.505 470.709 109.649 471.713 110.879
 499.392 109.879 572.902 109.901 595.486 109.551 605.064 103.882 612.099 103.522
 618.258 103.908  627.42  109.58 631.235 111.115 661.072 111.483 665.434  114.06
 671.457 114.023 674.468 118.612 676.325 119.387 679.487 120.504 747.816 120.778
#Mann= 6 ,-1 , 0
       0      .1       0 499.392     .05       0 572.902      .1       0
 595.486    .036       0  627.42      .1       0 676.325     .04       0
#XS Ineff= 4 ,-1
    3.52  243.17  135.84  283.35  486.34  131.36  595.95  602.83  109.55
  618.04   629.8  110.97
Permanent Ineff=
       T       F       T       T
#Block Obstruct= 9 ,-1
   13.39   33.13  134.13  135.33  153.66  135.68  173.39   189.6  133.28
  224.85  242.47  133.65  283.35  302.38  134.99  344.67  359.47  135.63
  367.22  385.55  136.21   406.7  454.63  136.32  472.25  485.64  120.16
Bank Sta=595.486,627.42
XS Rating Curve= 0 ,0
Exp/Cntr=0.5,0.3

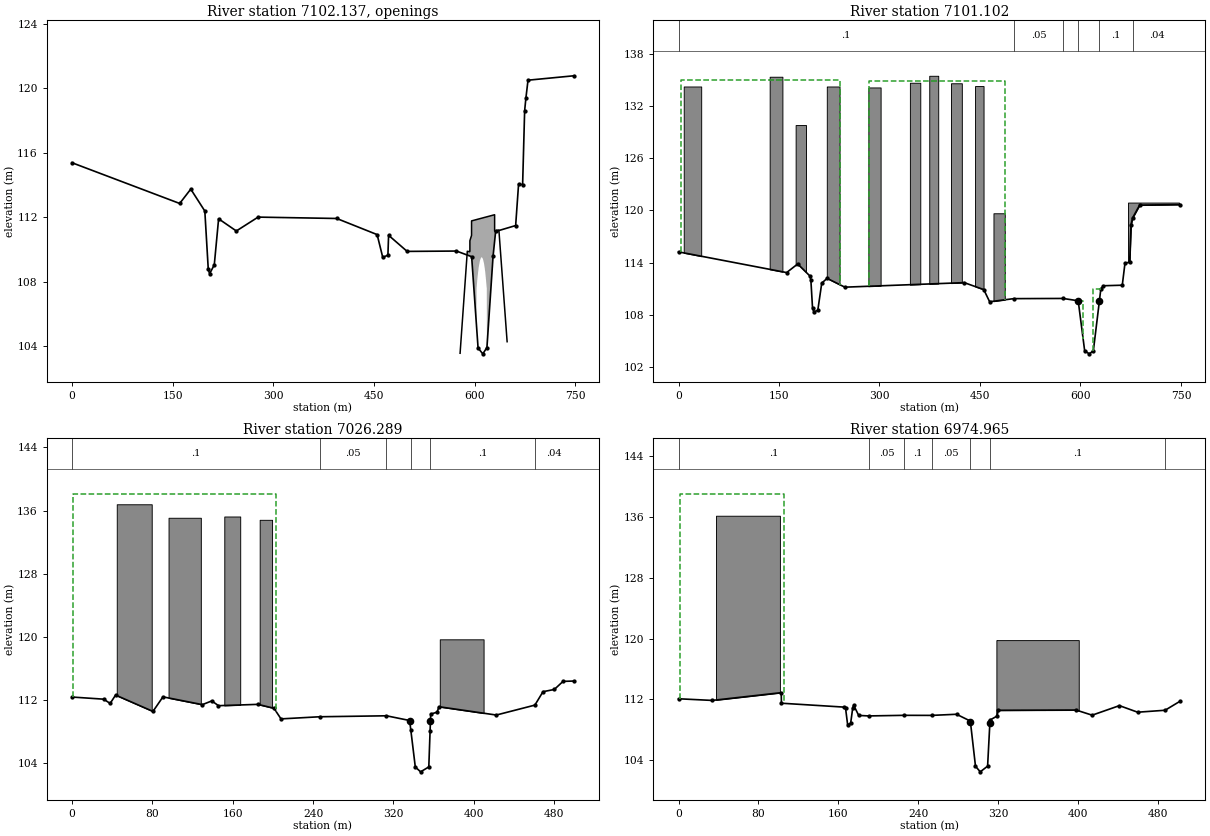
Type RM Length L Ch R = 4 ,7102.137,,,
BEGIN DESCRIPTION:
E42
END DESCRIPTION:
Bridge Culvert--1,0,-1,-1, 0
Deck Dist Width WeirC Skew NumUp NumDn MinLoCord MaxHiCord MaxSubmerge Is_Ogee
0.01,1.75,1.44,0, 26, 26, , , 0.95, 0, ,,,
 578.266 578.756 589.018 592.522 592.858 592.868 595.336 595.352 602.537 602.832
 604.358 606.055 607.874 609.476  610.68   612.3 613.986 615.775 618.037 618.413
  629.73 629.742 629.884 636.081 648.099 648.356
 103.558 103.847 109.888 109.858 109.894 110.541 110.873 111.773 111.853 111.856
 111.873 111.892 111.912  111.93 111.943 111.961  111.98     112 112.025 112.029
 112.155  111.14 111.147 111.205  104.42 104.275
 103.558   12.06   11.87  11.805  11.799  11.799  11.753  11.753   11.62 107.588
 108.316 108.907 109.314 109.493  109.52 109.412  109.12 108.599 107.588  11.188
  11.298  11.299    11.3   11.36  11.478 104.275
 579.418 579.908  590.17 593.674  594.01  594.02 596.488 596.504 603.689 603.984
  605.51 607.207 609.026 610.628 611.832 613.452 615.138 616.927 619.189 619.565
 630.882 630.894 631.036 637.233 649.251 649.508
 103.558 103.847 109.888 109.858 109.894 110.541 110.873 111.773 111.853 111.856
 111.873 111.892 111.912  111.93 111.943 111.961  111.98     112 112.025 112.029
 112.155  111.14 111.147 111.205  104.42 104.275
 103.558   12.06   11.87  11.805  11.799  11.799  11.753  11.753   11.62 107.588
 108.316 108.907 109.314 109.493  109.52 109.412  109.12 108.599 107.588  11.188
  11.298  11.299    11.3   11.36  11.478 104.275
BR Coef=-1 , 0 , 0 ,, 0 ,,,0.8,0,,0,
WSPro=,,,, 1 ,,,, 0 ,,,, 0 ,,,,-1 ,-1 ,-1 , 0 , 0 , 0 , 0 , 0
BC Mult= 1 ,0,589,0,589
BC Mult= 3 ,589,635,589,635
BC Mult= 1 ,635,800,635,800
BC Design=,, 0 ,, 0 ,,,,,,
BC Use User HTab Curves=0
BC User HTab FreeFlow(D)= 0

Type RM Length L Ch R = 1 ,7101.102,68.004,74.813,81.622
XS GIS Cut Line= 3
530242.2205175754779723.57329559530054.058757188 4780043.2312077
530086.6620258274780419.97178793
#Sta/Elev= 30
       0 115.247 161.373 112.868 177.872 113.858  196.38 112.456 197.594 111.968
 199.989 108.846 201.961 108.362 207.875 108.524 213.788 111.655 221.768 112.205
 248.251 111.192 426.467 111.713 455.652 110.914 464.415 109.518 500.457 109.875
 574.017 109.896 596.633 109.629 606.289 103.875 613.201 103.535 619.261 103.893
  628.17  109.55   630.4  110.99 634.317 111.356 662.422 111.417 666.437 113.937
 673.463  114.08  675.47 118.334 677.689 119.126 688.301 120.615 749.075 120.681
#Mann= 6 ,-1 , 0
       0      .1       0 500.457     .05       0 574.017      .1       0
 596.633    .036       0  628.17      .1       0 677.689     .04       0
#XS Ineff= 4 ,-1
    4.23  240.35  134.93  284.05  487.05  134.88   596.6  603.98  109.63
   619.2   630.4     111
Permanent Ineff=
       T       F       T       T
#Block Obstruct= 11 ,-1
    7.75   33.83  134.24  136.04  155.07  135.36   174.8  190.31  129.81
  221.32  240.35  134.24  283.35  301.67  134.13  345.37  360.88  134.67
  374.27  387.67  135.47   406.7  422.91  134.61  442.64  455.33  134.29
  470.13  487.05  119.68  671.01  747.14  120.91
Bank Sta=596.633,628.17
XS Rating Curve= 0 ,0
Exp/Cntr=0.5,0.3

Type RM Length L Ch R = 1 ,7026.289,49.213,51.323,53.434
XS GIS Cut Line= 4
 530051.660954064779928.43693039530025.0537588764780229.34521706
529982.7180343674780304.05393018529990.6598210594780415.38515343
#Sta/Elev= 30
       0 112.361  31.446 112.092  37.902 111.551  43.323  112.61  80.517 110.537
  90.477 112.384 129.708 111.399 139.108 111.869 145.771 111.266 184.923 111.433
 200.985 110.941 208.013 109.592 246.586 109.862 313.029 109.984  336.05 109.387
 337.277 108.142  341.71 103.495 346.977 102.879 355.153 103.504 356.445  108.11
  356.77  109.29 357.037   110.2 363.505 110.446 365.168 111.134  422.36  110.08
  460.75 111.338 468.844 113.039 480.104 113.323 488.795 114.349 499.567 114.389
#Mann= 6 ,-1 , 0
       0      .1       0 246.586     .05       0 313.029      .1       0
 337.277    .036       0 356.445      .1       0  460.75     .04       0
#XS Ineff= 1 ,-1
    1.32  203.52  138.13
Permanent Ineff=
       T
#Block Obstruct= 5 ,-1
   44.49    79.3   136.8   96.04  128.19  135.09  151.54   167.4  135.25
  186.78  199.12  134.83  366.08  409.69  119.68
Bank Sta=336.05,356.77
XS Rating Curve= 0 ,0
Exp/Cntr=0.3,0.1

Type RM Length L Ch R = 1 ,6974.965,2.923,71.69,3.02
XS GIS Cut Line= 4
530018.8303944674779955.01409951529996.7177944674780197.73599951
529929.0047944674780277.76049951529951.8688944674780429.89509951
#Sta/Elev= 30
       0 112.094  33.721 111.877 102.785 112.895 103.052  111.51 165.472 111.002
 167.206 110.877 169.325 108.664 172.338 108.895 174.346 110.836  175.35 111.249
 180.371  109.91 190.409 109.843 225.828 109.922  253.46 109.913 278.327 110.061
  292.03 109.178 292.289 109.009 297.306 103.245 302.064 102.507 309.441 103.252
 311.721  108.95 311.855 109.305 318.835 109.818  319.58 110.582 397.985 110.617
  414.12 109.942  441.42 111.194  459.67 110.331 487.126 110.587 502.399 111.792
#Mann= 7 ,-1 , 0
       0      .1       0 190.409     .05       0 225.828      .1       0
  253.46     .05       0  292.03    .036       0 311.855      .1       0
 487.126     .04       0
#XS Ineff= 2 ,-1
    1.06   105.2  138.99  164.41  177.09  110.77
Permanent Ineff=
       T       T
#Block Obstruct= 2 ,-1
   37.53   101.5  136.11  318.24   400.7  119.79
Bank Sta=292.289,311.721
XS Rating Curve= 0 ,0
Exp/Cntr=0.5,0.3

River Reach=IBAIZABAL       ,IBAIZABAL-102
Reach XY= 30
529922.4819193484780224.27112185 529915.154888314780225.95063119
529911.7710000024780226.72628941529899.0573147394780229.64053299
529897.7710000024780229.93538332529890.0266421814780231.71055273
529885.904956065 4780232.6553297529879.7710000054780234.06136122
529877.8637221944780234.49854932529874.5424093984780235.81227518
529871.1873889754780237.13933386529866.3788686994780239.04131593
529866.0985311314780239.29606225529857.3870811164780247.21226843
529851.9621552684780256.49739845529843.4120884984780274.05137458
529826.1685420274780305.13017852529819.215716969 4780317.7073636
529814.8834985234780321.78780571529806.4691899834780325.61844567
529797.5549624534780327.61706704529783.9222921994780327.81809248
529771.8792089714780327.49094145529767.4244130484780326.94782608
 529763.47143605  4780326.465891529762.7710000054780326.38049592
529755.4490861824780325.48783016529744.2635782994780322.31261447
529739.9315603824780321.08289015529739.8320934474780321.04955443

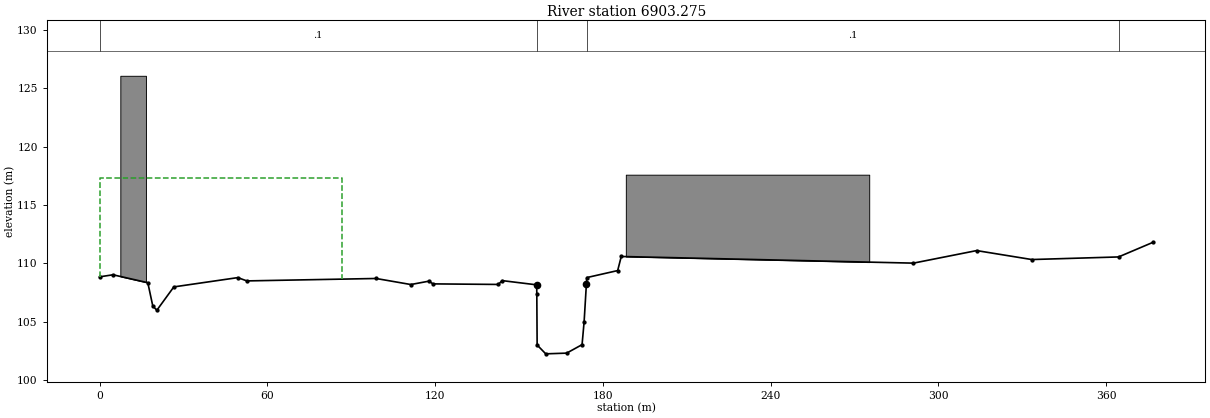
Type RM Length L Ch R = 1 ,6903.275,4.316,4.316,4.316
XS GIS Cut Line= 4
529753.5801596394780143.39904175529878.6217337434780212.90176926
529913.6126010774780255.89578946529951.8688944674780429.89509951
#Sta/Elev= 30
       0 108.842   4.795 109.017  17.231 108.338  19.023 106.326  20.475 105.981
  26.533 107.978  49.415 108.775  52.654 108.492  98.857   108.7 111.294 108.182
 117.824 108.473 119.205 108.237 142.524 108.189 144.013 108.516 156.307 108.155
 156.353 107.412 156.472 102.996 159.548 102.239 167.027   102.3 172.542 103.027
 173.275 104.987  174.08  108.19 174.252 108.779 185.272 109.378 186.561 110.586
 291.041 110.016  313.66 111.092 333.386 110.324 364.408 110.547 376.649 111.792
#Mann= 4 ,-1 , 0
       0      .1       0 156.307    .036       0 174.252      .1       0
 364.408     .04       0
#XS Ineff= 2 , 0
            86.7  117.28
Permanent Ineff=
       T       T
#Block Obstruct= 2 ,-1
     7.4   16.56  126.08  188.19  275.24   117.6
Bank Sta=156.307,174.08
XS Rating Curve= 0 ,0
Exp/Cntr=0.5,0.3