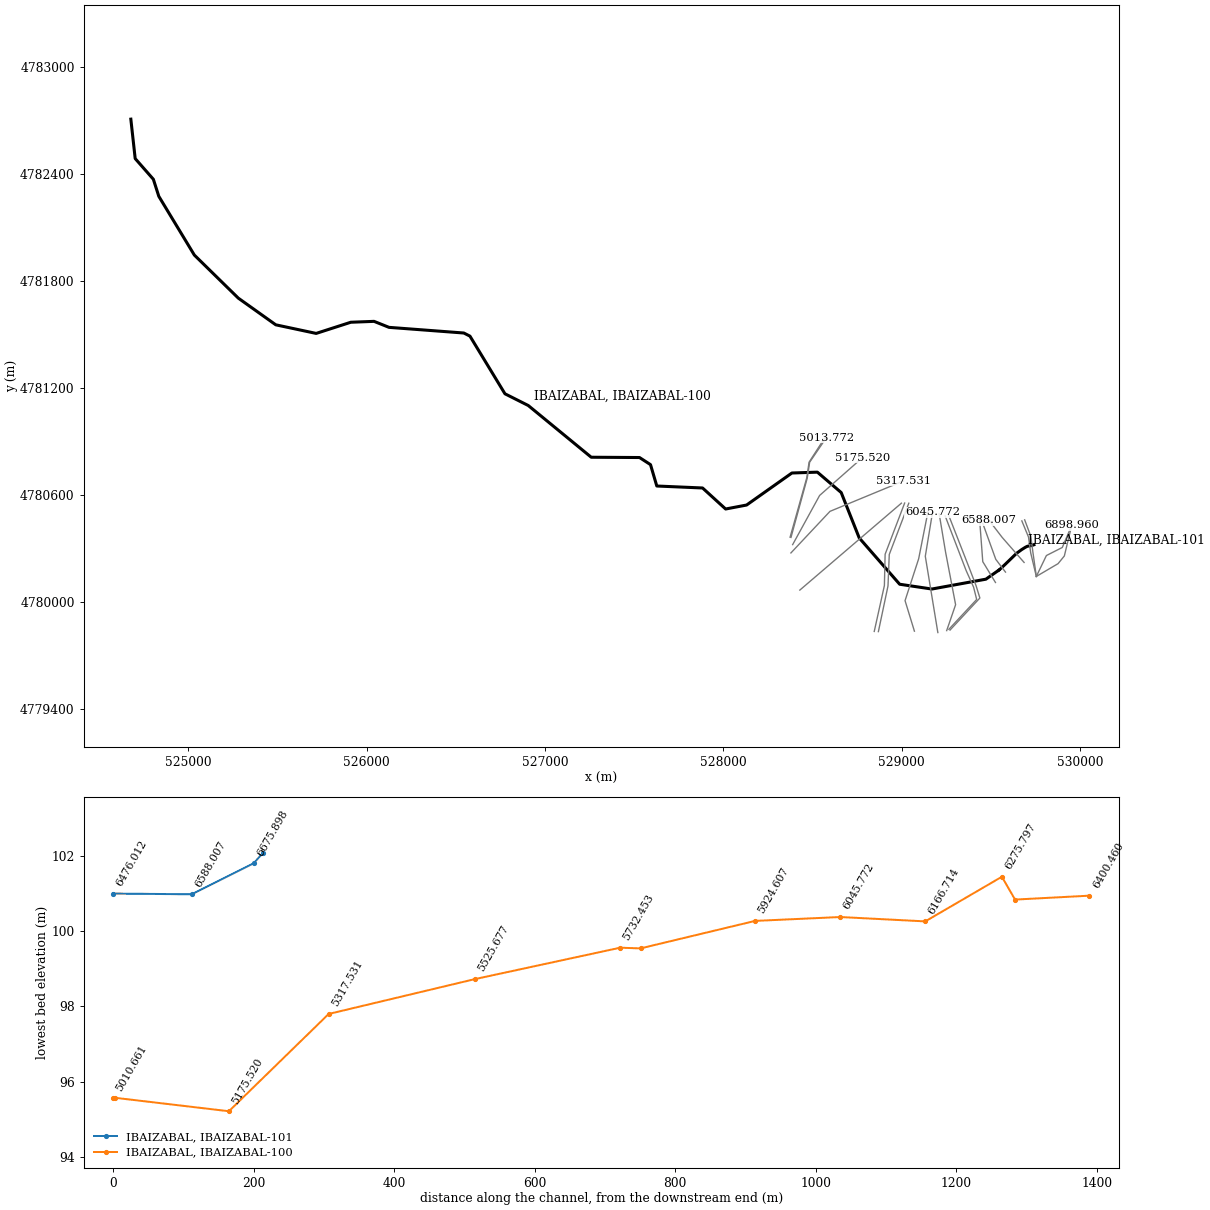
HEC-RAS study Durango.prj: Durango

--- Durango.g18 (geometry) --- (continued)

Type RM Length L Ch R = 4 ,6901.034,,,
BEGIN DESCRIPTION:
E43
END DESCRIPTION:
Bridge Culvert--1,0,-1,-1, 0
Deck Dist Width WeirC Skew NumUp NumDn MinLoCord MaxHiCord MaxSubmerge Is_Ogee
0.01,4.12,1.44,0, 21, 21, , , 0.95, 0, ,,,
 137.315 137.594 151.699 152.664 156.201 156.327 156.328 156.331 157.854 158.813
 165.301 168.559 171.805 172.689  174.47 174.472 174.667 177.494 181.076  197.96
 198.053
 106.994 107.024 108.494 108.485 108.254 108.246 108.246 108.749 108.747 109.162
 110.382 110.046 109.096  108.69 108.681 108.599 108.617 108.887 109.016 106.977
 106.965
 106.994   23.74  23.891  23.901  23.939 107.399 107.399 107.399 107.394 107.391
  107.37  107.36 107.349 107.347 107.341 106.363  24.099  24.087  24.072  23.999
 106.965
 132.538 132.817 146.922 147.887 151.424  151.55 151.551 151.554 153.077 154.036
 160.524 163.782 167.028 167.912 169.693 169.695  169.89 172.717 176.299 193.183
 193.276
 106.994 107.024 108.494 108.485 108.254 108.246 108.246 108.749 108.747 109.162
 110.382 110.046 109.096  108.69 108.681 108.599 108.617 108.887 109.016 106.977
 106.965
 106.994   23.74  23.891  23.901  23.939 107.399 107.399 107.399 107.394 107.391
  107.37  107.36 107.349 107.347 107.341 106.363  24.099  24.087  24.072  23.999
 106.965
BR Coef=-1 , 0 , 0 ,, 0 ,,,0.8,0,,0,
WSPro=,,,, 1 ,,,, 0 ,,,, 0 ,,,,-1 ,-1 ,-1 , 0 , 0 , 0 , 0 , 0
BC Mult= 1 ,0,156,0,148
BC Mult= 3 ,156,174,148,172
BC Mult= 1 ,174,400,172,400
BC Design=,, 0 ,, 0 ,,,,,,
BC Use User HTab Curves=0
BC User HTab FreeFlow(D)= 0

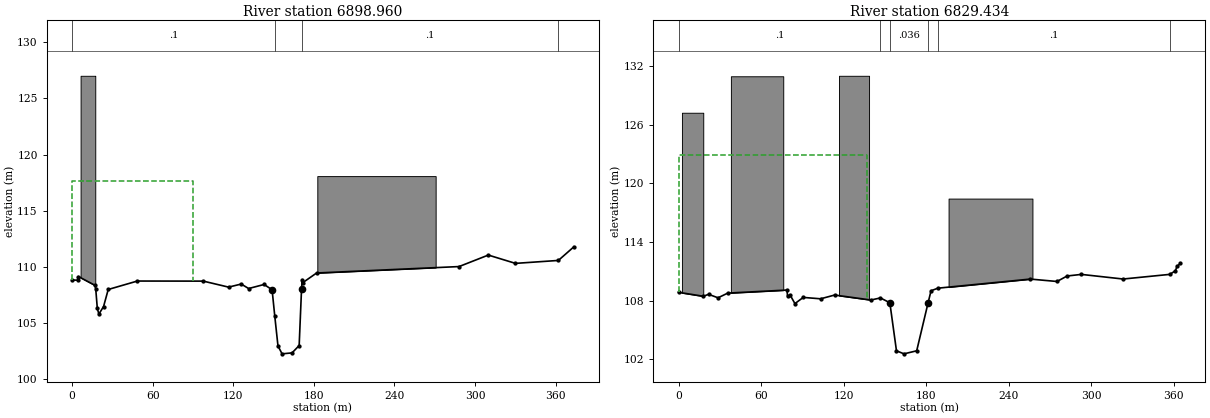
Type RM Length L Ch R = 1 ,6898.960,73.918,69.526,65.134
XS GIS Cut Line= 4
529753.5801944674780143.39899951529875.556333465 4780215.2681443
529910.547200799 4780258.2621645529951.8689309634780429.89509595
#Sta/Elev= 30
       0 108.842   4.416 108.824   4.698 109.154  17.114 108.363  17.632 108.031
  18.793 106.316  19.953 105.811  23.435 106.481  26.917     108  48.613 108.751
  97.718 108.743 116.512 108.209 125.936 108.483 131.446 108.084 142.931 108.445
   148.9 107.976 150.912 105.615 153.279 102.982  156.33 102.278 163.744 102.362
 169.051 103.015  170.82  108.03 171.286 108.881 171.657   108.6 182.025 109.464
 288.047 110.037 309.863 111.059 330.084 110.321 362.003 110.582 373.545 111.792
#Mann= 4 ,-1 , 0
       0      .1       0 150.912    .036       0 171.286      .1       0
 362.003     .04       0
#XS Ineff= 2 , 0
           90.22  117.64
Permanent Ineff=
       T       T
#Block Obstruct= 2 ,-1
    6.34   17.27     127  182.56  270.66  118.08
Bank Sta=148.9,170.82
XS Rating Curve= 0 ,0
Exp/Cntr=0.5,0.3

Type RM Length L Ch R = 1 ,6829.434,2.837,140.584,2.906
XS GIS Cut Line= 4
529753.5801596394780143.39904175529809.9892876514780260.66592653
529899.0181985664780305.90390722529951.8689309634780429.89509595
#Sta/Elev= 30
       0 108.842  18.023 108.439  21.822 108.637  28.731 108.282  35.779 108.762
  78.874 109.074  79.225  108.45  81.245 108.532  84.604 107.687   90.65 108.322
 103.286 108.179 113.456 108.564 139.852 108.055  146.75 108.268 153.613 107.776
 158.427  102.86 163.897  102.55  173.13  102.86  181.43  107.78 183.563     109
  188.48 109.265 255.796 110.196 275.108 109.951 282.475 110.512 292.819 110.675
 323.193 110.202 357.044 110.676  361.24 111.047 362.327 111.486 364.777 111.792
#Mann= 6 ,-1 , 0
       0      .1       0  146.75      .1       0 153.613    .036       0
  181.43      .1       0  188.48      .1       0 357.044     .04       0
#XS Ineff= 2 , 0
          136.74  122.87
Permanent Ineff=
       T       T
#Block Obstruct= 4 ,-1
    2.47   17.97  127.21   38.06   76.12  130.94  116.65   138.5  130.99
   196.3  257.27  118.43
Bank Sta=153.613,181.43
XS Rating Curve= 0 ,0
Exp/Cntr=0.5,0.3

River Reach=IBAIZABAL       ,IBAIZABAL-101
Reach XY= 30
529739.8320934474780321.04955443 529737.203220174780320.16850463
529732.0843943734780318.45296337529731.8965035164780318.38999299
529730.4925372154780317.91946278 529728.627155014780317.29429206
529727.7710000024780317.09292439529718.5211593474780314.91736189
529717.7710000054780314.82874044529708.072391044 4780313.6829773
 529702.906599064780312.43376241 529700.331367534780311.14668659
529694.2864864734780308.12551354529693.5440740474780307.75446297
529692.0749835454780307.02022576529671.3721913214780294.00847198
529666.7572591164780290.64787044529666.7543550474780290.64575571
  529649.66018864780278.19775439529645.221390605 4780274.9654141
529644.5482020044780274.47519699529643.172302868 4780273.4732649
529639.8895407214780270.28537783529637.1474393944780267.62252598
 529581.363584914780213.45088044529565.403775465 4780198.3183934
529550.2196790764780184.29219252529545.0037780484780180.24433174
529544.7710000024780180.06368164529543.3300327784780178.63578216

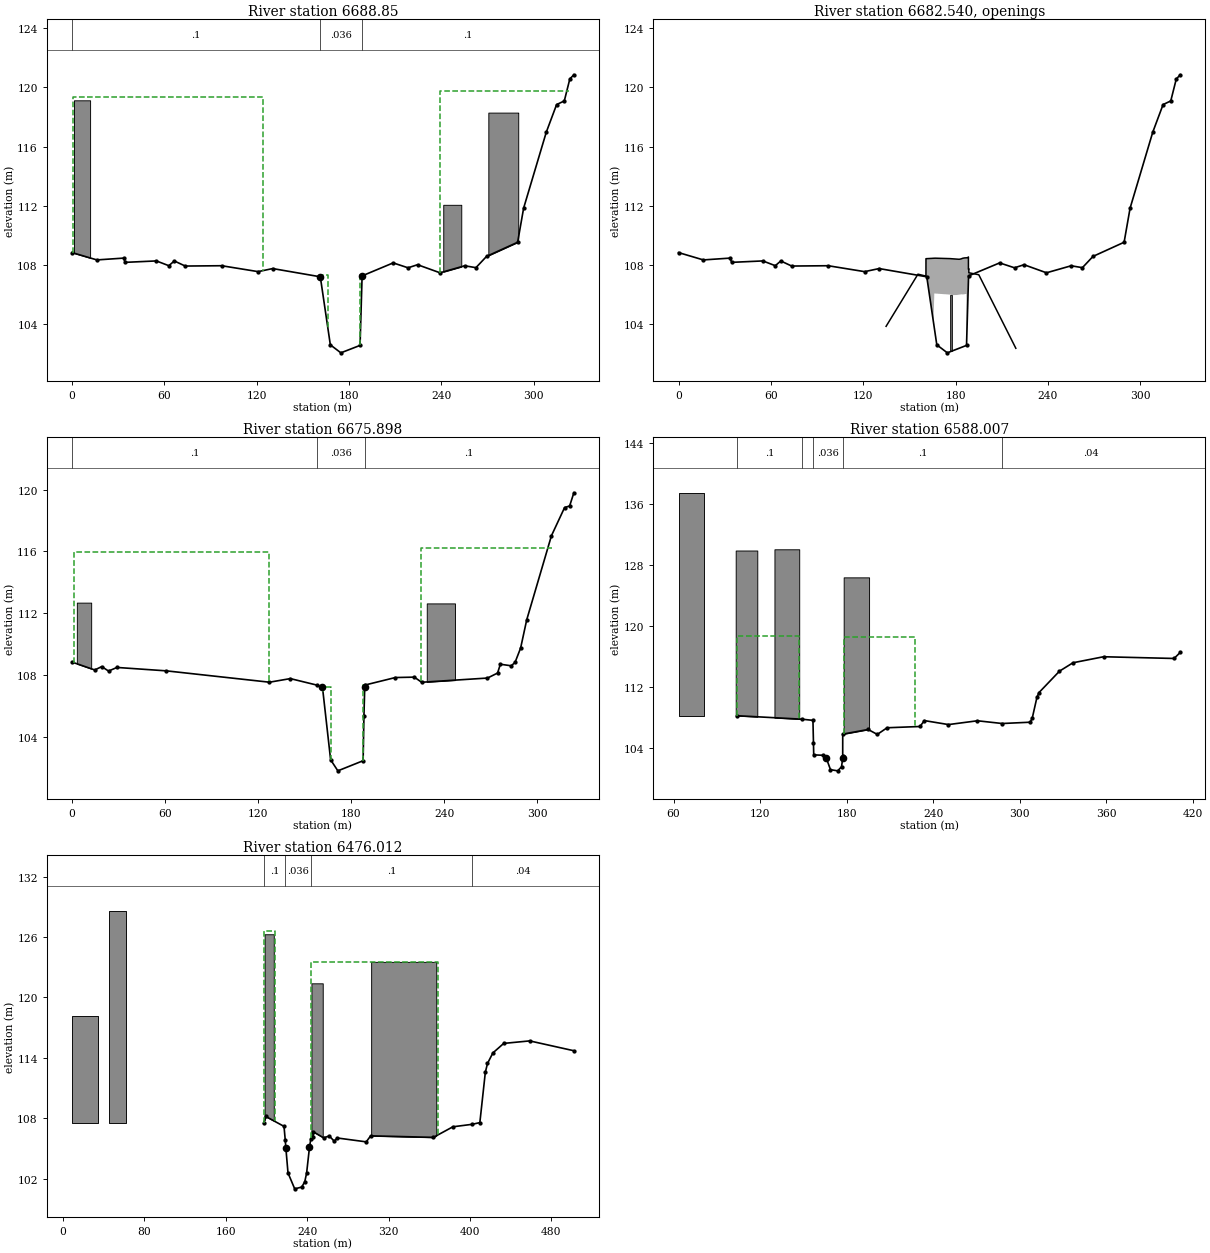
Type RM Length L Ch R = 1 ,6688.85 ,12.892,12.952,13.024
XS GIS Cut Line= 4
529753.5801596394780143.39904175529734.720327219 4780277.2826349
 529722.320670314780369.81203209 529688.240634544780461.10191425
#Sta/Elev= 30
       0 108.842   16.12 108.346  33.422 108.468  34.567 108.182  54.778 108.278
  62.857 107.956  66.434 108.275  73.516 107.932  97.192 107.954 120.897 107.554
 130.331 107.762 161.281 107.206 167.792 102.609 174.638 102.068 187.101 102.571
  188.43 107.267 208.613 108.145 218.283 107.814 224.451 108.022 239.054 107.476
 255.065  107.95 262.387 107.823 269.273 108.583 289.482  109.54 293.368 111.845
 308.097 116.978 314.794 118.841 319.795 119.088 323.379 120.572 326.006 120.855
#Mann= 3 ,-1 , 0
       0      .1       0 161.281    .036       0  188.43      .1       0
#XS Ineff= 4 ,-1
     .62  123.96  119.33  161.28  166.18   107.3  187.01   188.4   107.3
   239.3  322.86  119.77
Permanent Ineff=
       T       T       T       T
#Block Obstruct= 3 ,-1
    1.23   11.72  119.13  241.15  252.86  112.07  270.44  289.87   118.3
Bank Sta=161.281,188.43
XS Rating Curve= 0 ,0
Exp/Cntr=0.5,0.3

Type RM Length L Ch R = 4 ,6682.540,,,
BEGIN DESCRIPTION:
E44
END DESCRIPTION:
Bridge Culvert--1,0,-1,-1, 0
Deck Dist Width WeirC Skew NumUp NumDn MinLoCord MaxHiCord MaxSubmerge Is_Ogee
0.01,12.75,1.44,0, 31, 31, , , 0.95, 0, ,,,
 134.846 135.396 155.558  160.74 160.749 165.624 166.179  166.74 174.043  176.34
 176.462 177.607 180.849 182.339 183.539 184.383 184.389 184.738 185.937 187.007
 187.128 187.137 187.922 188.335 188.341 188.594 188.605 191.835 195.077 219.014
 219.134
 103.859 103.953 107.384 107.253  108.43 108.458 108.461 108.464 108.442 108.435
 108.434 108.425   108.4 108.389 108.415 108.447 108.448 108.461 108.483 108.488
 108.488 108.488 108.507 108.545 107.713 107.747 107.479 107.411 107.344 102.401
 102.376
 103.859   1.235   1.005    .946    .946     .89  106.08 106.076  106.02 106.003
 106.002 105.965 105.977     106 106.019 106.032 106.004 106.011 106.032 106.052
   1.394   1.394   1.382   1.376   1.376   1.372   1.372   1.323   1.274    .913
 102.376
 135.581 136.131 156.293 161.475 161.484 166.359 166.914 167.475 174.778 177.075
 177.197 178.342 181.584 183.074 184.274 185.118 185.124 185.473 186.672 187.742
 187.863 187.872 188.657  189.07 189.076 189.329  189.34  192.57 195.812 219.749
 219.869
 103.859 103.953 107.384 107.253  108.43 108.458 108.461 108.464 108.442 108.435
 108.434 108.425   108.4 108.389 108.415 108.447 108.448 108.461 108.483 108.488
 108.488 108.488 108.507 108.545 107.713 107.747 107.479 107.411 107.344 102.401
 102.376
 103.859   1.235   1.005    .946    .946     .89  106.08 106.076  106.02 106.003
 106.002 105.965 105.977     106 106.019 106.032 106.004 106.011 106.032 106.052
   1.394   1.394   1.382   1.376   1.376   1.372   1.372   1.323   1.274    .913
 102.376
Pier Skew, UpSta & Num, DnSta & Num=  ,177.035, 2 ,177.765, 2 , 0 , 0 , 0 ,,
   1.145   1.145
     101     108
   1.145   1.145
     101     108
BR Coef=-1 , 1 , 0 ,, 0 ,,,0.8,0,1.39,0,
WSPro=,,,, 1 ,,,, 0 ,,,, 0 ,,,,-1 ,-1 ,-1 , 0 , 0 , 0 , 0 , 0
BC Mult= 1 ,0,161,0,159
BC Mult= 3 ,161,188,159,191
BC Mult= 1 ,188,350,191,350
BC Design=,, 0 ,, 0 ,,,,,,
BC Use User HTab Curves=0
BC User HTab FreeFlow(D)= 0

Type RM Length L Ch R = 1 ,6675.898,81.325,87.891,94.457
XS GIS Cut Line= 4
529753.5801596394780143.39904175529722.221959279 4780274.8000968
 529709.866534874780364.11424001 529672.411606344780455.16602867
#Sta/Elev= 30
       0 108.842  14.642 108.333  19.133  108.55   23.54 108.262  28.942 108.495
  60.906 108.274 127.348  107.54 140.819 107.773 157.841 107.355 161.555   107.2
 166.792 102.521 171.462 101.804  187.76 102.459 188.289 105.359   188.8   107.2
 188.802 107.353 208.548 107.842   220.8 107.868 225.507 107.536 267.996 107.809
 274.484 108.132 276.298 108.703 283.337 108.602 285.805  108.83 289.368 109.752
 293.302 111.579 309.243 117.018 317.737 118.845  320.98 118.945  323.71 119.799
#Mann= 3 ,-1 , 0
       0      .1       0 157.841    .036       0 188.802      .1       0
#XS Ineff= 4 ,-1
    1.54  126.74  115.97  161.85  166.91   107.2  187.74   188.8  107.35
   224.8   309.3  116.24
Permanent Ineff=
       T       T       T       T
#Block Obstruct= 2 ,-1
    3.08   12.33  112.69  228.81     247  112.64
Bank Sta=161.555,188.8
XS Rating Curve= 0 ,0
Exp/Cntr=0.5,0.3

Type RM Length L Ch R = 1 ,6588.007,112.76,111.994,111.228
XS GIS Cut Line= 3
529685.0109435714780221.88110906529562.2602542334780362.37751118
529488.8510944674780458.15569951
#Sta/Elev= 30
 104.217 108.207 148.948 107.753 156.662   107.6 157.016 104.676 157.198 103.073
 163.654  103.02 165.989  102.61 168.832 101.132 173.832  100.98 176.489 101.516
  177.28  102.61 177.301 102.912 177.316 105.792 194.932 106.401 201.311 105.756
 208.077 106.629 230.889 106.794 233.954 107.568 250.672 107.046 270.764 107.545
 287.943 107.186 307.312 107.356 308.755 107.887 312.005  110.61 313.432 111.242
 327.654 114.052 337.021 115.152 358.234  115.94 407.124 115.714 411.459 116.519
#Mann= 5 ,-1 , 0
 104.217      .1       0 148.948      .1       0 157.016    .036       0
 177.316      .1       0 287.943     .04       0
#XS Ineff= 2 ,-1
       0  146.69118.6233  177.98  227.31118.4967
Permanent Ineff=
       T       T
#Block Obstruct= 4 ,-1
   63.44   81.06  137.44  103.08  118.06  129.87  129.96  147.14  130.03
  177.97  195.59  126.35
Bank Sta=165.989,177.28
XS Rating Curve= 0 ,0
Exp/Cntr=0.3,0.1

Type RM Length L Ch R = 1 ,6476.012,76.73,75.552,74.374
XS GIS Cut Line= 3
529580.7708754214780167.78914113529526.3717219344780239.28517142
529453.4148841394780441.47983617
#Sta/Elev= 30
 197.332 107.507 199.368 108.185  217.28   107.2 218.508 105.827  219.12  105.02
 221.204  102.58 227.782 101.001 234.676 101.176  237.69 101.711 239.505  102.58
 242.323 105.137 243.573 105.928 245.751 106.173 246.152 106.659 256.204 106.064
 261.739 106.249 266.694 105.724  269.51  106.05 298.103 105.664 302.433 106.263
 364.093  106.11 383.228 107.159 402.152 107.405 409.741 107.575 415.122 112.568
 417.248 113.444 422.544 114.491 433.195 115.436 458.709 115.685 502.126 114.708
#Mann= 4 ,-1 , 0
 197.332      .1       0 218.508    .036       0 243.573      .1       0
 402.152     .04       0
#XS Ineff= 2 ,-1
  185.55  208.28  126.64  244.23  368.99  123.48
Permanent Ineff=
       T       T
#Block Obstruct= 5 ,-1
    8.99   34.36   118.2   45.46   62.38   128.6  198.24  207.22  126.27
  244.23  255.33   121.4  302.91  366.87  123.53
Bank Sta=219.12,242.323
XS Rating Curve= 0 ,0
Exp/Cntr=0.3,0.1

River Reach=IBAIZABAL       ,IBAIZABAL-100
Reach XY= 30
529543.3300327784780178.63578216529471.0989726934780128.03180685
529168.1153105724780072.71253315528987.721441843  4780099.609804
528761.0551799874780359.76576167528660.1286176334780614.25253003
528526.6138890054780728.73525516528383.9332285414780723.97649677
528129.9733713574780544.17465619528012.4262194454780521.90811329
527883.247086339 4780639.8714016527626.7580285744780650.95792402
527591.5434021094780770.85868558527529.8448892164780810.82364157
 527259.343353354780812.44572662526906.3708321564781102.83616401
526775.8378315314781168.59872153526579.7689529554781492.12697734
 526545.385198374781509.70099665526126.1114425034781541.45070566
526042.3509791314781575.14142726525912.0584259224781570.13616752
525717.8908379644781507.43600485525491.611363232 4781555.7006546
525281.5906812474781705.49152835525035.2292324044781947.26066945
524836.0785519674782277.01660027524805.6130995714782372.59871525
524703.7693249024782488.78946033524679.3759244944782710.08198805

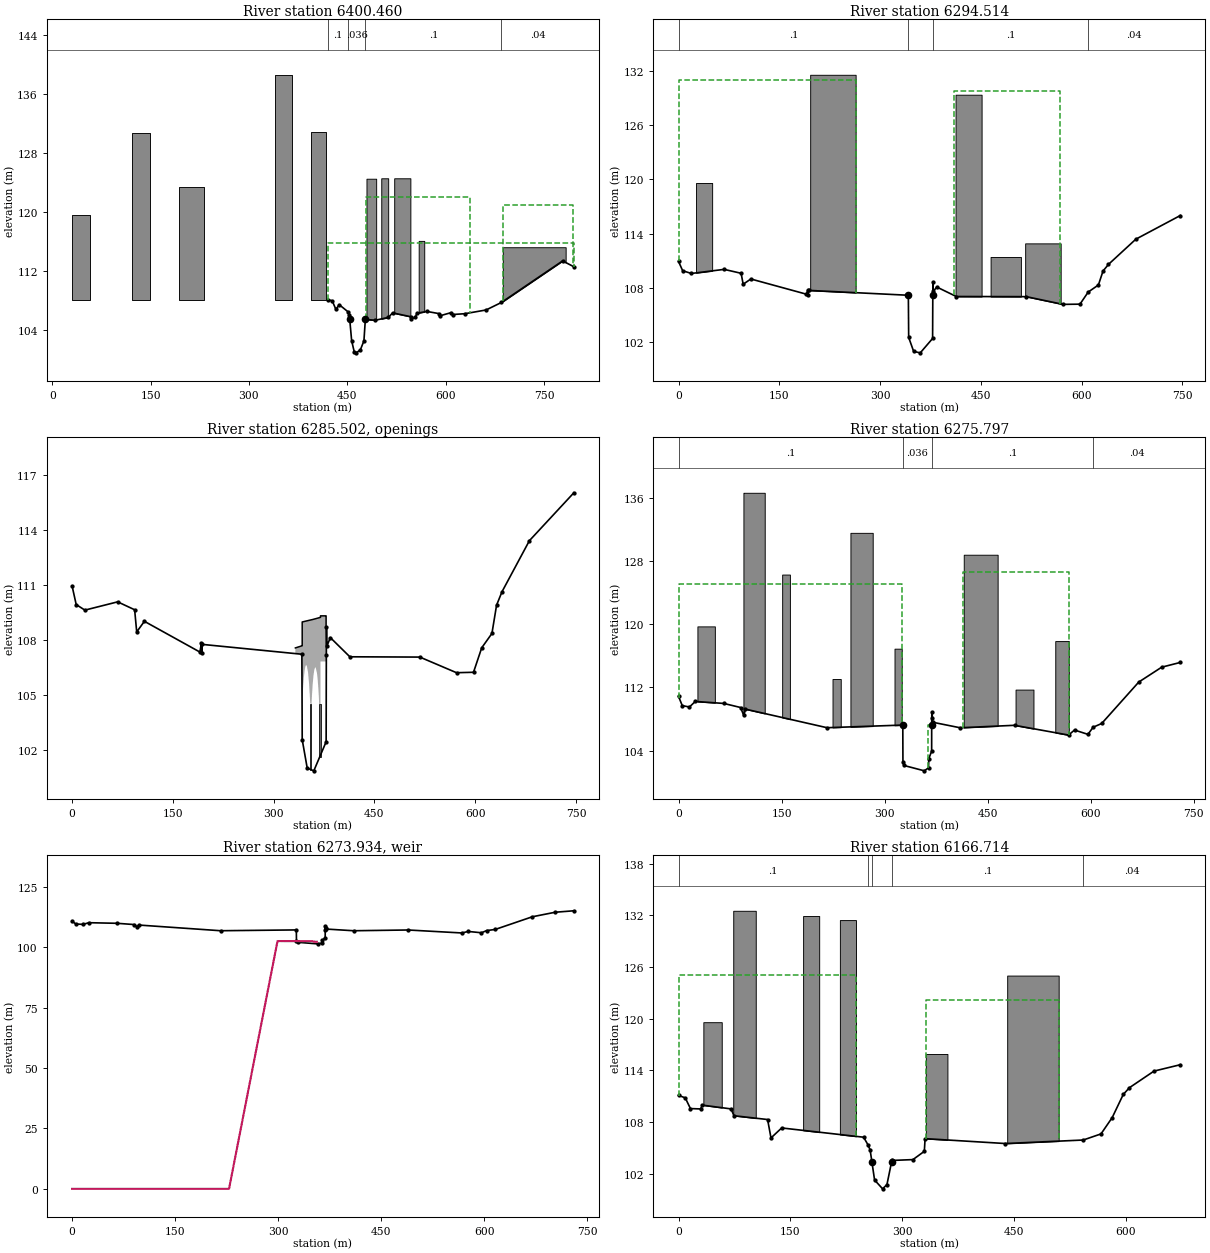
Type RM Length L Ch R = 1 ,6400.460,107.738,105.947,103.969
XS GIS Cut Line= 3
 529524.580314094780109.45072531529453.4589908724780226.44564855
529435.6967944674780463.10629951
#Sta/Elev= 30
 421.347 108.115 427.056 107.994 432.651 106.831   437.8 107.463 450.702 106.537
 453.167 106.052 453.707  105.53 456.706  102.57  460.62 101.097 463.346 100.944
 469.876  101.32  475.43  102.57 477.593 105.482 492.674 105.357 512.852 105.749
 519.161 106.361 547.261 105.828  547.96 105.551 553.811 105.743 556.152 106.303
 571.215 106.554 589.887  106.26 591.736 105.972 608.413 106.391 610.606 106.134
 629.517 106.247 661.696 106.751 685.083 107.765 778.445 113.398  795.59 112.605
#Mann= 4 ,-1 , 0
 421.347      .1       0 450.702    .036       0 477.593      .1       0
 685.083     .04       0
#XS Ineff= 3 ,-1
 421.347  415.86  115.89   479.3  637.53  122.03  687.58  794.01     121
Permanent Ineff=
       T       T       F
#Block Obstruct= 10 ,-1
   30.31   57.09  119.63  121.94  149.43  130.67  193.13  231.89  123.36
  339.74  365.11  138.61  395.42  417.97  130.83   479.3   494.1  124.53
  501.85  512.42  124.59  521.59  546.26  124.59  558.94   567.4  116.11
  687.22  783.08  115.25
Bank Sta=453.707,477.593
XS Rating Curve= 0 ,0
Exp/Cntr=0.5,0.3

Type RM Length L Ch R = 1 ,6294.514,18.486,18.717,19.262
XS GIS Cut Line= 5
529269.9805491114779842.45208584 529437.260155774780022.23857898
529416.1535373084780090.74907377529380.2910741824780184.39645382
529260.6003842514780491.24682195
#Sta/Elev= 30
       0  110.93   6.138  109.91  19.089 109.606  67.891 110.058   93.14 109.626
  96.214 108.417 107.655 108.996  190.32 107.318 192.443 107.791 192.851 107.264
 193.858 107.737 342.073   107.2 342.565  102.54 350.012 100.991 359.827  100.84
 378.181 102.427  378.47  107.18 378.686 108.677  379.08 107.625 384.428 108.108
 413.468 107.061 517.626 107.045  572.23 106.193 597.534 106.216 609.775 107.553
 624.964 108.333 631.861 109.876 639.992 110.612 680.717 113.394 746.907 116.007
#Mann= 4 ,-1 , 0
       0      .1       0 342.073    .036       0  378.47      .1       0
 609.775     .04       0
#XS Ineff= 2 ,-1
       0  263.62  130.99  410.22  568.11  129.73
Permanent Ineff=
       T       T
#Block Obstruct= 5 ,-1
   26.08   50.04   119.6  195.95  263.61  131.55  412.33   451.1  129.35
  464.49   509.6  111.43  515.95  568.81  112.93
Bank Sta=342.073,378.47
XS Rating Curve= 0 ,0
Exp/Cntr=0.5,0.3

Type RM Length L Ch R = 4 ,6285.502,,,
BEGIN DESCRIPTION:
E45
END DESCRIPTION:
Bridge Culvert--1,0,-1,-1, 0
Deck Dist Width WeirC Skew NumUp NumDn MinLoCord MaxHiCord MaxSubmerge Is_Ogee
0.01,18.52,1.44,0, 40, 40, , , 0.95, 0, ,,,
 332.367 342.342 342.543 342.543 342.552 343.109 344.093 345.105 346.379 347.125
 347.721 348.277 348.682  349.49 351.144 352.742  354.08 354.405 356.339 357.074
 358.089 358.157 359.311 360.627 361.806  362.64 364.519 365.459 366.568 367.202
 367.862 369.755 369.796   369.8 378.088 378.116 378.124 378.286 378.399   378.8
 107.545 107.662 107.664 107.664 108.961 108.966 108.974 108.983 108.994 109.001
 109.006  109.01 109.014 109.021 109.035 109.049 109.061 109.063  109.08 109.086
 109.095 109.096 109.107  109.12 109.132  109.14 109.159 109.168 109.179 109.186
 109.192 109.211 109.211 109.294 109.294 109.294 108.693 108.693 108.693 108.693
  -1.294  -1.215 104.492 104.492 104.498 104.916 105.513 105.973 106.363 106.504
 106.573 106.604 106.605 106.556 106.235 105.612 104.803 104.556 104.401 104.947
 105.528 105.568 106.034 106.358 106.479 106.472 106.173 105.865 105.346 104.961
  104.48 104.486 104.486 106.804 106.804  91.514   87.47  -1.174  -1.175  -1.175
  323.85 327.051 327.051  327.06 327.617 328.601 329.613 330.887 331.633 332.229
 332.785  333.19 333.998 335.652  337.25 338.588 338.913 340.847 341.582 342.597
 342.665 343.819 345.135 346.314 347.148 349.027 349.967 351.076  351.71  352.37
 354.263 354.304  354.31 362.596 362.624 362.632 362.794 362.907 395.277 395.578
 107.662 107.664 107.664 108.961 108.966 108.974 108.983 108.994 109.001 109.006
  109.01 109.014 109.021 109.035 109.049 109.061 109.063  109.08 109.086 109.095
 109.096 109.107  109.12 109.132  109.14 109.159 109.168 109.179 109.186 109.192
 109.211 109.211 109.294 109.294 109.294 108.693 108.693 108.693 100.004  99.924
  -1.215 104.492 104.492 104.498 104.916 105.513 105.973 106.363 106.504 106.573
 106.604 106.605 106.556 106.235 105.612 104.803 104.556 104.401 104.947 105.528
 105.568 106.034 106.358 106.479 106.472 106.173 105.865 105.346 104.961  104.48
 104.486 104.486 106.804 106.804  91.514   87.47  -1.174  -1.175  -1.665  99.924
Pier Skew, UpSta & Num, DnSta & Num=  ,355.381, 2 ,339.891, 2 , 0 , 0 , 0 ,,
       2       2
      99     108
       2       2
      99     108
Pier Skew, UpSta & Num, DnSta & Num=  ,368.835, 2 ,353.345, 2 , 0 , 0 , 0 ,,
       2       2
      99     108
       2       2
      99     108
BR Coef=-1 , 0 , 0 ,, 0 ,,,0.8,-1,1.4,0,
WSPro=,,,, 1 ,,,, 0 ,,,, 0 ,,,,-1 ,-1 ,-1 , 0 , 0 , 0 , 0 , 0
BC Mult= 1 ,0,342,0,326
BC Mult= 3 ,342,380,326,369
BC Mult= 1 ,380,800,369,750
BC Design=,, 0 ,, 0 ,,,,,,
BC Use User HTab Curves=0
BC User HTab FreeFlow(D)= 0

Type RM Length L Ch R = 1 ,6275.797,111.548,109.083,106.491
XS GIS Cut Line= 5
 529263.57963235 4779846.7808098529419.2735576854780014.11540245
 529401.952977094780083.46367911529360.0774592884780176.89058926
529242.6137861674780483.12364542
#Sta/Elev= 30
       0 110.871   5.413   109.7  15.906 109.529  24.395 110.231  65.949 109.977
  90.353 109.462   94.85 108.462  96.788 109.268 216.081 106.907  326.44  107.24
 326.648 102.507 328.158 102.126 357.879 101.447 363.859 101.838 364.311     103
 368.444 103.929 368.487 107.285 368.721  108.84 369.659 108.122 369.721   107.6
 409.857 106.899  489.17  107.21 567.697 105.975 576.401  106.61 595.971 106.063
 603.395 106.961 616.004 107.444 669.919 112.684 703.263 114.565 730.414 115.168
#Mann= 4 ,-1 , 0
       0      .1       0  326.44    .036       0 368.487      .1       0
 603.395     .04       0
#XS Ineff= 3 ,-1
      .7  324.93  125.12   362.6   368.5   107.3  414.45  568.11126.6166
Permanent Ineff=
       T       T       T
#Block Obstruct= 9 ,-1
   27.49   52.86  119.73   94.45  125.46  136.64  150.84  162.11  126.29
  224.14  236.12  113.07  250.22  282.64  131.57  314.36  324.93  116.91
  415.15  464.49   128.8  490.57  516.65  111.73  548.37  568.11  117.87
Bank Sta=326.44,368.487
XS Rating Curve= 0 ,0
Exp/Cntr=0.5,0.3

Type RM Length L Ch R = 5 ,6273.934,,,
BEGIN DESCRIPTION:
E46
END DESCRIPTION:
IW Pilot Flow=0
#Inline Weir SE= 10
       0       0  228.48       0  299.03  102.61  327.23   102.6  339.85  102.54
   342.6  102.55  345.24  102.56  349.47  102.58   352.9  102.37  356.28  102.34
IW Dist,WD,Coef,Skew,MaxSub,Min_El,Is_Ogee,SpillHt,DesHd
1,2.23,1.7,0,0.98,, 0 ,,,0,0,

Type RM Length L Ch R = 1 ,6166.714,121.216,120.942,120.715
XS GIS Cut Line= 4
529251.2201944674779839.32539951529301.2477944674779984.71789951
529244.9667944674780280.19309951529209.0094944674780495.93689951
#Sta/Elev= 30
       0 111.107   9.033 110.816   15.97 109.574  29.568 109.533   32.06 109.974
  70.462 109.537  74.362 108.746 119.491 108.304 124.067 106.167 138.374 107.326
 248.353 106.252 254.023  105.39 257.053 104.778 259.551 103.331  263.03 101.285
 273.817  100.26 279.639 100.761 285.869 103.389  286.89 103.557 314.522 103.653
 329.791 104.616 330.809 106.087 438.517 105.518 542.922 105.925 566.827 106.635
  581.86 108.528 596.748 111.223 605.042 112.002 637.969 113.925 673.266 114.665
#Mann= 5 ,-1 , 0
       0      .1       0 254.023      .1       0 259.551    .036       0
  286.89      .1       0 542.922     .04       0
#XS Ineff= 2 ,-1
     .62  237.44  125.06  332.42  510.05122.2133
Permanent Ineff=
       T       T
#Block Obstruct= 6 ,-1
    33.3   57.97   119.6   73.39  103.61  132.53  167.14  188.72  131.92
  216.48  238.06  131.45  331.81  360.79  115.91  440.97  510.04  125.01
Bank Sta=259.551,285.869
XS Rating Curve= 0 ,0
Exp/Cntr=0.3,0.1

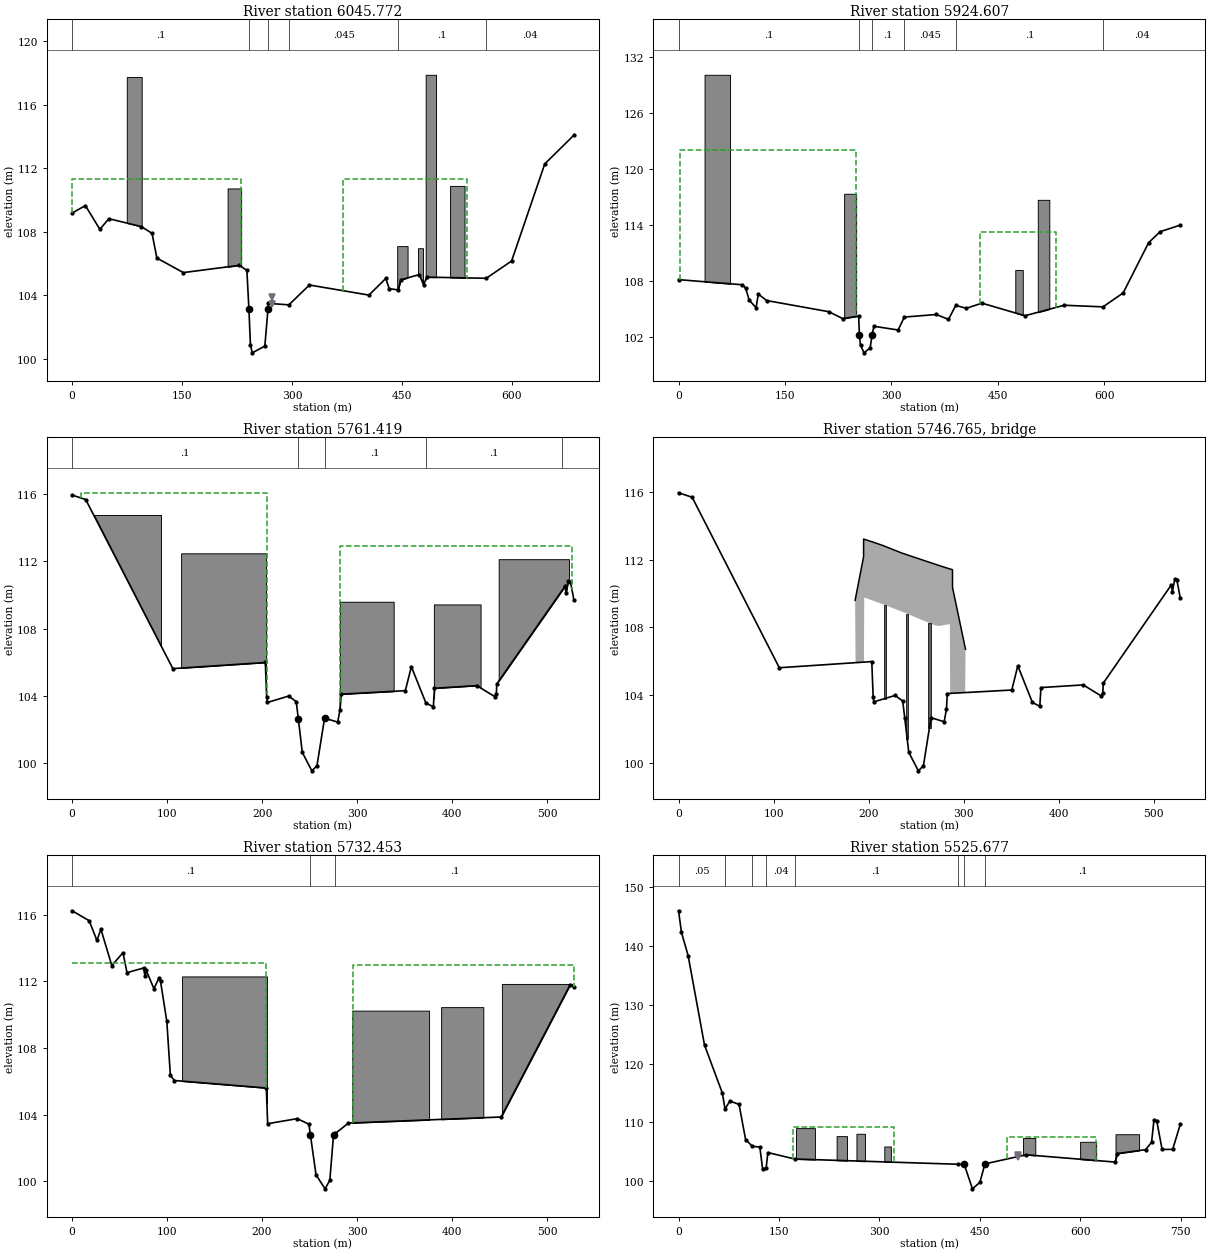
Type RM Length L Ch R = 1 ,6045.772,126.565,121.165,115.719
XS GIS Cut Line= 3
529201.7137937454779828.38183855  529131.36255734780256.74270047
529172.0099383574780503.75370843
#Sta/Elev= 30
       0 109.166  18.158 109.643  37.865  108.15  50.222 108.815  94.508 108.321
 109.067 107.892 115.692  106.34 151.751 105.424 228.231 105.882 238.456 105.561
  241.23  103.11 243.314 100.863 245.746 100.376 262.942   100.8 267.202 103.115
 267.799 103.489 295.743 103.395 323.715 104.644 404.955 104.009 427.916 105.057
 432.556 104.414 444.813 104.336  448.29 104.968 473.566 105.299 479.577 104.651
 483.655 105.139 564.931 105.066 599.532 106.156 644.723 112.261 684.433 114.067
#Mann= 6 ,-1 , 0
       0      .1       0  241.23    .036       0 267.799      .1       0
 295.743    .045       0 444.813      .1       0 564.931     .04       0
Levee=0,,,-1,273.22,103.91,Levee 8,Levee 9
#XS Ineff= 2 ,-1
       0  230.04  111.33  369.43  538.41  111.33
Permanent Ineff=
       T       T
#Block Obstruct= 6 ,-1
   74.63   94.98  117.73  212.16  230.66  110.72  443.44  457.62  107.09
  471.81  478.59  106.96  482.29  496.48  117.87  515.59  535.33  110.88
Bank Sta=241.23,267.202
XS Rating Curve= 0 ,0
Exp/Cntr=0.3,0.1

Type RM Length L Ch R = 1 ,5924.607,9.262,163.188,10.84
XS GIS Cut Line= 4
529070.3914944674779836.19859951529017.9167443084780007.52992086
529094.2060122014780242.47806436529148.5594944674780517.82399951
#Sta/Elev= 30
       0  108.11  90.081 107.562  94.458 107.218  99.578 105.914 109.231 105.104
 112.368 106.565 124.149 105.874 211.732 104.677 231.232 103.943 253.765  104.21
 254.756 102.217 256.335 101.096 261.306 100.273 269.953 100.809  272.65   102.2
 275.195 103.119 309.329 102.719 318.088 104.105 363.298 104.379 380.266 103.852
 390.545  105.35 405.317 105.042 427.396 105.593 488.001 104.246 543.366  105.37
 597.941 105.196 626.419 106.697 662.229 112.071  678.49  113.25 706.869 113.952
#Mann= 6 ,-1 , 0
       0      .1       0 254.756    .046       0  272.65      .1       0
 318.088    .045       0 390.545      .1       0 597.941     .04       0
#XS Ineff= 2 ,-1
    1.41  250.22  121.98  425.02  531.45  113.21
Permanent Ineff=
       T       T
#Block Obstruct= 4 ,-1
   36.65    72.6  130.05   233.3  250.22  117.31  474.36  484.93  109.15
  506.08  522.29  116.66
Bank Sta=254.756,272.65
XS Rating Curve= 0 ,0
Exp/Cntr=0.5,0.3

Type RM Length L Ch R = 1 ,5761.419,30.99,28.966,28.575
XS GIS Cut Line= 4
528868.5184170054779833.72926795 528922.406178344780090.34655195
528929.4894885914780266.78021229529038.9247452844780554.43860131
#Sta/Elev= 30
       0 115.943  14.322  115.68 106.014 105.623 203.314 105.986 204.729 103.921
 205.437 103.608 227.886  103.99 235.834  103.66 238.033  102.64 242.202 100.637
 252.295  99.542 257.627   99.84 265.638 102.674 279.436 102.441 281.866 103.177
 282.682 104.101 350.605 104.309 356.934 105.737 372.275 103.575 380.068 103.349
 381.282 104.453  425.77 104.611 444.533 103.962 446.346 104.125 446.814 104.712
 518.444 110.509 519.639 110.117     522 110.834  524.27 110.798   527.9 109.719
#Mann= 5 ,-1 , 0
       0      .1       0 238.033    .046       0 265.638      .1       0
 372.275      .1       0 515.653     .04       0
#XS Ineff= 2 ,-1
    8.99  204.58  116.08  282.29  525.99  112.91
Permanent Ineff=
       T       T
#Block Obstruct= 5 ,-1
    6.34   93.57  114.75  114.71  204.05  112.48  281.76  338.33   109.6
  380.62  429.78  109.44  448.81  522.82  112.13
Bank Sta=238.033,265.638
XS Rating Curve= 0 ,0
Skew Angle= 45
Exp/Cntr=0.5,0.3

Type RM Length L Ch R = 3 ,5746.765,,,
BEGIN DESCRIPTION:
E47
END DESCRIPTION:
Bridge Culvert--1,0,-1,-1, 0
Deck Dist Width WeirC Skew NumUp NumDn MinLoCord MaxHiCord MaxSubmerge Is_Ogee
0.01,28.77,1.44,45, 26, 26, , , 0.95, 0, ,,,
  185.76 186.236 194.676   194.7 195.012 195.382 203.895 206.555 215.039 217.931
 225.221 234.457 239.795 247.033 263.122 265.361 270.197 274.358 274.694 283.113
 285.442  285.72 288.227 288.236 301.591 301.918
 109.599 109.737  112.17 113.212 113.207   113.2 113.045 112.996 112.832 112.768
 112.604 112.398 112.297  112.16 111.858 111.816 111.726 111.649 111.642 111.492
 111.452 111.447 111.404 110.361 106.799 106.712
 109.599 -14.857 -14.857 -14.857 -14.857 109.765 109.596 109.541 109.364 109.304
 109.146 108.947 108.831 108.658 108.273 108.224 108.118 108.087  108.09 108.177
 108.201 -15.935  -15.99 -15.991 -16.289 106.712
 195.288 195.764 204.205 204.228 204.541  204.91 213.423 216.083 224.567 227.459
 234.749 243.985 249.323 256.562  272.65 274.889 279.725 283.886 284.222 292.641
  294.97 295.248 297.755 297.764 311.119 311.446
 109.599 109.737  112.17 113.212 113.207   113.2 113.045 112.996 112.832 112.768
 112.604 112.398 112.297  112.16 111.858 111.816 111.726 111.649 111.642 111.492
 111.452 111.447 111.404 110.361 106.799 106.712
 109.599 -14.857 -14.857 -14.857 -14.857 109.765 109.596 109.541 109.364 109.304
 109.146 108.947 108.831 108.658 108.273 108.224 108.118 108.087  108.09 108.177
 108.201 -15.935  -15.99 -15.991 -16.289 106.712
Pier Skew, UpSta & Num, DnSta & Num=  ,217.174, 4 ,226.698, 4 , 3 , 3 , 0 ,,
    1.79    1.79    2.44    2.44
      99  108.27 109.819     111
    1.79    1.79    2.44    2.44
      99  108.27 109.819     111
Pier Skew, UpSta & Num, DnSta & Num=  ,240.607, 4 ,250.132, 4 , 3 , 3 , 0 ,,
    1.79    1.79    2.44    2.44
      99 107.758 109.307     111
    1.79    1.79    2.44    2.44
      99 107.758 109.307     111
Pier Skew, UpSta & Num, DnSta & Num=  ,263.921, 4 ,273.445, 4 , 3 , 3 , 0 ,,
    1.79    1.79    2.44    2.44
      99 106.808 108.357     111
    1.79    1.79    2.44    2.44
      99 106.808 108.357     111
BR Coef=-1 , 1 , 0 ,, 0 ,,,0.8,-1,1.2,0,
WSPro=,,,, 1 ,,,, 0 ,,,, 0 ,,,,-1 ,-1 ,-1 , 0 , 0 , 0 , 0 , 0
BC Design=,, 0 ,, 0 ,,,,,,
BC Use User HTab Curves=0
BC User HTab FreeFlow(D)= 0

Type RM Length L Ch R = 1 ,5732.453,220.508,206.776,193.044
XS GIS Cut Line= 4
528845.2675290894779834.63528179528902.1486648924780092.09854862
528906.2386006754780267.68622614529015.6738573674780555.34461516
#Sta/Elev= 30
       0 116.224   18.04 115.628  26.123 114.448  30.391 115.115   41.82  112.94
  53.592 113.713  57.835 112.514   75.21 112.796  76.765 112.312  78.046  112.65
  86.179 111.558  91.465 112.192  93.139  111.99  99.734 109.602 103.506 106.357
 107.782 106.052  204.49 105.603 205.912 103.463 237.054 103.767 249.377 103.432
 250.846  102.81 256.845 100.396 266.373   99.56 271.366 100.075 275.263   102.8
 277.181  102.88 290.929 103.501 451.753 103.866 524.451   111.8 528.265  111.64
#Mann= 3 ,-1 , 0
       0      .1       0 250.846    .036       0 277.181      .1       0
#XS Ineff= 2 , 0
          204.05  113.07  295.51          112.96
Permanent Ineff=
       T       T
#Block Obstruct= 4 ,-1
  115.77  205.11  112.29  294.98  375.86  110.24  388.55  432.95  110.45
  452.51  526.52  111.84
Bank Sta=250.846,275.263
XS Rating Curve= 0 ,0
Skew Angle= 45
Exp/Cntr=0.5,0.3

Type RM Length L Ch R = 1 ,5525.677,212.63,208.146,203.662
XS GIS Cut Line= 2
528428.3712944674780066.79439951528997.4346944674780554.56289951
#Sta/Elev= 30
       0 145.963   4.374 142.299  14.359 138.321  38.804 123.146  65.421 115.002
  69.479 112.259  76.595 113.648  90.424 113.067 100.172 107.097 110.327 105.944
 121.448 105.827  125.65 102.029 130.938 102.327 133.448  104.89  173.51 103.793
 417.098 102.901 426.692 102.876 439.004  98.725 450.226  99.844 457.553 102.961
 519.133 104.512 652.093 103.272 655.263 104.718 697.541 105.382 706.535  106.63
 710.081 110.363 714.384 110.207 722.286 105.417 738.091 105.429 749.502 109.725
#Mann= 8 ,-1 , 0
       0     .05       0  69.479     .04       0 110.327      .1       0
 130.938     .04       0  173.51      .1       0 417.098      .1       0
 426.692    .036       0 457.553      .1       0
Levee=0,,,-1,507.49,104.4,,Levee 12
#XS Ineff= 3 ,-1
  121.23  133.92  104.72  170.57  322.11   109.2  491.28  623.79  107.52
Permanent Ineff=
       T       T       T
#Block Obstruct= 7 ,-1
  175.51   203.7  109.04  236.12  251.63  107.68  265.73  278.41  108.08
  307.31  317.18  105.92  514.54  532.86  107.36  599.82  623.79  106.72
  652.69  687.93     108
Bank Sta=426.692,457.553
XS Rating Curve= 0 ,0
Exp/Cntr=0.3,0.1

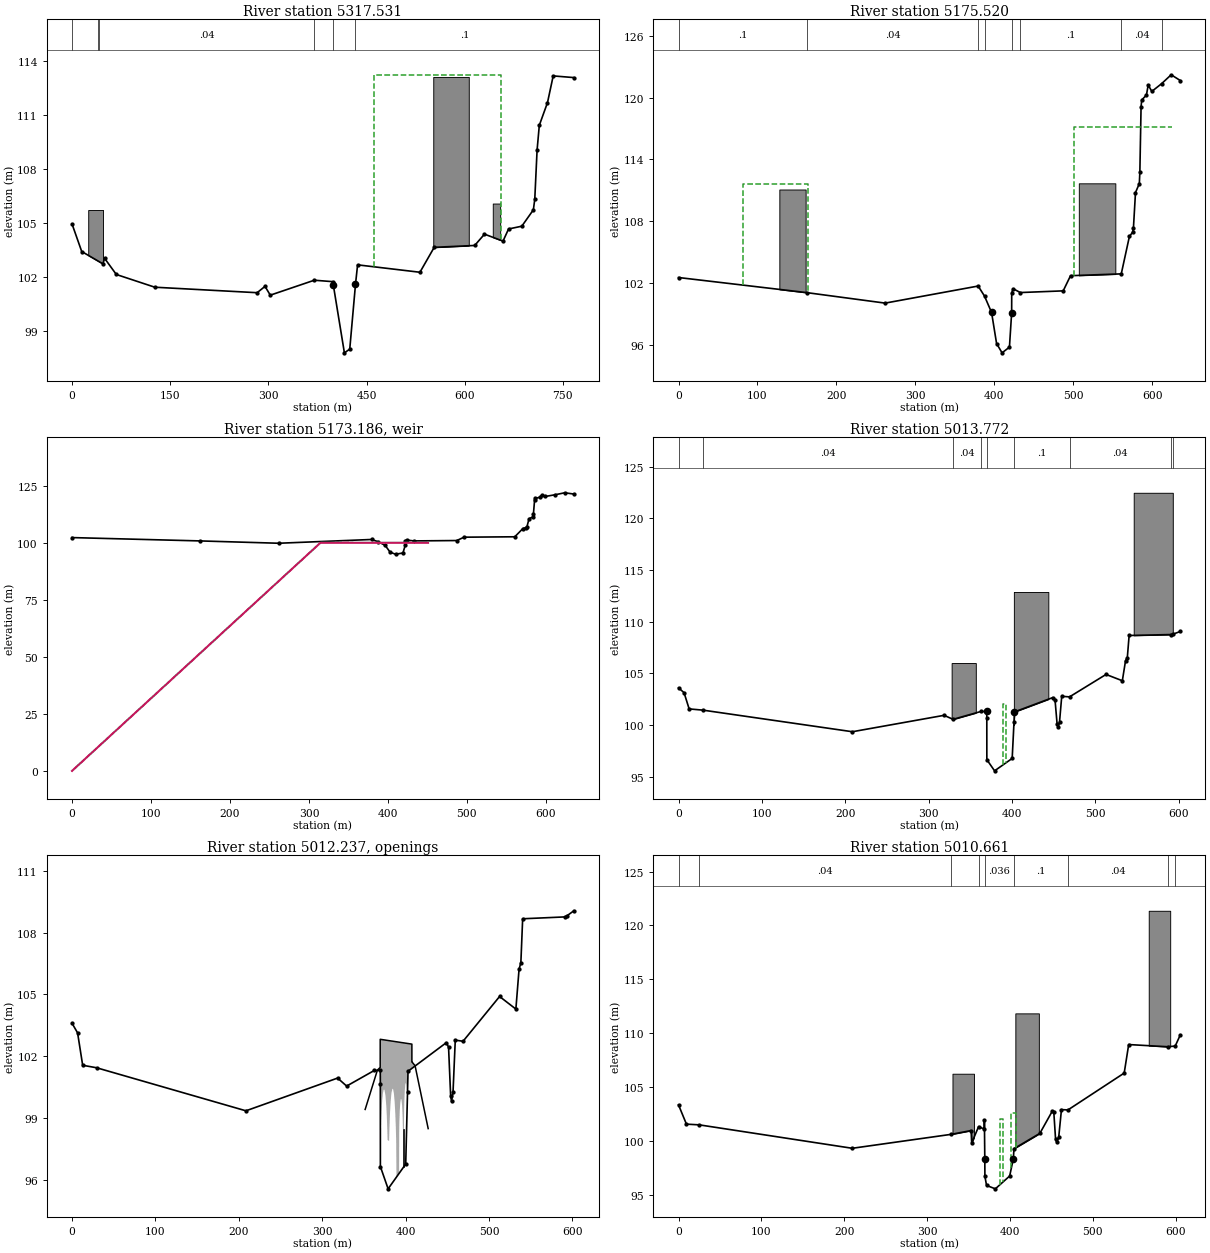
Type RM Length L Ch R = 1 ,5317.531,137.305,142.011,146.718
XS GIS Cut Line= 3
  528378.34376724780275.24247005528597.2142805854780508.70435099
529009.9415343984780679.63179954
#Sta/Elev= 30
       0 104.958  14.734 103.433  47.151 102.746  49.705 103.052  67.635 102.155
 126.453 101.447 282.785 101.142 294.811 101.494 302.882 101.005 370.127 101.836
 398.461 101.756 399.086 101.595 416.117  97.798  424.29  98.003  433.05   101.6
 436.273 102.691 531.543 102.279 553.325 103.664 615.225 103.769 630.173 104.398
 658.471  104.01 666.973 104.686 687.188  104.84 704.856  105.75 707.021 106.341
 710.531 109.066  713.95 110.451 726.448 111.712 735.162 113.197 766.736 113.104
#Mann= 6 ,-1 , 0
       0     .04       0  40.254     .04       0   41.71     .04       0
 370.127      .1       0 398.461    .036       0  433.05      .1       0
#XS Ineff= 1 ,-1
  461.67   654.8  113.26
Permanent Ineff=
       T
#Block Obstruct= 3 ,-1
   24.67   47.22  105.74  551.89  606.17  113.14  642.82   654.1   106.1
Bank Sta=399.086,433.05
XS Rating Curve= 0 ,0
Exp/Cntr=0.3,0.1

Type RM Length L Ch R = 1 ,5175.520,151.849,161.748,171.646
XS GIS Cut Line= 3
528388.1519042674780322.04457327528539.1902201154780597.91755774
528779.6571392464780810.58376094
#Sta/Elev= 30
       0 102.528 162.505  101.06 261.693 100.042 379.474 101.701 387.513 100.726
 396.473  99.132 402.813  96.115 409.748  95.211 419.102  95.765  421.91   99.12
 421.977 101.035 423.764 101.441 432.859 101.068 487.192 101.232 496.471 102.705
 560.727 102.882 571.031 106.517 575.236 106.942 576.141 107.333 578.746 110.787
 583.617 111.652 584.293  112.81 585.802 119.092 586.601 119.765 592.654 120.269
 594.859 121.237 599.387 120.607  611.76 121.357  623.94 122.225 635.529 121.665
#Mann= 8 ,-1 , 0
       0      .1       0 162.505     .04       0 379.474      .1       0
 387.513    .046       0  421.91      .1       0 432.859      .1       0
 560.727     .04       0  611.76      .1       0
#XS Ineff= 2 ,-1
   82.03  164.05   111.6  501.41  624.76  117.16
Permanent Ineff=
       T       T
#Block Obstruct= 2 ,-1
  127.67  160.97  111.08  506.96  553.22  111.68
Bank Sta=396.473,421.91
XS Rating Curve= 0 ,0
Exp/Cntr=0.3,0.1

Type RM Length L Ch R = 5 ,5173.186,,,
BEGIN DESCRIPTION:
E48
END DESCRIPTION:
IW Pilot Flow=0
#Inline Weir SE= 6
       0       0  314.67  100.28  384.16  100.28  407.94  100.29  422.54  100.28
  450.85  100.28
IW Dist,WD,Coef,Skew,MaxSub,Min_El,Is_Ogee,SpillHt,DesHd
0.1,3.8,1.7,0,0.98,, 0 ,,,0,0,

Type RM Length L Ch R = 1 ,5013.772,3.085,3.111,3.138
XS GIS Cut Line= 4
528378.6623776634780362.24921647528469.7757057824780695.09824838
 528483.319411864780784.60517506528576.8462586454780921.87062149
#Sta/Elev= 30
       0 103.597   6.627 103.132  12.718 101.562  29.424 101.441 208.478  99.353
 318.426 100.941 329.253 100.553 362.537 101.313 369.581 101.316 369.661 100.651
 369.713  96.648 378.982  95.568 400.092   96.77 402.281 100.281  402.84  101.27
 448.894 102.662 451.467 102.439 453.964  100.09 455.025  99.811 456.843 100.276
 459.511 102.781 468.861 102.727 512.656 104.898 532.186 104.288 536.009  106.22
 538.168 106.537 540.327 108.668 590.706 108.758 593.176 108.805 601.721 109.056
#Mann= 9 ,-1 , 0
       0      .1       0  29.424     .04       0 329.253     .04       0
 362.537      .1       0 369.661    .046       0 402.281      .1       0
 468.861     .04       0 590.706     .04       0 593.176     .04       0
#XS Ineff= 1 ,-1
  388.65  392.33     102
Permanent Ineff=
       T
#Block Obstruct= 3 ,-1
  327.49  356.48     106  402.11  443.44  112.88  545.82  592.69  122.48
Bank Sta=369.581,402.84
XS Rating Curve= 0 ,0
Exp/Cntr=0.5,0.3

Type RM Length L Ch R = 4 ,5012.237,,,
BEGIN DESCRIPTION:
E49
END DESCRIPTION:
Bridge Culvert--1,0,-1,-1, 0
Deck Dist Width WeirC Skew NumUp NumDn MinLoCord MaxHiCord MaxSubmerge Is_Ogee
0.01,2.91,1.44,0, 66, 66, , , 0.95, 0, ,,,
 351.451 351.925 366.161  369.19 369.492 369.506 369.887 370.317 370.648 371.455
 372.037 372.797 373.665 374.594 375.759 376.793 377.434 378.087 378.329 380.181
 380.608 381.289 382.008 382.986 384.227 385.035 385.957 386.836 387.601 388.259
  388.65 388.999 392.163 392.329 392.453 392.552 393.012 393.596 394.343 394.959
 395.674 396.092 396.399  396.71 398.019  398.02 398.047 398.194 398.481  398.98
  399.57  400.05 400.513   400.9 401.166 401.704 402.155 402.383 402.416 402.711
 407.491 407.506 407.646 411.317 426.789 427.029
  99.419   99.48  101.33 101.446 101.458 102.822  102.82 102.817 102.815  102.81
 102.807 102.802 102.797 102.791 102.784 102.777 102.773 102.769 102.768 102.756
 102.754  102.75 102.745 102.739 102.732 102.727 102.721 102.716 102.711 102.707
 102.704 102.702 102.683 102.682 102.681  102.68 102.677 102.674 102.669 102.665
 102.661 102.659 102.657 102.655 102.647 102.647 102.646 102.646 102.644 102.641
 102.637 102.634 102.631 102.629 102.627 102.624 102.621  102.62  102.62 102.618
 102.588 101.721  101.72 101.541  98.536  98.489
  99.419   -.875  -1.113  -1.163  41.695  43.637  97.887   98.54   98.92  99.592
  99.922  100.21 100.374 100.373  100.11   99.59  99.081  98.324  97.938  97.887
  98.552  99.273  99.784 100.215 100.429 100.392 100.178  99.777  99.221  98.505
  97.887   -.146   -.146  98.479  98.734  98.895  99.401  99.754  99.934  99.899
  99.639  99.341  99.011  98.468  98.468  98.596  98.862   99.37   99.86 100.328
 100.612 100.703 100.689   100.6 100.494  100.13  99.549  98.888  98.546  -1.976
  -2.054  -2.055  -2.057  -2.118  -2.373  98.489
 350.807 351.281 365.517 368.546 368.848 368.862 369.243 369.673 370.004 370.811
 371.393 372.153 373.021  373.95 375.115 376.149  376.79 377.443 377.685 379.537
 379.964 380.645 381.364 382.342 383.583 384.391 385.313 386.192 386.957 387.615
 388.006 388.355 391.519 391.685 391.809 391.908 392.368 392.952 393.699 394.315
  395.03 395.448 395.755 396.066 397.375 397.376 397.403  397.55 397.837 398.336
 398.926 399.406 399.869 400.256 400.522  401.06 401.511 401.739 401.772 402.067
 406.847 406.862 407.002 410.673 426.145 426.385
  99.419   99.48  101.33 101.446 101.458 102.822  102.82 102.817 102.815  102.81
 102.807 102.802 102.797 102.791 102.784 102.777 102.773 102.769 102.768 102.756
 102.754  102.75 102.745 102.739 102.732 102.727 102.721 102.716 102.711 102.707
 102.704 102.702 102.683 102.682 102.681  102.68 102.677 102.674 102.669 102.665
 102.661 102.659 102.657 102.655 102.647 102.647 102.646 102.646 102.644 102.641
 102.637 102.634 102.631 102.629 102.627 102.624 102.621  102.62  102.62 102.618
 102.588 101.721  101.72 101.541  98.536  98.489
  99.419   -.875  -1.113  -1.163  41.695  43.637  97.887   98.54   98.92  99.592
  99.922  100.21 100.374 100.373  100.11   99.59  99.081  98.324  97.938  97.887
  98.552  99.273  99.784 100.215 100.429 100.392 100.178  99.777  99.221  98.505
  97.887   -.146   -.146  98.479  98.734  98.895  99.401  99.754  99.934  99.899
  99.639  99.341  99.011  98.468  98.468  98.596  98.862   99.37   99.86 100.328
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Pier Skew, UpSta & Num, DnSta & Num=  ,379.26, 2 ,378.61, 2 , 0 , 0 , 0 ,,
    1.85    1.85
      94     102
    1.85    1.85
      94     102
Pier Skew, UpSta & Num, DnSta & Num=  ,397.37, 2 ,396.72, 2 , 0 , 0 , 0 ,,
     1.3     1.3
      94     102
     1.3     1.3
      94     102
BR Coef=-1 , 1 , 0 ,, 0 ,,,0.8,-1,1.6,0,
WSPro=,,,, 1 ,,,, 0 ,,,, 0 ,,,,-1 ,-1 ,-1 , 0 , 0 , 0 , 0 , 0
BC Mult= 1 ,0,369,0,368
BC Mult= 3 ,369,403,368,407
BC Mult= 1 ,403,650,407,650
BC Design=,, 0 ,, 0 ,,,,,,
BC Use User HTab Curves=0
BC User HTab FreeFlow(D)= 0

Type RM Length L Ch R = 1 ,5010.661,105.261,113.291,121.321
XS GIS Cut Line= 4
528373.7070634094780363.45768221528466.8631611224780696.03291404
528480.1133085334780784.68571042528572.4493063674780928.02635468
#Sta/Elev= 30
       0 103.344   9.536  101.56  24.947 101.495 209.633   99.32 329.282 100.617
 353.068 100.965 353.746   99.81 362.101 101.335 369.028 101.096 369.088 101.905
  369.58   98.35   369.7   96.71 371.705  95.874 382.286  95.557 399.579  96.747
 404.063  98.371 404.765  99.282 436.008 100.705 451.185  102.79 452.847 102.678
 454.991 100.145 456.372  99.894 458.751 100.328  462.08  102.91 469.883 102.877
 537.791   106.3 543.207 108.946 590.281 108.743 599.343 108.806  605.52 109.846
#Mann= 9 ,-1 , 0
       0      .1       0  24.947     .04       0 329.282     .04       0
 362.101      .1       0  369.58    .036       0 404.765      .1       0
 469.883     .04       0 590.281     .04       0 599.343     .04       0
#XS Ineff= 2 ,-1
  401.74     407   102.6  388.01  391.68     102
Permanent Ineff=
       T       T
#Block Obstruct= 3 ,-1
  330.57  356.48  106.24  406.43   434.8  111.84   567.4   593.3  121.36
Bank Sta=369.58,404.063
XS Rating Curve= 0 ,0
Exp/Cntr=0.5,0.3