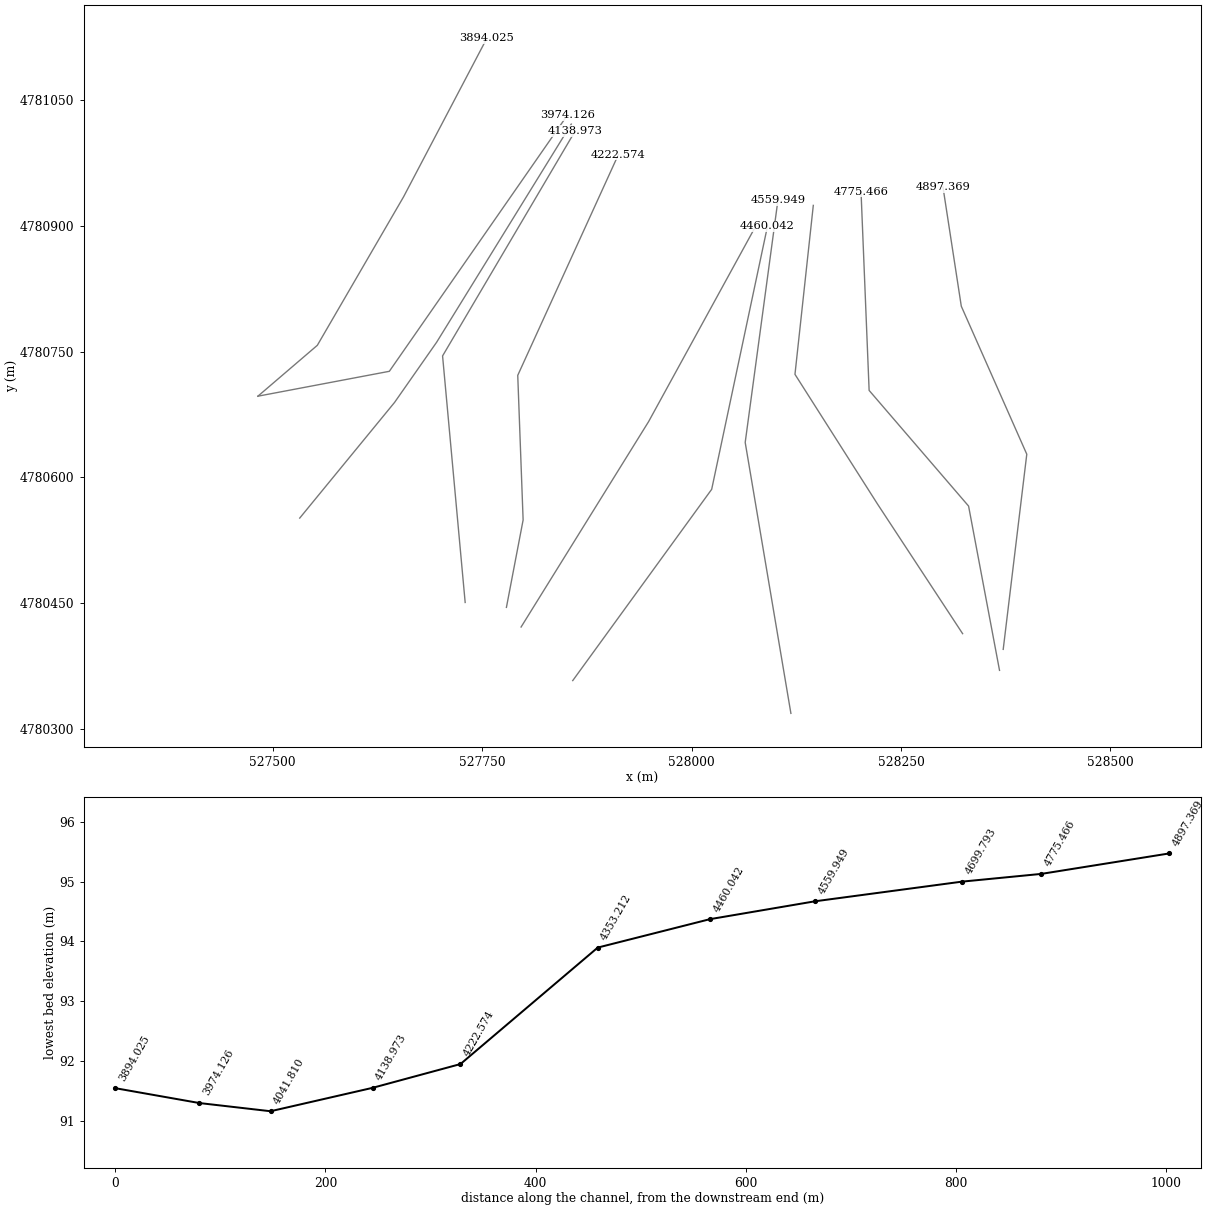
HEC-RAS study Durango.prj: Durango

--- Durango.g18 (geometry) --- (continued)

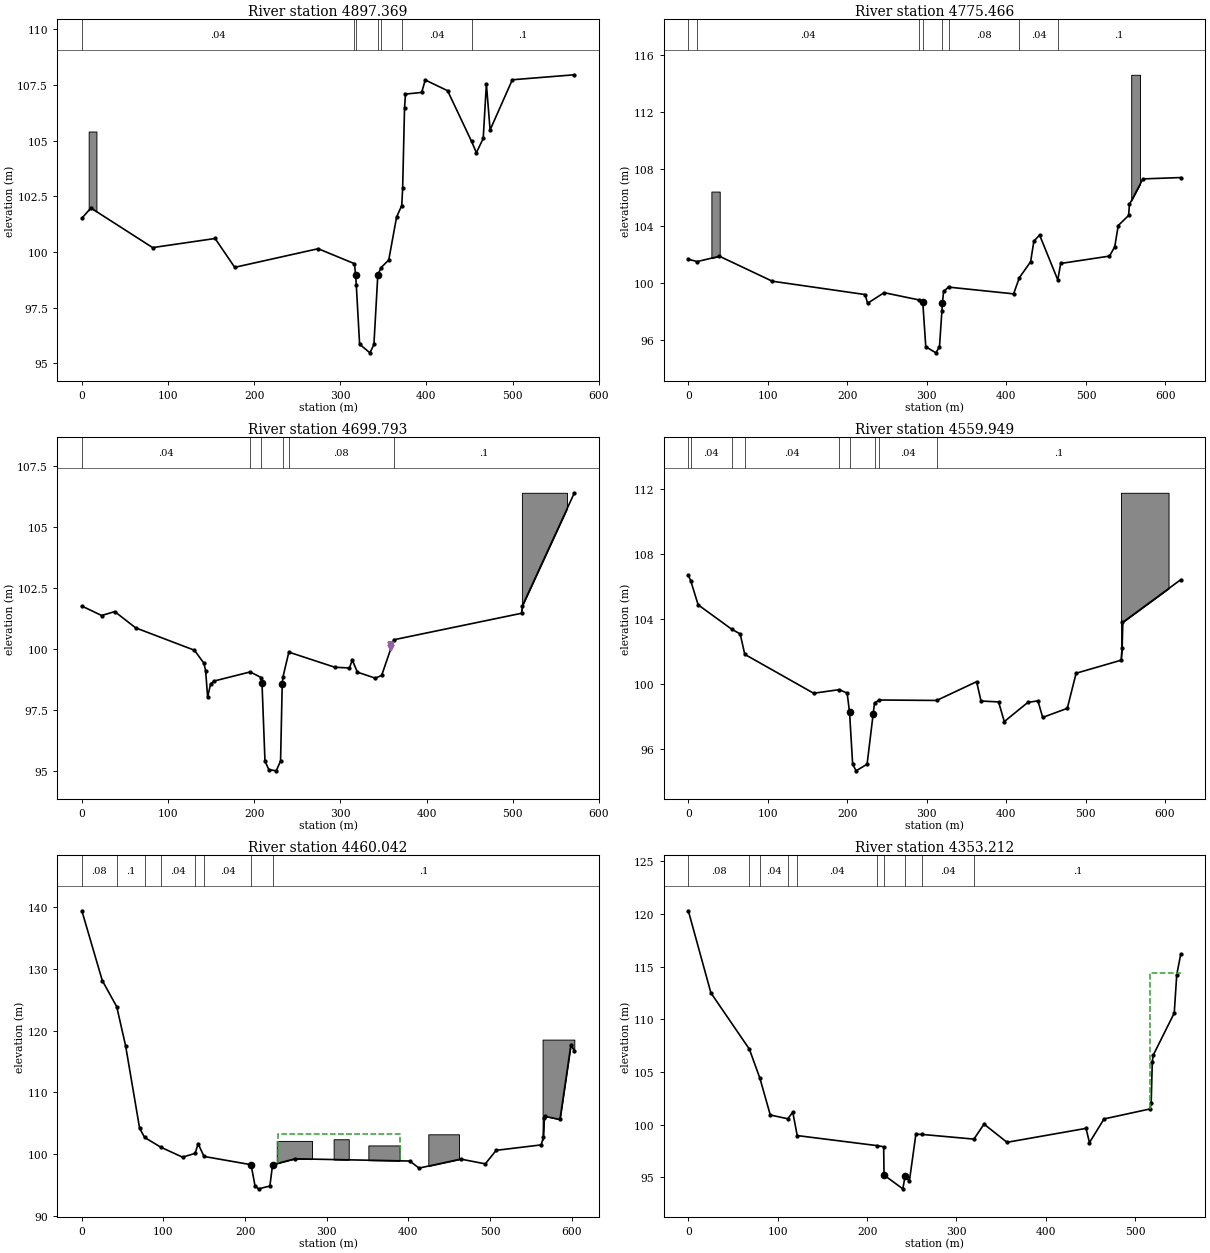
Type RM Length L Ch R = 1 ,4897.369,117.731,121.903,126.076
XS GIS Cut Line= 4
528371.9482944674780394.67599951528400.0887944674780627.61679951
528321.9206944674780804.27659951528300.0336944674780946.54239951
#Sta/Elev= 30
       0 101.517  10.474 101.976  82.164 100.198 154.716 100.607 177.475  99.312
 274.365 100.148 316.409  99.477  317.92   98.96  318.62  98.523 322.485  95.859
 334.477  95.473 339.092  95.848 343.625  98.977 347.455  99.304 356.299  99.639
 365.443 101.573 371.412 102.087 372.445 102.854 374.632 106.459 375.725  107.09
 394.522 107.165 398.689 107.723 424.627 107.242  452.43 104.969  458.08 104.458
 465.972 105.097 469.667 107.545 473.978 105.481 499.815 107.733 571.755 107.957
#Mann= 7 ,-1 , 0
       0     .04       0 316.409      .1       0  318.62    .036       0
 343.625      .1       0 347.455     .08       0 371.412     .04       0
  452.43      .1       0
#Block Obstruct= 1 ,-1
    7.93   16.92  105.41
Bank Sta=317.92,343.625
XS Rating Curve= 0 ,0
Exp/Cntr=0.3,0.1

Type RM Length L Ch R = 1 ,4775.466,77.713,75.673,73.633
XS GIS Cut Line= 4
 528367.55133022 4780369.6134154528330.6169310864780565.71748699
528211.8992195854780703.78178851528202.2259245734780941.21721152
#Sta/Elev= 30
       0 101.693  11.209 101.531  39.175 101.903  105.54 100.154 222.323  99.217
  225.39  98.604  246.19  99.349 290.439  98.836 294.835  98.661 298.574   95.56
 311.254   95.13 315.831  95.554 318.852  98.057  319.61   98.66  320.97  99.434
 327.161   99.74  409.01  99.266 416.275 100.401 430.395 101.514 434.519 102.963
 441.707 103.393 464.578 100.246  468.27 101.398 529.609 101.915 536.209 102.567
  540.63 104.059 553.641 104.764 554.724 105.546 571.656 107.328 619.272 107.423
#Mann= 8 ,-1 , 0
       0      .1       0  11.209     .04       0 290.439      .1       0
 294.835    .036       0 318.852      .1       0 327.161     .08       0
 416.275     .04       0 464.578      .1       0
#Block Obstruct= 2 ,-1
   28.99   39.47  106.44  556.92  568.02  114.63
Bank Sta=294.835,319.61
XS Rating Curve= 0 ,0
Exp/Cntr=0.3,0.1

Type RM Length L Ch R = 1 ,4699.793,145.554,139.844,134.135
XS GIS Cut Line= 4
528323.4840944674780413.43639951528221.8656944674780568.20909951
528123.3738944674780722.98179951528145.2609944674780924.65539951
#Sta/Elev= 30
       0  101.75  22.974 101.363  38.159 101.523  62.452 100.857 130.649   99.94
 141.595   99.41 143.647  99.101 145.955   98.02 149.424  98.561 153.369  98.678
 195.282  99.051 208.156  98.821 209.041  98.599 212.503  95.399 216.927  95.053
 225.537      95 230.587    95.4 232.528   98.57 233.341  98.838 240.188  99.863
 293.575  99.243  310.53  99.214 313.773   99.54 319.759  99.042 340.475  98.797
 347.889  98.908 362.079  100.37  510.21 101.454 511.312 101.767 571.463 106.381
#Mann= 6 ,-1 , 0
       0     .04       0 195.282      .1       0 208.156    .034       0
 233.341      .1       0 240.188     .08       0 362.079      .1       0
Levee=0,,,-1,358.94,100.14,,Levee 34
#Block Obstruct= 1 ,-1
  510.66     563  106.39
Bank Sta=209.041,232.528
XS Rating Curve= 0 ,0
Exp/Cntr=0.3,0.1

Type RM Length L Ch R = 1 ,4559.949,111.318,99.907,88.495
XS GIS Cut Line= 3
528118.5199145074780318.27767366528063.9662029484780641.68705134
528103.0502231954780930.90880118
#Sta/Elev= 30
       0 106.687   2.975 106.356  12.362 104.873  54.359 103.383  65.272 103.083
  71.032  101.83 157.722   99.44 189.854   99.66 199.898   99.45  202.94   98.26
 206.803   95.08 211.128  94.671 224.998   95.08 232.684  98.181  234.32  98.846
 240.465  99.025 312.518  98.997 362.836  100.15 368.375  98.962 390.495  98.907
 397.678  97.698 427.213  98.873 439.993  98.975 445.995  97.955 476.976  98.512
 488.058 100.669  544.67  101.47 545.895 102.191 546.448 103.788 619.829 106.421
#Mann= 9 ,-1 , 0
       0     .08       0   2.975     .04       0  54.359      .1       0
  71.032     .04       0 189.854      .1       0  202.94    .034       0
  234.32      .1       0 240.465     .04       0 312.518      .1       0
#Block Obstruct= 1 ,-1
  544.58  604.41  111.76
Bank Sta=202.94,232.684
XS Rating Curve= 0 ,0
Exp/Cntr=0.3,0.1

Type RM Length L Ch R = 1 ,4460.042,105.799,106.83,107.86
XS GIS Cut Line= 3
527858.0986734014780357.40369978528023.9619866524780585.73693091
528090.5432944674780899.64159951
#Sta/Elev= 30
       0 139.383  25.013 128.092   42.76 123.842   53.63 117.496  70.744 104.182
  76.836 102.697  96.557 101.122 123.306  99.501 138.714 100.112 142.394 101.677
 149.631  99.615  207.22   98.28 212.163  94.824  216.48  94.372 230.284  94.828
 233.632  98.282 233.643  98.285 261.087  99.236 401.698  98.874 412.967  97.727
 464.079  99.187 494.168  98.414 507.453 100.605  562.64 101.486 565.184 102.697
 566.304 105.866 567.326 106.108 585.586   105.6 599.016 117.687 603.106 116.711
#Mann= 8 ,-1 , 0
       0     .08       0   42.76      .1       0  76.836      .1       0
  96.557     .04       0 138.714      .1       0 149.631     .04       0
  207.22    .034       0 233.632      .1       0
#XS Ineff= 1 ,-1
  239.91  389.16   103.2
Permanent Ineff=
       T
#Block Obstruct= 5 ,-1
  238.68  281.85  102.13  308.37  326.87   102.4  350.93  389.16   101.4
  424.32  461.94   103.2  564.32  603.17  118.53
Bank Sta=207.22,233.643
XS Rating Curve= 0 ,0
Exp/Cntr=0.3,0.1

Type RM Length L Ch R = 1 ,4353.212,122.191,130.638,139.085
XS GIS Cut Line= 3
527796.4559861324780421.35844935527948.6950298884780666.59496678
528074.7342102944780896.62013556
#Sta/Elev= 30
       0 120.289  25.246 112.496  68.262 107.158  80.107 104.384  91.684 100.904
  111.29 100.547 116.858 101.171 121.813  98.952 210.959      98 218.537  97.888
 218.937  95.203 239.935  93.896 242.472   95.07 242.855  95.112 247.253    94.6
 254.569  99.078 261.334  99.063 319.489  98.616 330.792  100.04  356.51  98.313
 444.901  99.635 448.771  98.286 465.097 100.532 516.516 101.479 517.835 102.082
 519.037 105.952 520.045 106.576 543.617 110.583 546.404 114.214 550.941 116.194
#Mann= 10 ,-1 , 0
       0     .08       0  68.262      .1       0  80.107     .04       0
  111.29      .1       0 121.813     .04       0 210.959      .1       0
 218.537    .038       0 242.855      .1       0 261.334     .04       0
 319.489      .1       0
#XS Ineff= 2 , 0
                          516.48          114.36
Permanent Ineff=
       T       T
Bank Sta=218.937,242.472
XS Rating Curve= 0 ,0
Exp/Cntr=0.3,0.1

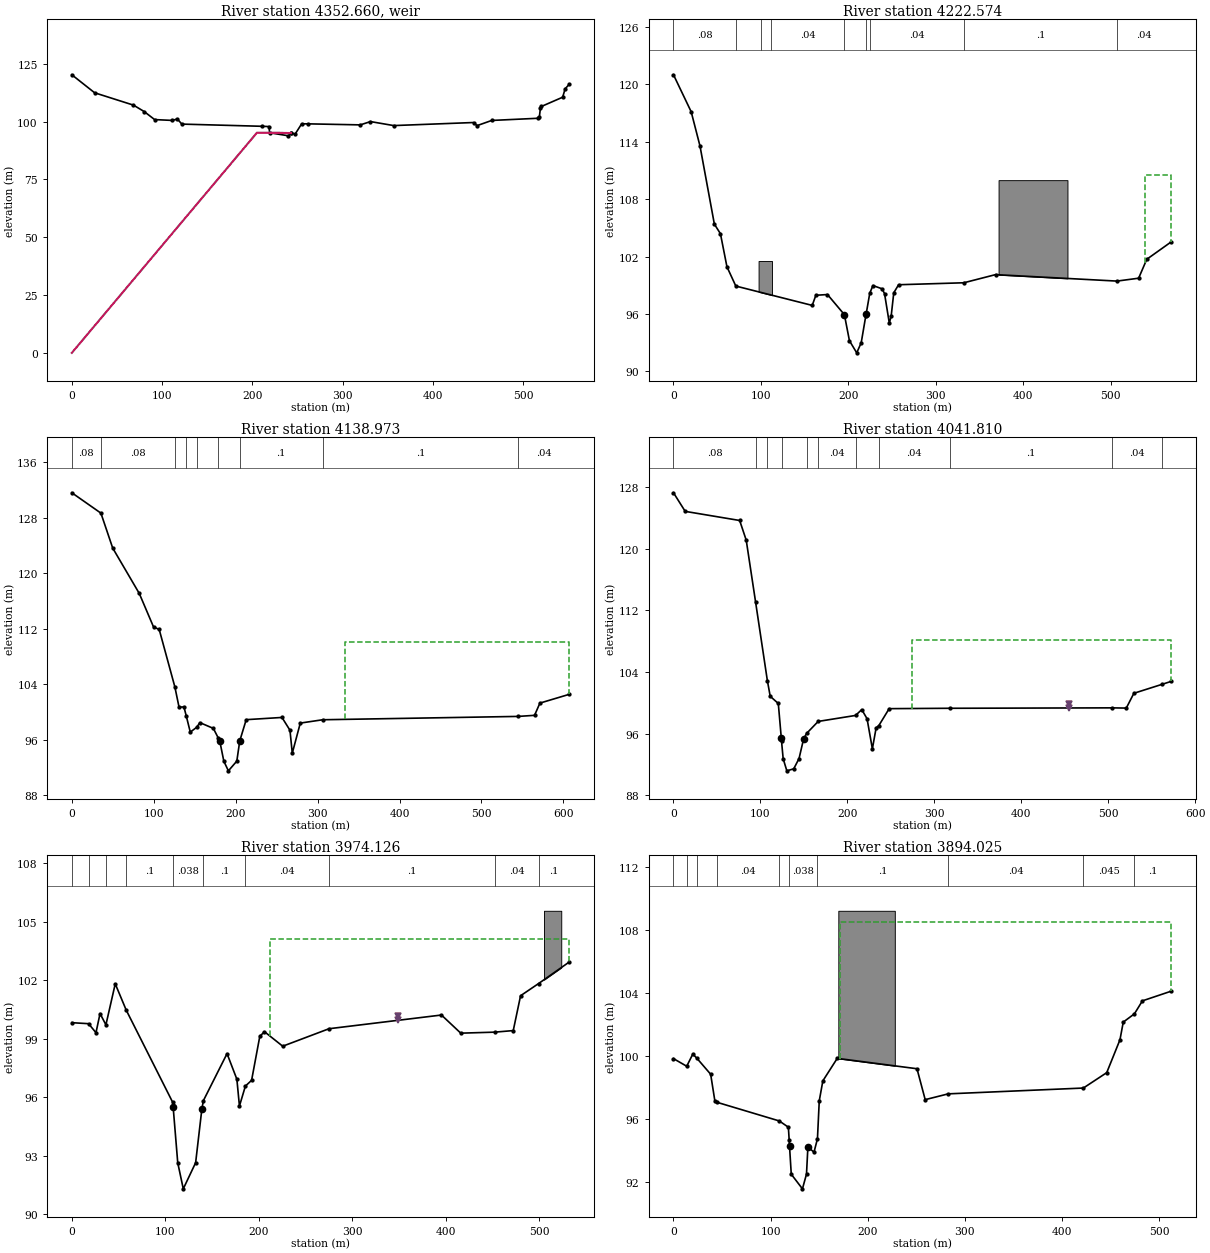
Type RM Length L Ch R = 5 ,4352.660,,,
BEGIN DESCRIPTION:
E50
END DESCRIPTION:
IW Pilot Flow=0
#Inline Weir SE= 6
       0       0  205.08   95.26  218.97   95.26  231.85   95.16  240.44   95.08
   242.7   95.08
IW Dist,WD,Coef,Skew,MaxSub,Min_El,Is_Ogee,SpillHt,DesHd
0.1,1.75,1.7,0,0.98,, 0 ,,,0,0,

Type RM Length L Ch R = 1 ,4222.574,82.841,83.601,84.361
XS GIS Cut Line= 4
527778.9459944674780444.80129951527798.8787944674780549.15559951
527792.4589794254780721.76225637527912.6132944674780985.33329951
#Sta/Elev= 30
       0 120.969  20.229 117.109  30.309  113.53  46.728 105.382  53.671 104.381
  61.105 100.931   71.25  98.916 158.601  96.897 162.762  97.954 176.045  98.031
 195.376  95.932 201.156  93.207 209.478  91.946 214.612      93 219.805   95.79
  220.19   95.96 224.383   98.17  228.02  98.971 238.416   98.63 241.276  98.128
 246.711  95.061 248.825  95.752 251.827  98.213 257.339  99.054 331.912  99.259
 368.187  100.11 506.937  99.435  531.75  99.736 541.055  101.71 568.634 103.505
#Mann= 9 ,-1 , 0
       0     .08       0   71.25     .04       0 100.364      .1       0
  111.85     .04       0 195.376    .038       0 219.805      .1       0
 224.383     .04       0 331.912      .1       0 506.937     .04       0
#XS Ineff= 2 , 0
                          539.21          110.53
Permanent Ineff=
       T       T
#Block Obstruct= 2 ,-1
   97.27   112.6  101.53  371.63   450.4  109.97
Bank Sta=195.376,220.19
XS Rating Curve= 0 ,0
Exp/Cntr=0.3,0.1

Type RM Length L Ch R = 1 ,4138.973,108.257,97.163,86.069
XS GIS Cut Line= 3
527729.7001197824780450.66390239527702.7321458114780744.96657485
527861.0224278134781013.47379395
#Sta/Elev= 30
       0 131.592  35.462 128.663  49.874  123.63   82.32 117.092  99.737 112.263
 106.622 111.913 125.757 103.637  130.86  100.72 136.826 100.752 139.662   99.46
  144.58  97.123 152.475  97.828 156.296  98.492 172.756   97.66 179.021  96.212
 180.532  95.865 185.535  92.938 191.093  91.548 201.392  92.948  204.96   95.85
 212.865  98.918 256.526  99.237 266.272  97.393   269.1  94.089 278.881  98.425
 306.281  98.905 545.048  99.387 564.874  99.542 571.403 101.303 607.228 102.566
#Mann= 9 ,-1 , 0
       0     .08       0  35.462     .08       0 125.757      .1       0
 139.662      .1       0 152.475     .04       0 179.021    .038       0
  204.96      .1       0 306.281      .1       0 545.048     .04       0
#XS Ineff= 1 ,-1
  333.04 607.228  110.07
Permanent Ineff=
       T
Bank Sta=180.532,204.96
XS Rating Curve= 0 ,0
Exp/Cntr=0.3,0.1

Type RM Length L Ch R = 1 ,4041.810,77.727,67.684,57.64
XS GIS Cut Line= 4
527532.2306369494780551.40837215527645.4243818394780689.46301791
527695.6969944674780761.38189951527856.3323944674781021.68139951
#Sta/Elev= 30
       0 127.287  13.469 124.871  76.127 123.687   83.67 121.129  94.348 113.155
 107.965 102.893 111.255 100.845 120.565  99.907  124.02   95.39  124.31   94.98
 126.156  92.733 130.399  91.156 138.302   91.42 144.419  92.754 149.726   95.33
 153.169  96.025 166.438  97.577 209.407  98.354 216.567  99.116 222.668  97.924
 228.769  94.017 233.091  96.741 236.241  97.045 248.085  99.236 317.543  99.285
 504.178   99.34 520.847  99.311 529.567 101.233 562.137 102.402  572.15 102.766
#Mann= 11 ,-1 , 0
       0     .08       0  94.348      .1       0 107.965      .1       0
  124.31    .038       0 153.169      .1       0 166.438     .04       0
 209.407      .1       0 236.241     .04       0 317.543      .1       0
 504.178     .04       0 562.137      .1       0
Levee=0,,,-1,454.63,99.87,,Levee 14
#XS Ineff= 2 , 0
                          274.36          108.19
Permanent Ineff=
       T       T
Bank Sta=124.02,149.726
XS Rating Curve= 0 ,0
Exp/Cntr=0.3,0.1

Type RM Length L Ch R = 1 ,3974.126,67.842,80.102,92.361
XS GIS Cut Line= 3
527482.2982716164780696.89322994527639.1874475694780726.60119714
527851.6422629544781032.23412367
#Sta/Elev= 30
       0  99.812  17.872  99.761  25.814  99.298  30.139 100.281  36.435  99.702
  46.398 101.805   58.19 100.451 107.708  95.742 108.365  95.468 113.239  92.629
 119.154  91.293 132.373  92.633 139.084  95.409 140.714   95.82 165.956  98.226
 176.468  96.913 179.212  95.539 185.579  96.562 192.209  96.857 200.996  99.115
 206.005  99.349 225.491  98.606 275.044  99.503 395.244 100.205  415.89  99.275
  452.22  99.327 472.008  99.407 479.836 101.194 499.027 101.816 531.898 102.924
#Mann= 10 ,-1 , 0
       0     .08       0  17.872      .1       0  36.435      .1       0
   58.19      .1       0 107.708    .038       0 140.714      .1       0
 185.579     .04       0 275.044      .1       0  452.22     .04       0
 499.027      .1       0
Levee=0,,,-1,348.9,100.13,,Levee 14
#XS Ineff= 2 , 0
                          211.98          104.08
Permanent Ineff=
       T       T
#Block Obstruct= 1 ,-1
  504.85  523.35  105.55
Bank Sta=108.365,139.084
XS Rating Curve= 0 ,0
Exp/Cntr=0.3,0.1

Type RM Length L Ch R = 1 ,3894.025,43.12,44.719,46.317
XS GIS Cut Line= 4
527482.2982944674780696.89319951527553.2267602844780757.61324118
527656.1874058954780934.88969088527755.5688944674781124.05709951
#Sta/Elev= 30
       0  99.812  13.621  99.327  19.885   100.1  24.016   99.84  38.263   98.82
  42.668  97.097  44.549  97.042 108.924  95.853 118.283  95.455 119.111   94.62
  119.45   94.25  121.25   92.47 132.753  91.542 136.933   92.48 138.363    94.2
 144.657  93.868 148.214  94.726 150.067  97.133 153.775    98.4 168.569  99.827
 250.676  99.169 259.118  97.206 282.862  97.574 421.938  97.943 446.005   98.92
 459.629 101.007 463.018  102.13 474.527 102.657 482.741  103.48 512.061 104.088
#Mann= 10 ,-1 , 0
       0     .08       0  13.621      .1       0  24.016      .1       0
  44.549     .04       0 108.924      .1       0 119.111    .038       0
 148.214      .1       0 282.862     .04       0 421.938    .045       0
 474.527      .1       0
#XS Ineff= 2 , 0
                          171.81          108.48
Permanent Ineff=
       T       T
#Block Obstruct= 1 ,-1
  169.69  227.84   109.2
Bank Sta=119.45,138.363
XS Rating Curve= 0 ,0
Exp/Cntr=0.3,0.1