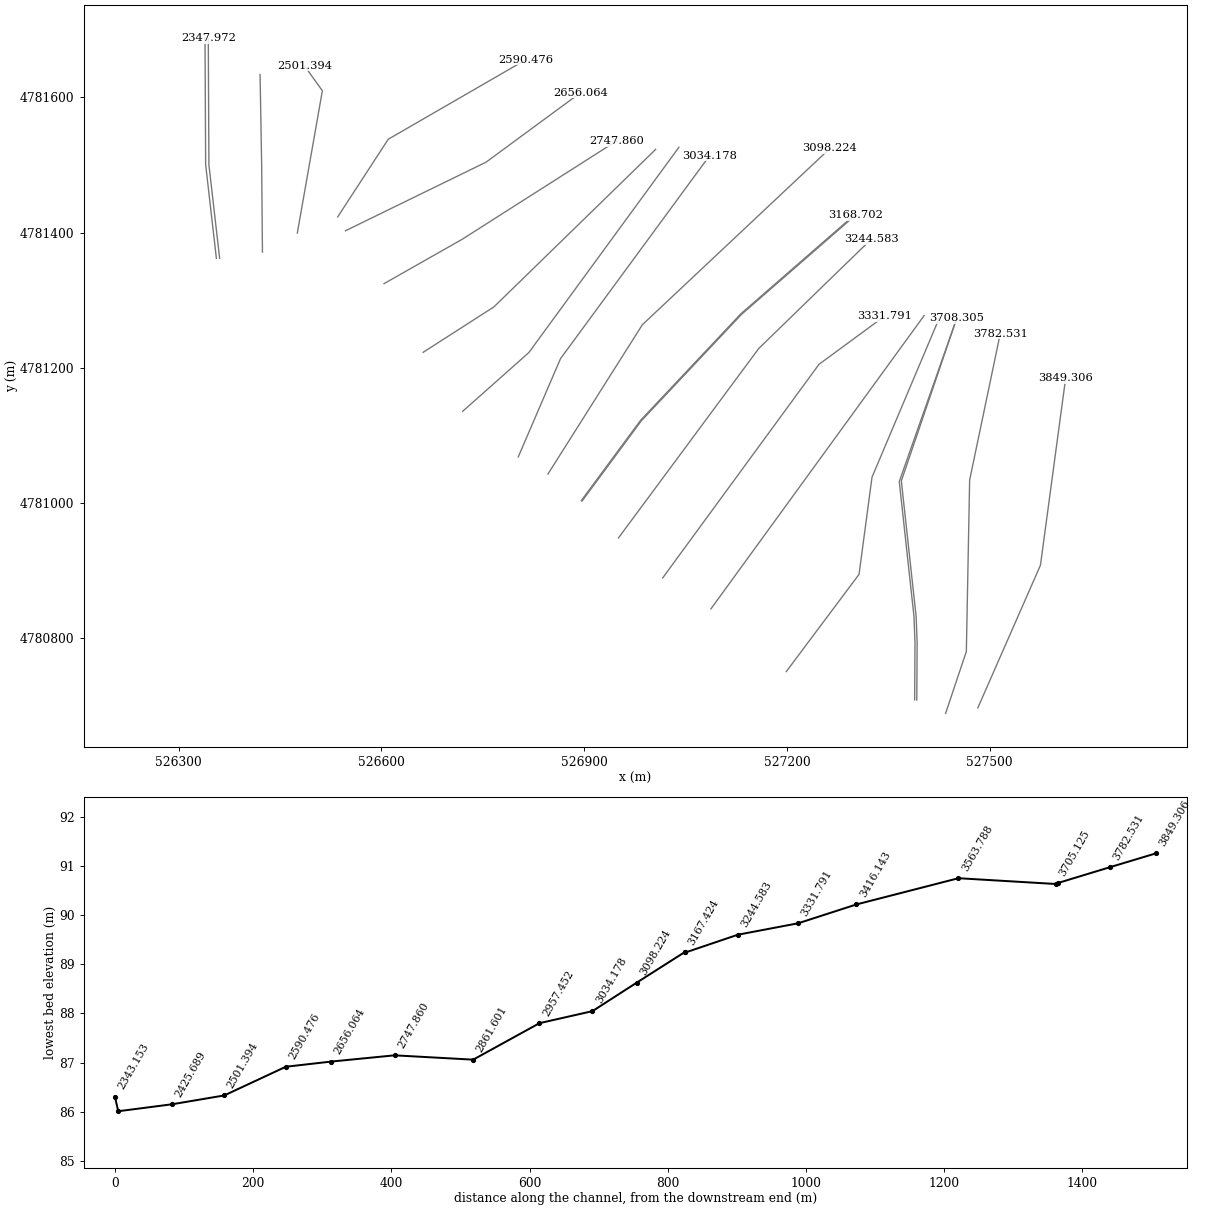
HEC-RAS study Durango.prj: Durango

--- Durango.g18 (geometry) --- (continued)

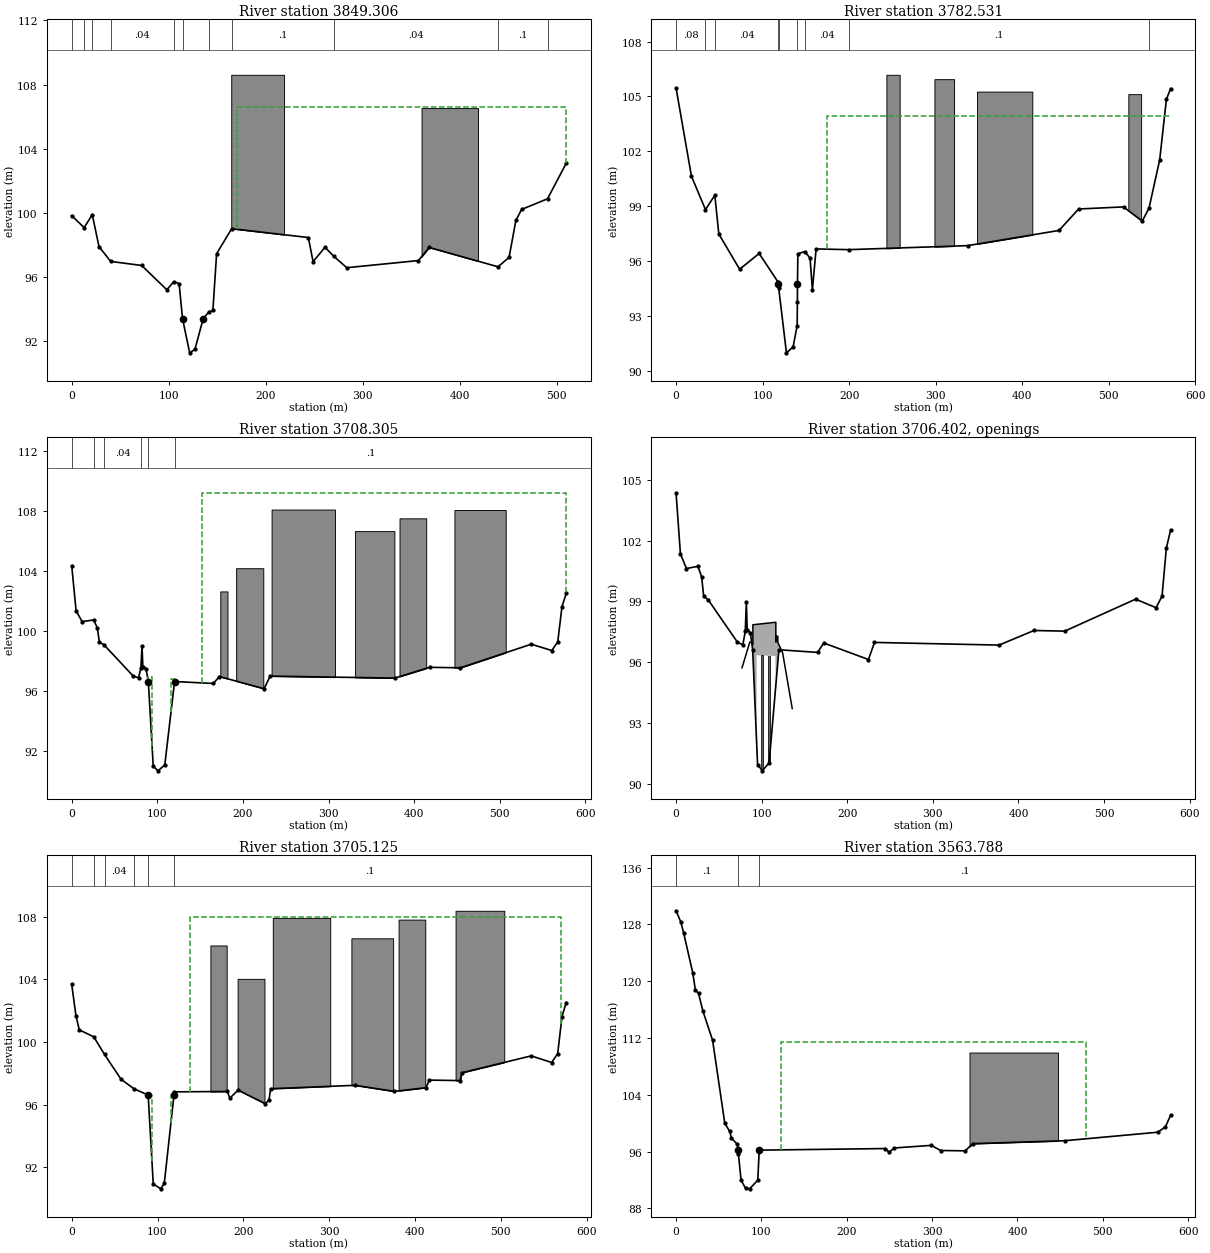
Type RM Length L Ch R = 1 ,3849.306,61.166,66.775,72.384
XS GIS Cut Line= 3
527482.2982716164780696.89322994527574.9273996024780907.94693928
527612.2282114264781184.62516136
#Sta/Elev= 30
       0  99.812  12.844   99.07  21.202  99.882  28.119  97.883  40.162   96.96
  72.069  96.707  98.012  95.192 105.144  95.688  110.66   95.58  114.23   93.38
 121.557  91.253  126.98   91.47 135.567  93.396 141.076  93.785 145.496  93.901
 149.339  97.442 164.864  99.004 243.882  98.451 248.748  96.944 261.088  97.845
 269.818  97.294 283.426  96.567 357.318  97.013 368.417  97.833 439.333  96.624
 450.739  97.211 457.724  99.515 463.645 100.205 490.351 100.868 509.668 103.092
#Mann= 11 ,-1 , 0
       0     .08       0  12.844      .1       0  21.202      .1       0
  40.162     .04       0 105.144      .1       0  114.23    .038       0
 141.076     .04       0 164.864      .1       0 269.818     .04       0
 439.333      .1       0 490.351     .04       0
#XS Ineff= 2 , 0
                          170.75          106.61
Permanent Ineff=
       T       T
#Block Obstruct= 2 ,-1
  164.41  218.85  108.61  360.53  418.68  106.53
Bank Sta=114.23,135.567
XS Rating Curve= 0 ,0
Exp/Cntr=0.3,0.1

Type RM Length L Ch R = 1 ,3782.531,73.397,74.226,75.055
XS GIS Cut Line= 4
527434.5912944674780688.75889951527465.2911085794780780.29083323
527470.1900780364781033.98809381527515.4952944674781250.68939951
#Sta/Elev= 30
       0  105.46  17.807  100.63  34.015  98.806  44.819  99.588  49.449   97.47
  73.504  95.543  96.078  96.406 117.897  94.844  118.27  94.722 118.679   94.51
 127.621  90.971 135.294  91.293  140.01  92.466 140.266  93.766  140.37   94.71
 140.807   96.39  148.75  96.507 154.904  96.159 157.604  94.415 161.906  96.656
   199.4  96.615 336.938  96.834 442.729  97.666  465.34  98.839 517.244  98.953
 538.933  98.175 546.749  98.891 559.069 101.526 566.797 104.833 571.674 105.424
#Mann= 9 ,-1 , 0
       0     .08       0  34.015      .1       0  44.819     .04       0
 117.897    .038       0 118.679      .1       0 140.266      .1       0
  148.75     .04       0   199.4      .1       0 546.749      .1       0
#XS Ineff= 2 , 0
                          174.45          103.94
Permanent Ineff=
       T       T
#Block Obstruct= 4 ,-1
  243.17   258.5  106.18  298.68  321.41  105.94  347.84  411.81  105.26
  522.82  537.62  105.12
Bank Sta=118.27,140.37
XS Rating Curve= 0 ,0
Exp/Cntr=0.5,0.3

Type RM Length L Ch R = 1 ,3708.305,3.18,3.18,3.18
XS GIS Cut Line= 5
   527391.989022 4780708.5223749   527392.522271 4780793.3266936
  527391.0064958 4780832.1542704  527369.1308529 4781032.6405527
         527451.        4781273.
#Sta/Elev= 30
       0 104.356   5.119 101.351  12.119 100.624  25.572 100.733   29.85 100.215
  32.313  99.255  37.641  99.078  71.785  96.988  78.038  96.871  80.847  97.525
  82.121  98.985  83.121  97.606  86.796  97.467  89.531  96.613  95.232  90.965
 100.821  90.654 108.745  91.055 120.148  96.621 165.396   96.49   172.5  96.954
 224.747   96.14 231.788  96.982377.2521 96.8503418.1355 97.5697454.0331 97.5384
 536.797 99.1143560.7288  98.692567.7089 99.2663572.6947101.6246577.6804102.5193
#Mann= 6 ,-1 , 0
       0      .1       0  25.572      .1       0  37.641     .04       0
  80.847      .1       0  89.531    .038       0 120.148      .1       0
#XS Ineff= 3 ,-1
   89.53   94.16    96.9  116.04  120.15    96.8  152.25  578.85  109.23
Permanent Ineff=
       T       T       T
#Block Obstruct= 6 ,-1
  173.57  181.94  102.64  192.07  223.79  104.19  233.48  307.49  108.11
  330.84  376.91  106.67  382.91  414.09107.5233  447.05  506.96  108.08
Bank Sta=89.531,120.148
XS Rating Curve= 0 ,0
Exp/Cntr=0.5,0.3

Type RM Length L Ch R = 4 ,3706.402,,,
BEGIN DESCRIPTION:
E51
END DESCRIPTION:
Bridge Culvert--1,0,-1,-1, 0
Deck Dist Width WeirC Skew NumUp NumDn MinLoCord MaxHiCord MaxSubmerge Is_Ogee
0.01,2.98,1.44,0, 19, 19, , , 0.95, 0, ,,,
   77.04  77.277  86.224  88.174  89.726  89.733   93.94  94.159 116.039 116.436
 116.559 116.576  116.67 116.681 118.871  118.89 124.465 135.449 135.732
  95.732  95.765  97.002  96.979  96.869  97.853  97.872  97.873  97.974  97.976
  97.977  97.002  97.002    97.3  97.284   96.98  96.478  93.792  93.723
  95.732   9.238   9.238   9.238   9.238   9.238   9.238   96.35  96.308   9.141
   9.141   9.141   9.141   9.141   9.141   9.141   9.141   9.141  93.723
  76.595  76.832  85.779  87.729  89.281  89.288  93.495  93.714 115.594 115.991
 116.114 116.131 116.225 116.236 118.426 118.445  124.02 135.004 135.287
  95.732  95.765  97.002  96.979  96.869  97.853  97.872  97.873  97.974  97.976
  97.977  97.002  97.002    97.3  97.284   96.98  96.478  93.792  93.723
  95.732   9.238   9.238   9.238   9.238   9.238   9.238   96.35  96.308   9.141
   9.141   9.141   9.141   9.141   9.141   9.141   9.141   9.141  93.723
Pier Skew, UpSta & Num, DnSta & Num=  ,100.571, 4 ,101.011, 4 , 0 , 0 , 0 ,,
    2.36    2.36     1.9     1.9
      89  91.666  91.666      97
    2.36    2.36     1.9     1.9
      89  91.666  91.666      97
Pier Skew, UpSta & Num, DnSta & Num=  ,108.313, 4 ,108.753, 4 , 0 , 0 , 0 ,,
    2.36    2.36     1.9     1.9
      89  91.666  91.666      97
    2.36    2.36     1.9     1.9
      89  91.666  91.666      97
BR Coef=-1 , 1 , 0 ,, 0 ,,,0.8,0,1.33,0,
WSPro=,,,, 1 ,,,, 0 ,,,, 0 ,,,,-1 ,-1 ,-1 , 0 , 0 , 0 , 0 , 0
BC Mult= 1 ,0,89,0,87
BC Mult= 3 ,89,120,87,120
BC Mult= 1 ,120,600,120,600
BC Design=,, 0 ,, 0 ,,,,,,
BC Use User HTab Curves=0
BC User HTab FreeFlow(D)= 0

Type RM Length L Ch R = 1 ,3705.125,151.052,141.337,131.621
XS GIS Cut Line= 5
  527388.7989693 4780708.7294327  527389.3322183 4780793.5337514
  527387.8164431 4780832.3613282  527366.0724805  4781031.640784
         527451.        4781273.
#Sta/Elev= 30
       0 103.681   4.912 101.684   8.829 100.772   25.72 100.332  38.234  99.207
  57.566  97.618  72.655  97.013  89.081  96.619  95.047  90.944 103.765  90.631
 107.911  90.983 119.253  96.644 119.492   96.82 181.515  96.843 184.301  96.416
 193.935  96.931 225.544  96.062 229.917  96.294 231.888  97.019 330.113 97.2368
375.9821 96.8503412.8769 97.0848416.8655 97.5697452.7631 97.5384454.7574  98.039
 535.527 99.1143559.4587  98.692566.4389 99.2663571.4247101.6246576.4104102.5193
#Mann= 6 ,-1 , 0
       0      .1       0   25.72      .1       0  38.234     .04       0
  72.655      .1       0  89.081    .038       0 119.492      .1       0
#XS Ineff= 3 ,-1
      89   93.71  96.626   115.6   119.5   96.64  138.33  570.39108.0033
Permanent Ineff=
       T       T       T
#Block Obstruct= 6 ,-1
  161.67  180.62  106.16  193.39  224.67  104.03  234.36  301.32  107.92
  325.99  374.63106.6167  380.97  412.07  107.81   447.4  504.14108.3733
Bank Sta=89.081,119.253
XS Rating Curve= 0 ,0
Exp/Cntr=0.5,0.3

Type RM Length L Ch R = 1 ,3563.788,147.465,147.645,147.825
XS GIS Cut Line= 4
  527198.8979335 4780750.5713635  527306.5564835 4780894.4077791
  527325.7236663  4781038.117126         527425.        4781273.
#Sta/Elev= 30
       0 129.914   5.674 128.313   9.025 126.728  19.548 121.196   22.73 118.697
  26.318 118.297  31.497 115.781  42.822 111.681   57.11  99.981  62.825  98.851
  64.968  97.887  71.944  97.011    72.6   96.22  73.064   95.68  76.203   91.95
  81.433  90.842  86.219  90.749  95.769   91.97   97.46    96.2 245.319  96.423
 249.479    95.9 255.852  96.509 298.945  96.871 309.995  96.149 338.684 96.1022
347.6737 97.1116455.5496 97.5276564.4247 98.7245573.4146 99.4904579.4075101.1212
#Mann= 3 ,-1 , 0
       0      .1       0  73.064    .038       0   97.46      .1       0
#XS Ineff= 1 ,-1
  122.91  480.62  111.49
Permanent Ineff=
       T
#Block Obstruct= 1 ,-1
  343.79  447.49  109.95
Bank Sta=72.6,97.46
XS Rating Curve= 0 ,0
Exp/Cntr=0.3,0.1

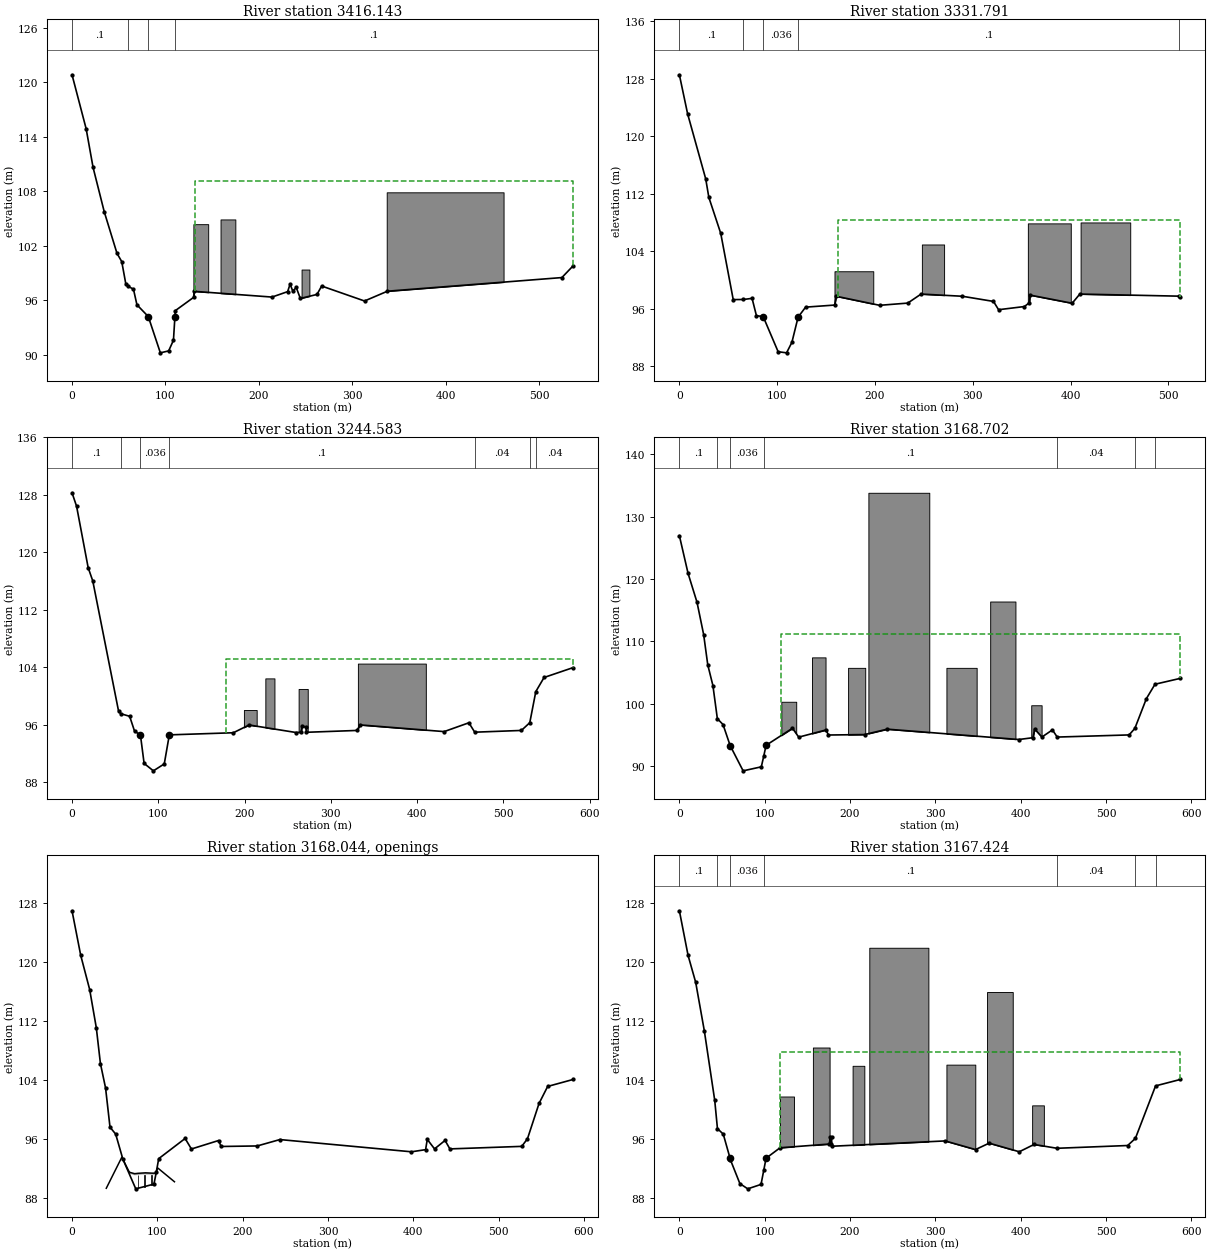
Type RM Length L Ch R = 1 ,3416.143,84.397,84.352,84.307
XS GIS Cut Line= 3
527087.4717885614780843.41801123527347.4583944674781201.07709951
527402.921119026 4781277.3762128
#Sta/Elev= 30
       0 120.802  15.111 114.868  22.552 110.603  34.523 105.723   48.13 101.165
  53.232 100.254  57.645  97.772  59.649  97.563  65.799  97.213  69.508    95.5
  81.669  94.206  94.585  90.216 103.475  90.429 108.613  91.604  110.19    94.2
 110.579  94.856 130.086  96.309  130.94  96.981 214.153  96.351 230.891  96.948
  233.51  97.772 236.406  97.007 240.115  97.404 244.494  96.201 262.337  96.639
 267.313  97.566 313.219  95.919 337.782  96.996524.5602  98.495536.4965 99.7756
#Mann= 4 ,-1 , 0
       0      .1       0  59.649      .1       0  81.669    .038       0
 110.579      .1       0
#XS Ineff= 2 , 0
                          132.16          109.13
Permanent Ineff=
       T       T
#Block Obstruct= 4 ,-1
  129.96  145.81  104.37  159.03  174.89  104.89  245.81  254.19   99.38
     337  462.12107.8733
Bank Sta=81.669,110.19
XS Rating Curve= 0 ,0
Exp/Cntr=0.3,0.1

Type RM Length L Ch R = 1 ,3331.791,87.289,87.208,87.128
XS GIS Cut Line= 3
527016.1031661754780889.21108906527247.2811944674781205.10759951
527344.6003944674781276.63139951
#Sta/Elev= 30
       0 128.574   8.433 123.125  26.926 114.071  30.123 111.493  42.287 106.482
  55.057  97.249  65.463  97.265  74.324  97.425  78.779  95.013  85.696   94.88
 100.969  89.989 109.595  89.833 115.045  91.296 121.398  94.811 129.064  96.201
 158.756  96.489 160.387  97.715 204.759  96.455 233.498  96.764 247.129  98.023
 289.261  97.717 321.162  96.997 326.354  95.842 352.723  96.283 357.838  96.813
 358.553  97.878 401.596  96.742 409.434  98.022 510.741   97.73 512.227  97.644
#Mann= 5 ,-1 , 0
       0      .1       0  65.463      .1       0  85.696    .036       0
 121.398      .1       0 510.741     .04       0
#XS Ineff= 2 , 0
                          162.29          108.33
Permanent Ineff=
       T       T
#Block Obstruct= 4 ,-1
  158.59  198.24   101.2  247.93  270.66  104.93   356.3  400.18  107.87
  410.22  460.97     108
Bank Sta=85.696,121.398
XS Rating Curve= 0 ,0
Exp/Cntr=0.3,0.1

Type RM Length L Ch R = 1 ,3244.583,75.861,75.881,75.901
XS GIS Cut Line= 3
526950.633458688 4780948.3256177527158.1696062024781228.55804287
527324.667532456 4781390.3658867
#Sta/Elev= 30
       0 128.304   5.272 126.433  18.714 117.876  24.035 116.042    53.9  97.949
  56.576  97.549  66.811  97.193  72.482  95.125  79.307    94.6  83.573  90.635
  94.325  89.601 106.951  90.565 112.808  94.608 187.015  94.902 205.223  95.984
 259.922  94.933 265.712  94.979 266.688  95.881 271.278  95.665 271.666  94.967
 330.292  95.223  334.19  95.992 431.431  95.063 460.122  96.289 466.916  94.981
 521.029  95.224 530.755  96.304 537.726  100.63 547.327 102.596 580.885 103.966
#Mann= 7 ,-1 , 0
       0      .1       0  56.576      .1       0  79.307    .036       0
 112.808      .1       0 466.916     .04       0 530.755     .04       0
 537.726     .04       0
#XS Ineff= 2 , 0
                          178.68           105.2
Permanent Ineff=
       T       T
#Block Obstruct= 4 ,-1
   199.3   214.1   98.07  224.14  234.71  102.47  262.73   273.3     101
  331.45  410.22  104.53
Bank Sta=79.307,112.808
XS Rating Curve= 0 ,0
Exp/Cntr=0.5,0.3

Type RM Length L Ch R = 1 ,3168.702,1.278,1.278,1.278
XS GIS Cut Line= 4
526896.8672171824781003.01722286526984.490908935 4781121.6868449
527132.9835545024781279.36567352527301.1669791294781425.78418438
#Sta/Elev= 30
       0  126.96  10.185 120.911  20.665 116.281  28.458  111.09  33.271 106.239
  39.311 102.914  44.502  97.606  51.147  96.666   59.55   93.28  74.693   89.24
  96.019  89.883  98.808  91.551 101.579  93.335  132.54  96.072 139.883  94.645
 171.733  95.795 174.746  94.986 217.008  95.058 243.606  95.924 397.757  94.265
 414.339  94.555 416.308  95.945 424.816  94.658 437.159  95.808 442.788  94.657
 527.012  95.001  533.73  96.037 547.282 100.826  557.39 103.132 587.097 104.074
#Mann= 7 ,-1 , 0
       0      .1       0  44.502      .1       0   59.55    .036       0
  98.808      .1       0 442.788     .04       0  533.73     .04       0
  557.39     .04       0
#XS Ineff= 2 , 0
                          119.47          111.12
Permanent Ineff=
       T       T
#Block Obstruct= 7 ,-1
  119.47  136.92  100.32  155.42  171.28  107.44  197.71   217.8  105.76
   221.5  292.86  133.84  312.95  348.37  105.76  364.23  393.83   116.4
  412.33  424.49   99.76
Bank Sta=59.55,101.579
XS Rating Curve= 0 ,0
Exp/Cntr=0.5,0.3

Type RM Length L Ch R = 4 ,3168.044,,,
BEGIN DESCRIPTION:
E52
END DESCRIPTION:
Bridge Culvert--1,0,-1,-1, 0
Deck Dist Width WeirC Skew NumUp NumDn MinLoCord MaxHiCord MaxSubmerge Is_Ogee
0.01,1.08,1.44,0, 25, 25, , , 0.95, 0, ,,,
  40.141  40.953  58.368  66.603  67.255  67.542  67.544   70.54  71.443  73.345
  73.523  77.259  82.822  86.087  91.657  93.929  97.417  97.586  97.638  97.894
  98.467  98.845  100.36 119.893 120.042
  89.319  89.507  93.531  91.628  91.528  91.483  91.483  91.386  91.356  91.294
  91.297  91.347  91.387  91.411   91.38  91.367  91.368  91.368  91.365  91.349
  91.483  91.572  92.078  90.214  90.199
  89.319  22.566  22.639  22.673  22.676  91.271  91.271  91.174  91.144  91.082
  91.077   91.12  91.184  91.177  91.166  91.155  91.137  38.144  21.976  21.976
  21.974  21.974   21.97  21.927  90.199
  40.435  41.247  58.662  66.897  67.549  67.836  67.838  70.834  71.737  73.639
  73.817  77.553  83.116  86.381  91.951  94.223  97.711   97.88  97.932  98.188
  98.761  99.139 100.654 120.187 120.336
  89.319  89.507  93.531  91.628  91.528  91.483  91.483  91.386  91.356  91.294
  91.297  91.347  91.387  91.411   91.38  91.367  91.368  91.368  91.365  91.349
  91.483  91.572  92.078  90.214  90.199
  89.319  22.566  22.639  22.673  22.676  91.271  91.271  91.174  91.144  91.082
  91.077   91.12  91.184  91.177  91.166  91.155  91.137  38.144  21.976  21.976
  21.974  21.974   21.97  21.927  90.199
Pier Skew, UpSta & Num, DnSta & Num=  ,77.29, 2 ,77.59, 2 , 0 , 0 , 0 ,,
     1.1     1.1
      88    91.2
     1.1     1.1
      88    91.2
Pier Skew, UpSta & Num, DnSta & Num=  ,85.04, 2 ,85.34, 2 , 0 , 0 , 0 ,,
     1.1     1.1
      88    91.2
     1.1     1.1
      88    91.2
Pier Skew, UpSta & Num, DnSta & Num=  ,93.64, 2 ,93.94, 2 , 0 , 0 , 0 ,,
     1.1     1.1
      88    91.2
     1.1     1.1
      88    91.2
BR Coef=-1 , 1 , 0 ,, 0 ,,,0.8,-1,2,0,
WSPro=,,,, 1 ,,,, 0 ,,,, 0 ,,,,-1 ,-1 ,-1 , 0 , 0 , 0 , 0 , 0
BC Mult= 1 ,0,60,0,63
BC Mult= 3 ,60,99,63,99
BC Mult= 1 ,99,600,99,600
BC Design=,, 0 ,, 0 ,,,,,,
BC Use User HTab Curves=0
BC User HTab FreeFlow(D)= 0

Type RM Length L Ch R = 1 ,3167.424,68.174,69.2,70.226
XS GIS Cut Line= 4
526895.7882872394781003.70778111526983.4119789914781122.37740315
527131.9046245584781280.05623177527300.0880491864781426.47474262
#Sta/Elev= 30
       0 126.932  10.208 120.876  19.094 117.245  29.258 110.649  41.414 101.248
  44.619  97.407  51.425  96.662   59.42   93.38  59.706  93.212  70.908  89.955
  80.138  89.245  95.683  89.845  98.926  91.785  101.58  93.391 118.008  94.812
 175.751  95.314 176.959  96.323  177.21  95.324 178.374  96.238 178.669  95.018
 311.403  95.738 347.054  94.568 363.012  95.437 398.326   94.27  415.64  95.261
 442.495  94.741 525.325  95.117 534.376  96.079 558.036 103.198 587.097  104.07
#Mann= 7 ,-1 , 0
       0      .1       0  44.619      .1       0  59.706    .036       0
  98.926      .1       0 442.495     .04       0 534.376     .04       0
 558.036     .04       0
#XS Ineff= 2 , 0
                          117.89          107.73
Permanent Ineff=
       T       T
#Block Obstruct= 7 ,-1
  117.89  134.27  101.76  156.48  176.04   108.4     203  216.74  105.92
  222.56  291.81  121.92  312.95  346.78  106.08  360.53  390.66  115.92
  413.39  427.14  100.56
Bank Sta=59.42,101.58
XS Rating Curve= 0 ,0
Exp/Cntr=0.5,0.3

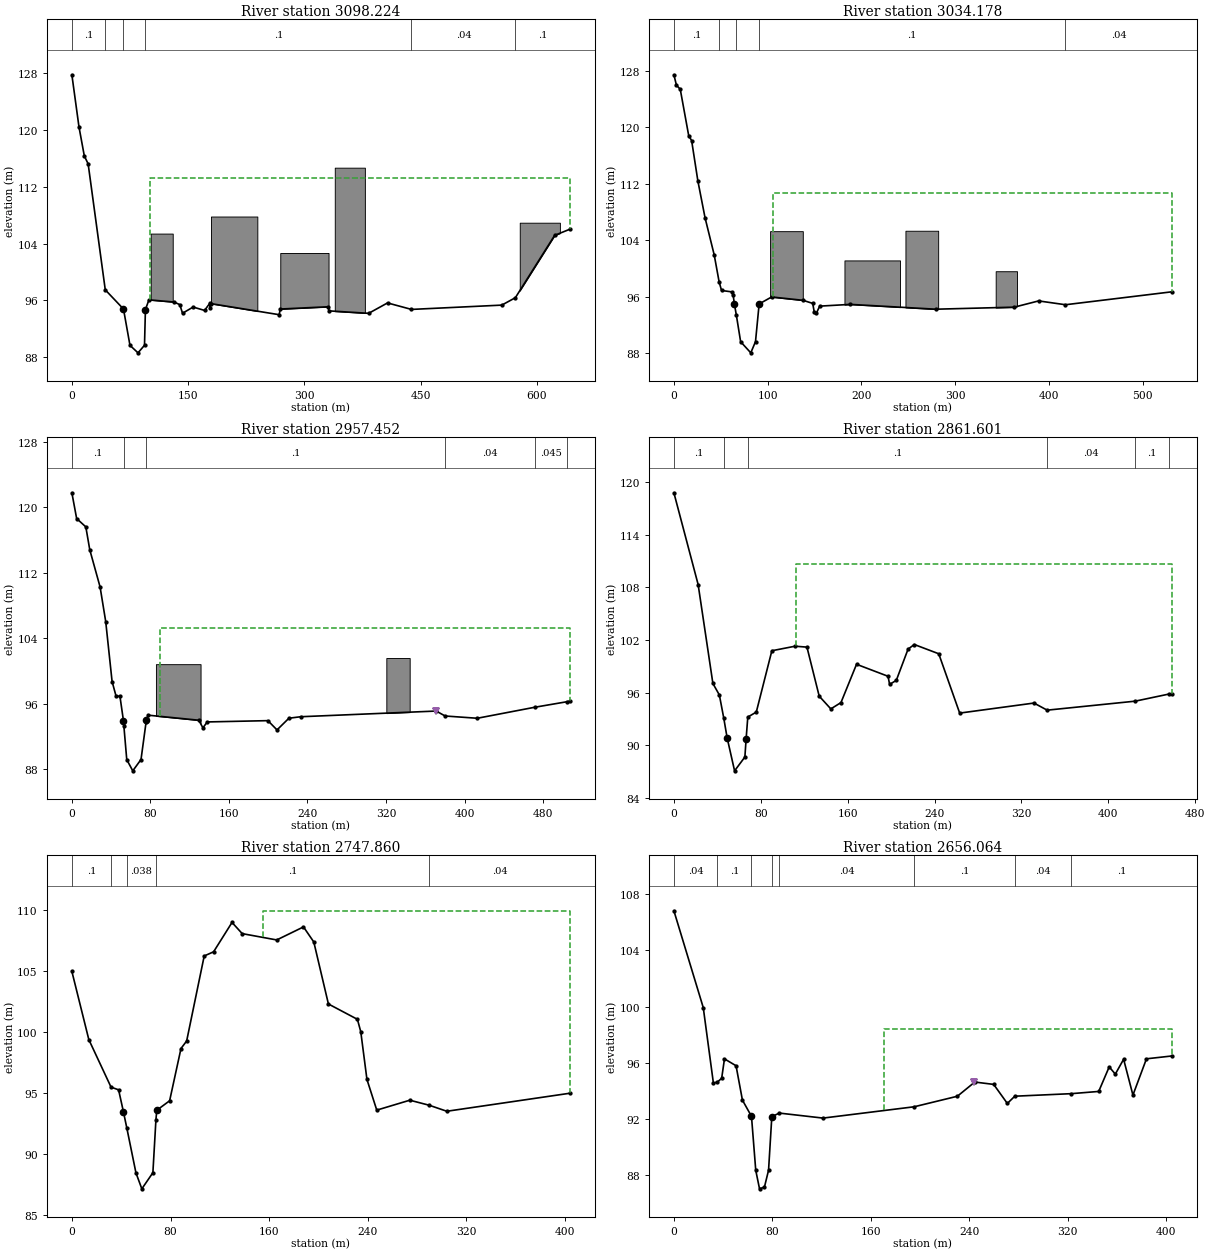
Type RM Length L Ch R = 1 ,3098.224,61.807,64.046,66.286
XS GIS Cut Line= 3
526846.3405470724781042.88925549526985.9100830394781263.63745235
527263.5498944674781524.64389951
#Sta/Elev= 30
       0 127.734   9.171 120.406  16.078 116.313  21.002 115.207  43.094  97.488
  66.601  94.789  74.978   89.68  85.335  88.627  93.717   89.69   94.91   94.71
  99.434  96.081 131.793  95.773 139.249  95.408  142.79  94.194 156.444  95.066
 171.192  94.593 177.981  95.598 178.356  94.999 179.539  95.547 267.477  93.992
 268.856  94.787 330.977  95.108 331.635  94.529  382.96  94.185  407.27  95.646
 438.195  94.734 554.695  95.339 572.229   96.38 622.908 105.151 642.232 105.998
#Mann= 6 ,-1 , 0
       0      .1       0  43.094      .1       0  66.601    .036       0
   94.91      .1       0 438.195     .04       0 572.229      .1       0
#XS Ineff= 2 , 0
                          101.15          113.27
Permanent Ineff=
       T       T
#Block Obstruct= 5 ,-1
  101.76  130.13   105.4  179.47   239.3   107.8   268.9  331.19  102.67
  339.21  378.06  114.67  577.89  629.69  106.93
Bank Sta=66.601,94.91
XS Rating Curve= 0 ,0
Exp/Cntr=0.3,0.1

Type RM Length L Ch R = 1 ,3034.178,82.957,76.725,70.494
XS GIS Cut Line= 3
526802.3584568744781068.14256727 526864.892889274781213.53512259
527085.3267634654781513.70039809
#Sta/Elev= 30
       0 127.405   2.719 125.927   6.783 125.358  15.782 118.797  18.915 118.088
  25.579 112.368    33.2  107.18  42.997 101.904  48.239  98.084  50.802  96.876
  61.503  96.681   63.11  96.281   64.52   94.95  66.616  93.371  71.156  89.622
  81.988  88.048  87.008  89.633  90.894  94.971 104.214  95.956 137.694  95.482
 148.008  95.046 149.677  93.794 151.854  93.647 155.472  94.659 188.178  94.907
 279.153  94.224  362.85  94.513 388.875  95.397 417.487  94.856 530.682  96.683
#Mann= 5 ,-1 , 0
       0      .1       0  48.239      .1       0  66.616    .036       0
  90.894      .1       0 417.487     .04       0
#XS Ineff= 2 , 0
                           105.2          110.67
Permanent Ineff=
       T       T
#Block Obstruct= 4 ,-1
  102.56  137.44  105.27  181.85  241.06  101.13  246.87  281.76  105.33
  343.08  365.81    99.6
Bank Sta=64.52,90.894
XS Rating Curve= 0 ,0
Exp/Cntr=0.3,0.1

Type RM Length L Ch R = 1 ,2957.452,98.059,95.851,93.643
XS GIS Cut Line= 3
 526720.133476264781135.60501596526817.970574571 4781222.4645137
527039.9892944674781526.20729951
#Sta/Elev= 30
       0 121.785   4.864 118.637  14.225 117.615  18.237 114.821  28.744 110.277
  34.479 106.048   40.97  98.721  44.981  96.953  48.993  96.905  52.596  93.894
  52.957  93.315  55.915  89.175  62.048  87.803  70.442  89.188  75.563  93.725
   75.79   93.96  77.658  94.606 129.227  93.989 133.527  93.058 137.896   93.78
  199.71  93.937 208.987  92.804 221.105  94.233 233.145  94.415 371.127   95.11
 380.248  94.505 413.018  94.229 471.317  95.569 504.783  96.258 507.065  96.295
#Mann= 6 ,-1 , 0
       0      .1       0  52.957    .036       0  75.563      .1       0
 380.248     .04       0 471.317    .045       0 504.783     .04       0
Levee=0,,,-1,370.57,95.08,,Levee 16
#XS Ineff= 2 , 0
                           89.87          105.21
Permanent Ineff=
       T       T
#Block Obstruct= 2 ,-1
   85.64   131.1  100.84  320.35  344.14  101.59
Bank Sta=52.596,75.79
XS Rating Curve= 0 ,0
Exp/Cntr=0.3,0.1

Type RM Length L Ch R = 1 ,2861.601,114.512,113.741,112.97
XS GIS Cut Line= 3
526661.6559839834781222.91528745526766.4011582474781290.13980228
527005.5953621614781523.08056295
#Sta/Elev= 30
       0 118.799  22.321 108.328  35.913  97.034  41.862  95.723  45.858  93.122
  49.042  90.821  55.885  87.062  65.373   88.64   66.54   90.75  68.045    93.2
  75.878  93.767  90.212  100.77 111.548 101.286 122.525 101.183 133.804  95.586
  144.52  94.132 153.847  94.853  168.18  99.224 197.209  97.854 198.623   96.93
 204.796  97.386 215.633 100.955 221.367 101.481 243.882 100.425 263.167  93.653
 331.579  94.799  343.71  93.988  424.79  95.014  455.82  95.825 458.341  95.798
#Mann= 6 ,-1 , 0
       0      .1       0  45.858    .036       0  68.045      .1       0
  343.71     .04       0  424.79      .1       0  455.82    .045       0
#XS Ineff= 2 , 0
                          112.33          110.71
Permanent Ineff=
       T       T
Bank Sta=49.042,66.54
XS Rating Curve= 0 ,0
Exp/Cntr=0.3,0.1

Type RM Length L Ch R = 1 ,2747.860,92.681,91.796,90.912
XS GIS Cut Line= 3
526603.8115944674781324.53369951526719.5002944674781390.19489951
526947.7509944674781535.58739951
#Sta/Elev= 30
       0 104.995  13.751  99.398  31.767  95.496  37.897  95.276  41.856  93.453
  44.545  92.152  51.967   88.46  56.736   87.15  65.703  88.475  68.173  92.827
  68.869    93.6  79.269  94.377   88.49  98.666   93.09  99.286 107.322 106.261
 114.937 106.604 129.875 109.012  138.14 108.095 166.135 107.576 187.833 108.646
 196.197 107.408 208.039 102.321 231.558 101.062 234.282 100.044 239.288  96.129
 247.255   93.61 274.054  94.424 289.778  94.011 304.077  93.517 403.647  94.993
#Mann= 5 ,-1 , 0
       0      .1       0  31.767      .1       0  44.545    .038       0
  68.173      .1       0 289.778     .04       0
#XS Ineff= 2 , 0
                          154.63          109.97
Permanent Ineff=
       T       T
Bank Sta=41.856,68.869
XS Rating Curve= 0 ,0
Exp/Cntr=0.3,0.1

Type RM Length L Ch R = 1 ,2656.064,57.256,65.588,73.35
XS GIS Cut Line= 3
526546.7489644564781402.75063561526754.7673718384781504.23668464
526894.108194405 4781606.7692213
#Sta/Elev= 30
       0 106.816  23.864  99.925   32.09  94.558  35.228  94.618  38.821   94.89
  41.097  96.274  50.508  95.785  55.693  93.337  63.047  92.185  66.517  88.338
  69.589  87.023  73.561  87.145  76.923   88.35  79.573  92.166  85.704  92.415
 121.171  92.059 195.229  92.864 230.346  93.614 244.502  94.625 259.847  94.457
 270.944  93.101  277.01  93.617 322.794  93.797 345.183  93.956 353.716  95.705
 358.681  95.189  365.43  96.246 372.996  93.697  383.99  96.279 404.453  96.479
#Mann= 8 ,-1 , 0
       0     .04       0  35.228      .1       0  63.047    .036       0
  79.573      .1       0  85.704     .04       0 195.229      .1       0
  277.01     .04       0 322.794      .1       0
Levee=0,,,-1,244.05,94.6,,Levee 35
#XS Ineff= 2 , 0
                          170.93           98.37
Permanent Ineff=
       T       T
Bank Sta=63.047,79.573
XS Rating Curve= 0 ,0
Exp/Cntr=0.3,0.1

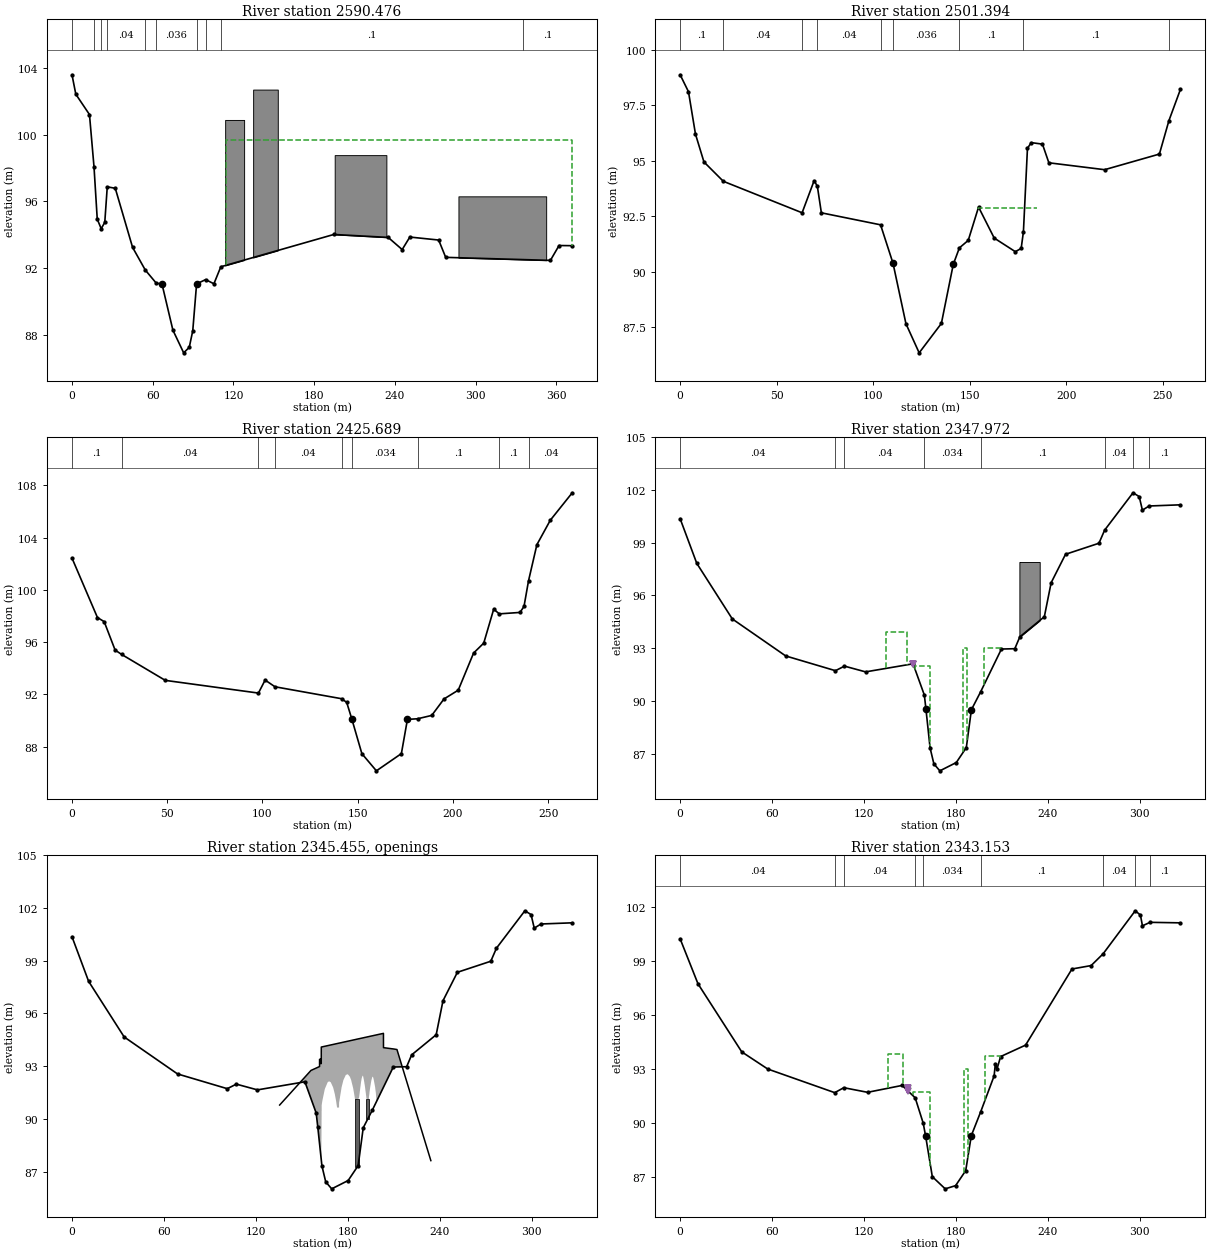
Type RM Length L Ch R = 1 ,2590.476,83.972,89.082,94.762
XS GIS Cut Line= 3
526535.2191944674781423.22089951526610.0650944674781538.17679951
526813.2042944674781655.57539951
#Sta/Elev= 30
       0 103.587   2.844 102.421  12.989 101.203  16.359  98.073  18.771  94.932
  21.713   94.36  24.367  94.742  26.212  96.869  32.168  96.783  45.025  93.241
  54.486   91.88  62.471   91.11  66.954   91.02  74.992  88.279  83.003  86.918
  87.151  87.247  89.759  88.243    92.6   91.05  99.307  91.308 105.479  91.058
  110.61  92.078 194.584  94.014 235.009  93.837 245.403  93.109 251.086  93.859
 272.523   93.68 277.743  92.642 355.564   92.46 361.993  93.352 371.797  93.341
#Mann= 10 ,-1 , 0
       0     .04       0  16.359     .04       0  21.713      .1       0
  26.212     .04       0  54.486      .1       0  62.471    .036       0
    92.6      .1       0  99.307     .04       0  110.61      .1       0
  335.51      .1       0
#XS Ineff= 2 , 0
                          114.19            99.7
Permanent Ineff=
       T       T
#Block Obstruct= 4 ,-1
  113.83  127.93  100.88  134.63  152.95   102.7  195.24  233.66   98.77
  287.22  352.42    96.3
Bank Sta=66.954,92.6
XS Rating Curve= 0 ,0
Exp/Cntr=0.3,0.1

Type RM Length L Ch R = 1 ,2501.394,72.972,75.704,78.436
XS GIS Cut Line= 3
526475.5182944674781399.37959951526512.5843410044781609.87486977
526486.0709944674781646.78149951
#Sta/Elev= 30
       0  98.868   4.327  98.102   7.944  96.192  12.334  94.939  22.367  94.067
  63.187  92.648   69.42  94.097  71.092   93.84  73.165  92.646 103.834  92.105
  110.29   90.37  116.99  87.645 123.834  86.335  135.34  87.659 141.508  90.324
 144.67291.06585 149.259  91.404 154.604  92.904 162.716  91.508 173.651  90.895
  176.68  91.041 177.846  91.792 179.941  95.557 181.919   95.81 187.703  95.742
 191.032  94.901 219.916   94.59 248.292  95.294 253.241  96.805 259.176  98.207
#Mann= 9 ,-1 , 0
       0      .1       0  22.367     .04       0  63.187      .1       0
  71.092     .04       0 103.834      .1       0  110.29    .036       0
 144.672      .1       0 177.846      .1       0 253.241     .04       0
#XS Ineff= 1 ,-1
  154.36  184.76   92.85
Permanent Ineff=
       T
Bank Sta=110.29,141.508
XS Rating Curve= 0 ,0
Exp/Cntr=0.3,0.1

Type RM Length L Ch R = 1 ,2425.689,77.907,77.717,77.528
XS GIS Cut Line= 3
526423.9273944674781371.23909951526422.7548944674781500.21639951
526420.4098944674781633.88379951
#Sta/Elev= 30
       0 102.441  13.368   97.89  16.904  97.576  22.641    95.4  26.031  95.069
  48.992   93.08  97.897  92.108 101.406  93.104 106.592   92.59   141.6  91.675
  144.25  91.392 146.966  90.106 152.212   87.47 159.835  86.155 172.955  87.474
 176.128  90.094 181.447  90.141 188.884  90.397 195.328  91.657 202.806   92.33
 210.873  95.173 216.194  95.932 221.422  98.528 224.373  98.172 235.244  98.281
 237.341   98.74 239.713 100.705 244.103 103.467 251.146 105.339 262.671 107.441
#Mann= 9 ,-1 , 0
       0      .1       0  26.031     .04       0  97.897      .1       0
 106.592     .04       0   141.6      .1       0 146.966    .034       0
 181.447      .1       0 224.373      .1       0 239.713     .04       0
Bank Sta=146.966,176.128
XS Rating Curve= 0 ,0
Exp/Cntr=0.5,0.3

Type RM Length L Ch R = 1 ,2347.972,4.819,4.819,4.819
XS GIS Cut Line= 3
526360.6113180274781361.85897943526344.7150975484781500.46345615
526343.7932734294781687.44182794
#Sta/Elev= 30
       0 100.362  10.853  97.823  34.042  94.659   68.89  92.553 101.344  91.714
 107.253  91.973 121.033  91.646 152.015  92.106 159.383  90.326  160.43   89.52
 163.116  87.321   165.6  86.411   169.5  86.014 180.235  86.487 186.776  87.338
 190.085  89.491 196.027  90.496 209.691  92.946 218.414  92.965 221.692  93.639
 237.692  94.784  242.13  96.719 251.524  98.338 273.334  98.967  277.03  99.711
 295.575 101.839 299.615 101.622 301.692 100.851 306.088 101.087 326.494 101.154
#Mann= 8 ,-1 , 0
       0     .04       0 101.344      .1       0 107.253     .04       0
 159.383    .034       0 196.027      .1       0  277.03     .04       0
 295.575     .04       0 306.088      .1       0
Levee=-1,152.03,92.12,0,,,Levee 36,
#XS Ineff= 4 ,-1
  134.14  148.02   93.91   153.4  162.97      92  198.32   209.7      93
   184.8  187.31      93
Permanent Ineff=
       T       T       T       T
#Block Obstruct= 1 ,-1
  221.41  234.67    97.9
Bank Sta=160.43,190.085
XS Rating Curve= 0 ,0
Exp/Cntr=0.5,0.3

Type RM Length L Ch R = 4 ,2345.455,,,
BEGIN DESCRIPTION:
E53
END DESCRIPTION:
Bridge Culvert--1,0,-1,-1, 0
Deck Dist Width WeirC Skew NumUp NumDn MinLoCord MaxHiCord MaxSubmerge Is_Ogee
0.01,4.62,1.44,0, 63, 63, , , 0.95, 0, ,,,
 135.542 136.052 155.966 161.574 161.579 162.407 162.418 162.524 162.687 162.698
 162.971 163.394 165.005 166.873 167.762 168.895 170.462 171.509 172.354 173.004
 174.305 174.322 175.993 177.165 178.729 180.002  181.35 182.158  183.08 183.501
 184.529 184.802 187.306 187.661 188.152 188.642 189.088 189.459 189.768  190.04
 190.502 191.108 191.511 192.218 193.801 193.807 194.599 195.346 195.979  196.22
 196.303  196.57 197.057 197.569 197.815 198.323 198.745 203.276 203.308 209.914
 212.089 233.725 234.208
  90.784  90.834  92.753  92.975  93.384  93.392  93.139  93.142  93.147  94.084
  94.089  94.098  94.128  94.164  94.181  94.203  94.233  94.253   94.27  94.282
  94.307  94.307  94.339  94.362  94.392  94.416  94.442  94.458  94.475  94.484
  94.503  94.509  94.557  94.563  94.573  94.582  94.591  94.598  94.604  94.609
  94.618   94.63  94.637  94.651  94.681  94.681  94.697  94.711  94.723  94.728
  94.729  94.734  94.744  94.754  94.758  94.768  94.776  94.863  94.049  93.974
  93.943  87.758   87.62
  90.784 -27.506 -27.103 -26.989 -26.989 -26.972 -26.972  -26.97  16.092  18.901
  90.784  91.022  91.695  92.082  92.134  92.079  91.777  91.416  91.019  90.641
  90.641   90.91  91.809   92.21  92.497  92.537  92.395  92.214  91.891  91.743
  91.218   91.05  91.164  91.412  91.752  92.085  92.306  92.409  92.462  92.411
  92.208  91.893  91.629  91.135  91.128  91.243   91.78   92.17  92.373  92.399
  92.398  92.356  92.171  91.928  91.812  91.467 -25.541 -25.505 -25.505 -25.452
 -25.435 -25.262   87.62
 135.958 136.468 156.382  161.99 161.995 162.823 162.834  162.94 163.103 163.114
 163.387  163.81 165.421 167.289 168.178 169.311 170.878 171.925  172.77  173.42
 174.721 174.738 176.409 177.581 179.145 180.418 181.766 182.574 183.496 183.917
 184.945 185.218 187.722 188.077 188.568 189.058 189.504 189.875 190.184 190.456
 190.918 191.524 191.927 192.634 194.217 194.223 195.015 195.762 196.395 196.636
 196.719 196.986 197.473 197.985 198.231 198.739 199.161 203.692 203.724  210.33
 212.505 234.141 234.624
  90.784  90.834  92.753  92.975  93.384  93.392  93.139  93.142  93.147  94.084
  94.089  94.098  94.128  94.164  94.181  94.203  94.233  94.253   94.27  94.282
  94.307  94.307  94.339  94.362  94.392  94.416  94.442  94.458  94.475  94.484
  94.503  94.509  94.557  94.563  94.573  94.582  94.591  94.598  94.604  94.609
  94.618   94.63  94.637  94.651  94.681  94.681  94.697  94.711  94.723  94.728
  94.729  94.734  94.744  94.754  94.758  94.768  94.776  94.863  94.049  93.974
  93.943  87.758   87.62
  90.784 -27.506 -27.103 -26.989 -26.989 -26.972 -26.972  -26.97  16.092  18.901
  90.784  91.022  91.695  92.082  92.134  92.079  91.777  91.416  91.019  90.641
  90.641   90.91  91.809   92.21  92.497  92.537  92.395  92.214  91.891  91.743
  91.218   91.05  91.164  91.412  91.752  92.085  92.306  92.409  92.462  92.411
  92.208  91.893  91.629  91.135  91.128  91.243   91.78   92.17  92.373  92.399
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Pier Skew, UpSta & Num, DnSta & Num=  ,173.65, 2 ,174.06, 2 , 0 , 0 , 0 ,,
     1.3     1.3
      85      94
     1.3     1.3
      85      94
Pier Skew, UpSta & Num, DnSta & Num=  ,186.08, 2 ,186.49, 2 , 0 , 0 , 0 ,,
     2.5     2.5
      85      94
     2.5     2.5
      85      94
Pier Skew, UpSta & Num, DnSta & Num=  ,193.01, 2 ,193.42, 2 , 0 , 0 , 0 ,,
     1.6     1.6
      85      94
     1.6     1.6
      85      94
BR Coef=-1 , 1 , 0 ,, 0 ,,,0.8,-1,1.33,0,
WSPro=,,,, 1 ,,,, 0 ,,,, 0 ,,,,-1 ,-1 ,-1 , 0 , 0 , 0 , 0 , 0
BC Mult= 1 ,0,153,0,149
BC Mult= 3 ,153,218,149,208
BC Mult= 1 ,218,350,208,350
BC Design=,, 0 ,, 0 ,,,,,,
BC Use User HTab Curves=0
BC User HTab FreeFlow(D)= 0

Type RM Length L Ch R = 1 ,2343.153,79.811,80.443,81.075
XS GIS Cut Line= 3
 526355.796457114781361.82385121 526339.900236634781500.42832793
526338.9784125114781687.40669972
#Sta/Elev= 30
       0 100.252  11.661  97.743  40.218  93.949  57.189  92.993 100.887  91.676
 106.796  91.952  122.34  91.695  144.88  92.079 153.402  91.388 158.646  89.972
  160.24   89.24 164.579  86.991 172.992  86.313 179.767  86.491 186.381   87.33
 190.019  89.278 196.223  90.624 204.919   92.61 205.726  93.294 206.727  92.977
 209.155  93.688 225.433  94.326 255.727  98.571 268.226  98.762 276.051  99.418
 297.012 101.817 300.396 101.578 301.728 100.979 306.676 101.173 326.494 101.144
#Mann= 9 ,-1 , 0
       0     .04       0 100.887      .1       0 106.796     .04       0
 153.402      .1       0 158.646    .034       0 196.223      .1       0
 276.051     .04       0 297.012     .04       0 306.676      .1       0
Levee=-1,148.94,91.93,0,,,Levee 36,
#XS Ineff= 4 ,-1
  135.37  145.24   93.81   151.7  163.39    91.7   198.9   208.5    93.7
  185.22  187.72      93
Permanent Ineff=
       T       T       T       T
Bank Sta=160.24,190.019
XS Rating Curve= 0 ,0
Exp/Cntr=0.5,0.3