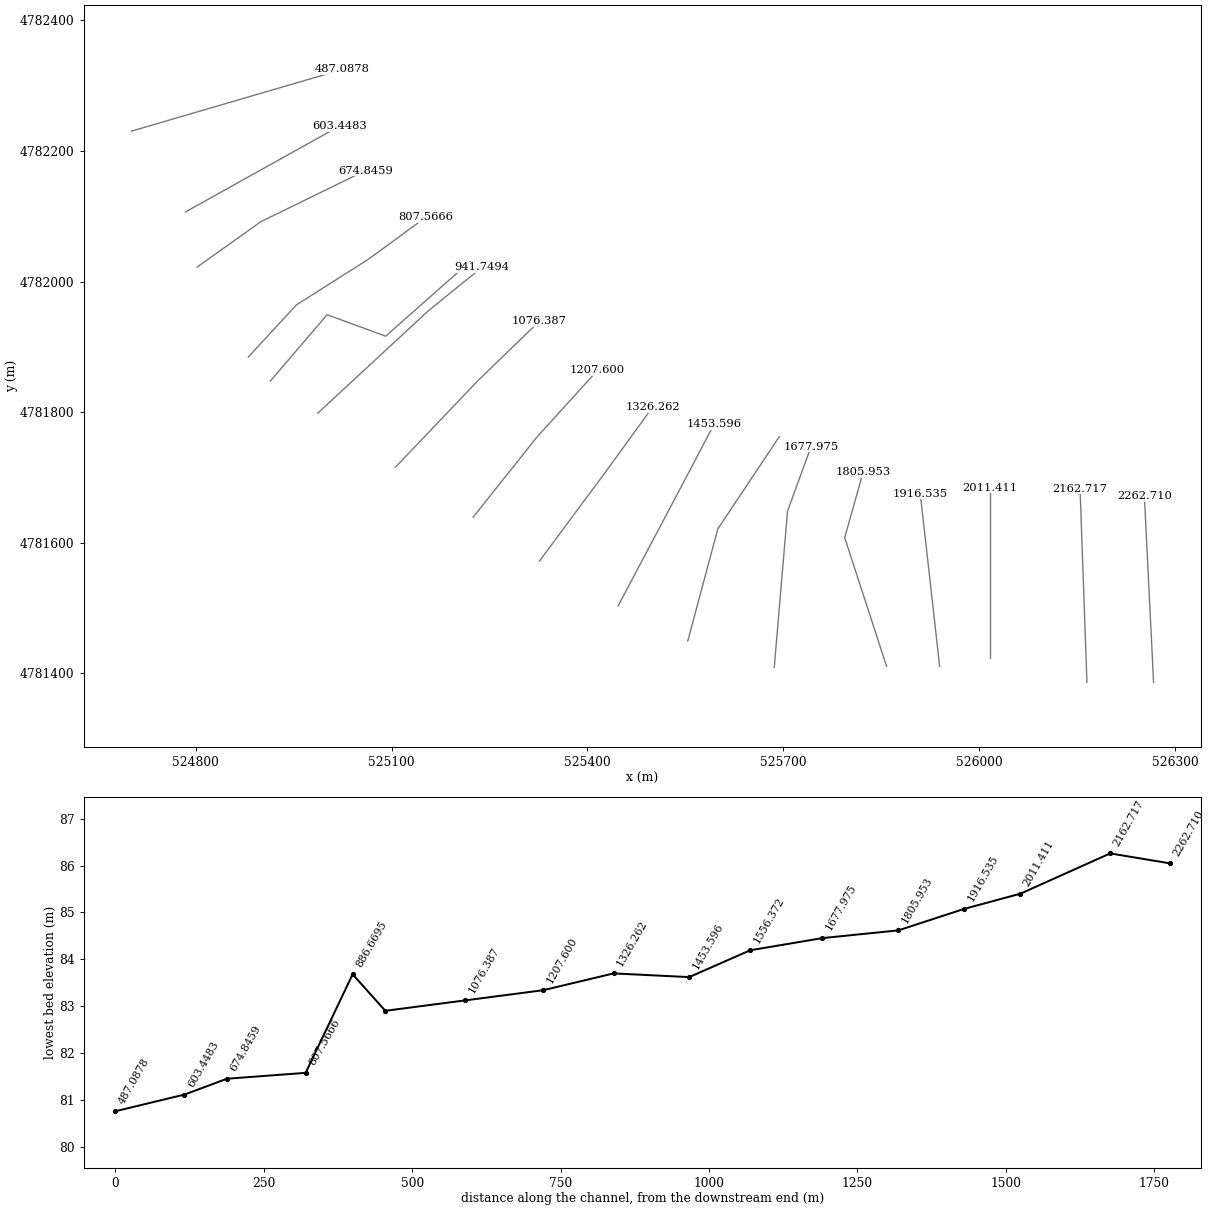
HEC-RAS study Durango.prj: Durango

--- Durango.g18 (geometry) --- (continued)

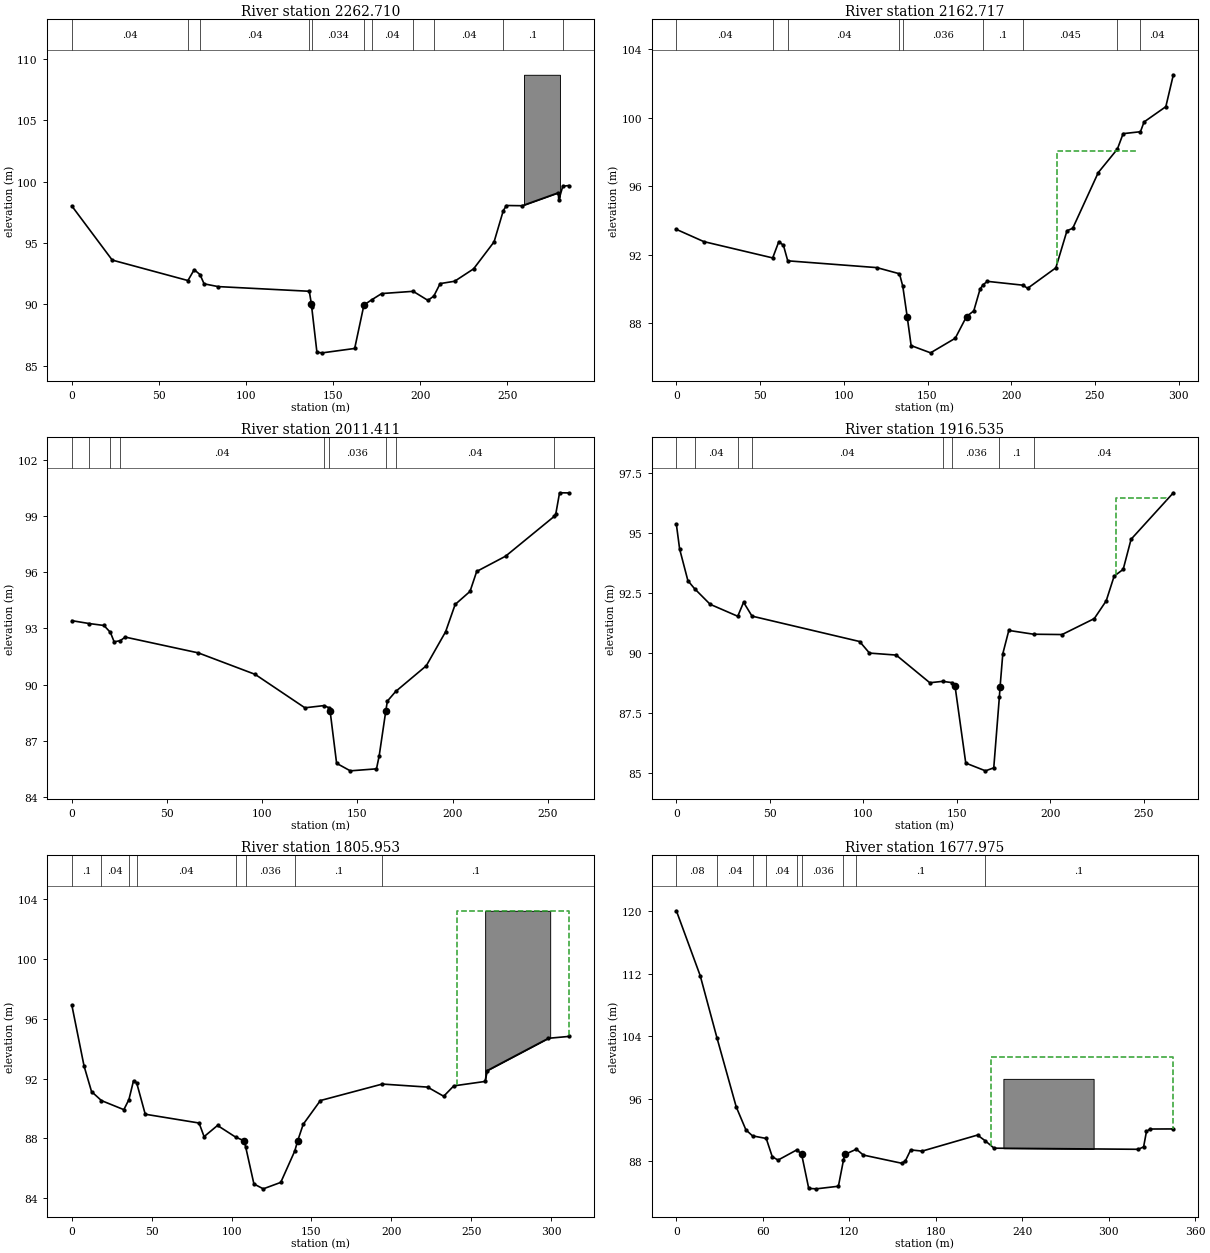
Type RM Length L Ch R = 1 ,2262.710,100.189,99.993,99.798
XS GIS Cut Line= 2
526266.8096944674781386.48189951526252.7393944674781671.40439951
#Sta/Elev= 30
       0  98.014  23.187  93.607  66.639   91.94  70.245  92.825  73.599  92.421
   75.91  91.672  83.954  91.447 136.302  91.066  137.56   89.99 137.704  89.768
 140.696  86.088 143.861  86.051 162.357  86.408 167.676  89.951 172.038  90.362
 177.843  90.879 195.923  91.062 204.408  90.324  207.79  90.676 211.416  91.691
 219.729  91.882 230.608  92.891  242.37   95.09 247.671  97.635 249.463  98.052
 258.474  98.034 279.233  99.089 279.499   98.47 281.789  99.616 285.269  99.681
#Mann= 11 ,-1 , 0
       0     .04       0  66.639      .1       0  73.599     .04       0
 136.302      .1       0 137.704    .034       0 167.676      .1       0
 172.038     .04       0 195.923    .045       0  207.79     .04       0
 247.671      .1       0 281.789     .04       0
#Block Obstruct= 1 ,-1
  259.56  280.18   108.7
Bank Sta=137.56,167.676
XS Rating Curve= 0 ,0
Exp/Cntr=0.3,0.1

Type RM Length L Ch R = 1 ,2162.717,151.76,151.305,150.851
XS GIS Cut Line= 2
526164.8003765884781386.48191218526154.2476911214781683.12962586
#Sta/Elev= 30
       0   93.47   16.41  92.755  57.527  91.803  61.198  92.758  63.955  92.537
  66.521  91.634 119.763  91.237  133.25  90.878 135.244  90.144  137.89   88.35
 140.214  86.685 151.826  86.262 166.563  87.113 173.288  88.379 177.628  88.712
 181.433  89.998 183.275   90.24 185.703  90.436 207.043  90.211 209.768  90.027
 226.645  91.224 233.307   93.39 236.744  93.535 251.991  96.787 263.382  98.154
 266.842  99.058 277.185  99.171 279.336  99.741 292.344 100.633 296.836 102.495
#Mann= 9 ,-1 , 0
       0     .04       0  57.527      .1       0  66.521     .04       0
  133.25      .1       0 135.244    .036       0 183.275      .1       0
 207.043    .045       0 263.382      .1       0 277.185     .04       0
#XS Ineff= 1 ,-1
  227.31  274.63   98.02
Permanent Ineff=
       T
Bank Sta=137.89,173.288
XS Rating Curve= 0 ,0
Exp/Cntr=0.3,0.1

Type RM Length L Ch R = 1 ,2011.411,93.287,94.877,96.467
XS GIS Cut Line= 2
526015.8902594454781423.41631132526015.8902594454781684.49756657
#Sta/Elev= 30
       0  93.418   9.086  93.265  16.865  93.161   20.26  92.792  22.225  92.289
  25.403  92.349  28.064  92.541  66.437  91.698  96.305  90.551 122.445  88.766
 132.447  88.884  134.84   88.78 135.675    88.6 139.097  85.803  146.29  85.401
 160.049  85.508 161.452   86.19  164.97   88.62 165.765  89.123 170.147   89.64
 186.225  91.011 196.372  92.829 201.372  94.282 209.195  94.982 212.695  96.046
 227.868   96.86 253.563  98.997 254.225  99.102 256.225 100.245 261.082 100.238
#Mann= 9 ,-1 , 0
       0      .1       0   9.086     .04       0   20.26      .1       0
  25.403     .04       0 132.447      .1       0  134.84    .036       0
  164.97      .1       0 170.147     .04       0 253.563      .1       0
Bank Sta=135.675,164.97
XS Rating Curve= 0 ,0
Exp/Cntr=0.3,0.1

Type RM Length L Ch R = 1 ,1916.535,107.692,110.582,113.473
XS GIS Cut Line= 2
525939.2855944674781410.90939951525909.5816944674781675.11739951
#Sta/Elev= 30
       0  95.346   1.743  94.318   6.162      93   9.731  92.667   18.06  92.016
  32.835  91.517  35.957    92.1  40.466  91.523  98.033  90.465   103.3  89.983
 117.597    89.9 135.581  88.747 142.401  88.805 147.636   88.75 149.074   88.61
 154.817  85.399 165.361  85.076 169.795  85.201 172.814  88.171  173.15   88.55
 174.628  89.955 177.846  90.927 191.083  90.769 206.332  90.755 223.571   91.42
 229.956   92.16 234.198   93.19 239.038  93.472 243.255  94.726 265.873  96.663
#Mann= 8 ,-1 , 0
       0     .08       0   9.731     .04       0  32.835      .1       0
  40.466     .04       0 142.401      .1       0 147.636    .036       0
 172.814      .1       0 191.083     .04       0
#XS Ineff= 1 ,-1
  234.98  261.94   96.45
Permanent Ineff=
       T
Bank Sta=149.074,173.15
XS Rating Curve= 0 ,0
Exp/Cntr=0.3,0.1

Type RM Length L Ch R = 1 ,1805.953,133.654,127.977,122.301
XS GIS Cut Line= 3
525857.9907944674781410.90939951525793.8929944674781607.89289951
525822.0334944674781707.94799951
#Sta/Elev= 30
       0  96.917   7.659  92.837  12.338  91.128  18.541  90.525  32.562  89.918
  35.744  90.594  38.628  91.859  40.597  91.709  45.955  89.612  79.641  89.024
  82.795  88.112  91.201  88.861 102.472  88.084 107.799  87.835 108.844  87.413
 113.982  84.944 119.844  84.618 130.781   85.05 139.536  87.146  141.33   87.82
  144.84   88.94 155.584  90.528 194.336  91.631 222.665  91.428 232.768  90.815
 239.091   91.51 258.678  91.807 259.867  92.525 298.303  94.695 311.087  94.819
#Mann= 8 ,-1 , 0
       0      .1       0  18.541     .04       0  35.744      .1       0
  40.597     .04       0 102.472      .1       0 108.844    .036       0
 139.536      .1       0 194.336      .1       0
#XS Ineff= 1 ,-1
  241.15  311.45  103.23
Permanent Ineff=
       T
#Block Obstruct= 1 ,-1
  258.72  299.43  103.23
Bank Sta=107.799,141.33
XS Rating Curve= 0 ,0
Exp/Cntr=0.3,0.1

Type RM Length L Ch R = 1 ,1677.975,124.118,121.603,119.089
XS GIS Cut Line= 3
525686.0210944674781409.34609951525706.3447944674781648.54029951
525742.3020944674781747.03199951
#Sta/Elev= 30
       0 120.071  16.529 111.764  28.179 103.789   41.56  94.937  48.266  92.004
   52.84  91.238  62.359  90.906  66.534  88.572  70.548  88.134  83.595  89.445
  86.911   88.89  91.857  84.508  97.091  84.453 112.445  84.785 115.946  88.109
  116.92  88.861 124.925  89.529 129.761   88.78 156.342  87.733 158.865  88.011
 162.624  89.439 170.602  89.288 208.989   91.34 214.256  90.619 220.503   89.66
 320.583  89.518 324.263   89.83 326.251  91.807 328.778  92.115 344.906  92.126
#Mann= 9 ,-1 , 0
       0     .08       0  28.179     .04       0   52.84      .1       0
  62.359     .04       0  83.595      .1       0  86.911    .036       0
 115.946      .1       0 124.925      .1       0 214.256      .1       0
#XS Ineff= 2 , 0
                          218.33           101.3
Permanent Ineff=
       T       T
#Block Obstruct= 1 ,-1
  226.96  289.56   98.54
Bank Sta=86.911,116.92
XS Rating Curve= 0 ,0
Exp/Cntr=0.3,0.1

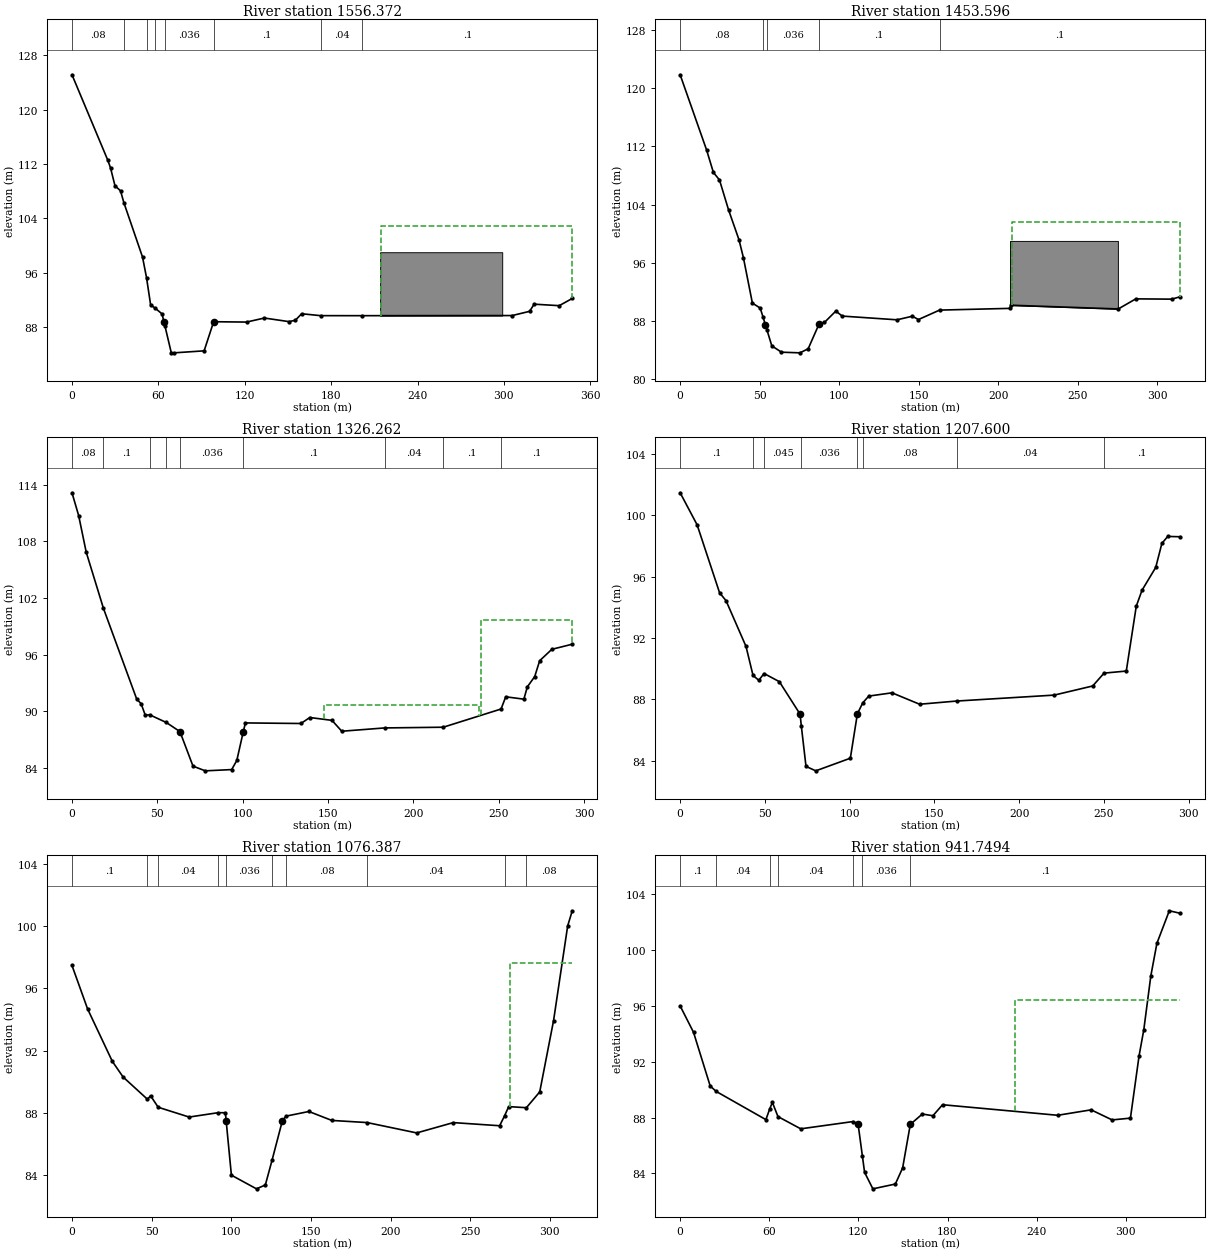
Type RM Length L Ch R = 1 ,1556.372,105.957,102.776,99.596
XS GIS Cut Line= 3
525553.6217712824781449.78873632525599.5740258524781621.15635281
525693.8379326064781762.66560706
#Sta/Elev= 30
       0 125.114  24.844 112.551  26.765  111.41  29.871 108.772  33.711 108.039
  36.031 106.294  48.985  98.293   51.77  95.255   54.63  91.235   57.99  90.729
  62.573  89.918   63.85   88.75  64.497  88.202  68.954   84.21  70.985  84.193
  91.777  84.487  98.381  88.764  98.399  88.773 121.241  88.721 133.594  89.315
 150.611   88.79   155.1  88.978 159.504  89.946 172.615  89.666 201.766  89.662
 305.749  89.681 317.819  90.301 320.989  91.354 338.402  91.134 347.453  92.195
#Mann= 8 ,-1 , 0
       0     .08       0  36.031     .04       0   51.77      .1       0
   57.99      .1       0  64.497    .036       0  98.381      .1       0
 172.615     .04       0 201.766      .1       0
#XS Ineff= 2 , 0
                          214.63           102.8
Permanent Ineff=
       T       T
#Block Obstruct= 1 ,-1
  214.01  298.81      99
Bank Sta=63.85,98.399
XS Rating Curve= 0 ,0
Exp/Cntr=0.3,0.1

Type RM Length L Ch R = 1 ,1453.596,129.494,127.333,125.173
XS GIS Cut Line= 3
525446.8268944674781503.14769951525545.3186944674781689.18759951
525593.7827944674781781.42589951
#Sta/Elev= 30
       0 121.826  16.636 111.493  20.925 108.402  24.738 107.382  30.456 103.263
  37.004  99.166  39.779  96.714  45.452  90.447  50.343  89.778  52.083  88.582
  53.591  87.501  54.569  86.799  57.668  84.576  63.754  83.709  75.345   83.62
  80.531  84.175  87.364  87.566  90.758  87.796  97.935  89.357 101.961   88.67
 136.397  88.159 146.068   88.65 149.915  88.195 163.202  89.493   207.5   89.73
 208.101  90.163   275.6   89.65 286.646  91.036 309.293  90.998 314.698  91.338
#Mann= 5 ,-1 , 0
       0     .08       0  52.083      .1       0  54.569    .036       0
  87.364      .1       0 163.202      .1       0
#XS Ineff= 2 , 0
                          208.46          101.53
Permanent Ineff=
       T       T
#Block Obstruct= 1 ,-1
  207.53  275.37      99
Bank Sta=53.591,87.364
XS Rating Curve= 0 ,0
Exp/Cntr=0.3,0.1

Type RM Length L Ch R = 1 ,1326.262,119.161,118.662,118.163
XS GIS Cut Line= 3
525326.4480944674781571.93559951525429.6299944674781711.07469951
525499.9811944674781808.00309951
#Sta/Elev= 30
       0  113.15   3.899  110.74   8.348 106.846  18.429 100.905  37.907  91.295
  40.484   90.81  42.911  89.593  45.472  89.637  55.229  88.821  63.223  87.855
  70.876  84.196  78.066  83.699  93.523  83.832  96.525  84.796  100.28   87.81
 101.564  88.774 134.089  88.713 139.289  89.348 152.283  89.045 158.002  87.894
 183.119  88.244 217.428  88.319 251.298  90.247 254.036  91.541 264.658   91.29
 266.693  92.599 271.004  93.682 273.906  95.362 281.055  96.572 292.991  97.111
#Mann= 9 ,-1 , 0
       0     .08       0  18.429      .1       0  45.472      .1       0
  55.229      .1       0  63.223    .036       0  100.28      .1       0
 183.119     .04       0 217.428      .1       0 251.298      .1       0
#XS Ineff= 2 ,-1
  147.49  238.41   90.69  239.47 292.991   99.65
Permanent Ineff=
       T       T
Bank Sta=63.223,100.28
XS Rating Curve= 0 ,0
Exp/Cntr=0.3,0.1

Type RM Length L Ch R = 1 ,1207.600,132.464,131.213,129.962
XS GIS Cut Line= 3
525224.8296944674781639.16009951525323.3213944674781762.66559951
525415.5596944674781864.28409951
#Sta/Elev= 30
       0 101.481  10.015   99.39  23.274  94.955  27.074  94.443  38.863  91.459
  43.012  89.563  46.419  89.247  49.506   89.69   58.54  89.158  70.786  87.035
  71.495  86.276  74.268   83.63  80.044   83.34 100.434  84.164  104.59   87.06
 107.749  87.774 111.307  88.217 125.009   88.43  141.31  87.685 163.102  87.893
 220.749  88.281 243.463  88.877 250.159  89.715 263.276   89.85 269.162   94.08
 272.556  95.122 280.643  96.611 284.282   98.18 287.741  98.633 295.207  98.612
#Mann= 8 ,-1 , 0
       0      .1       0  43.012      .1       0  49.506    .045       0
  71.495    .036       0  104.59      .1       0 107.749     .08       0
 163.102     .04       0 250.159      .1       0
Bank Sta=70.786,104.59
XS Rating Curve= 0 ,0
Exp/Cntr=0.3,0.1

Type RM Length L Ch R = 1 ,1076.387,135.526,134.638,133.75
XS GIS Cut Line= 3
525106.0142680854781715.76478277525232.6464936874781848.65045161
525326.4481422814781939.32537858
#Sta/Elev= 30
       0  97.466   9.781  94.679  25.325  91.308  32.104  90.302  47.386  88.873
  49.314  89.102  54.106  88.362  73.529  87.733  91.726  88.013  96.286   88.01
  96.767  87.495 100.063      84 115.822  83.123 121.376  83.372 125.567  84.955
 132.077  87.503 134.371  87.792 148.708   88.09   163.1  87.516 185.274  87.379
  216.38  86.714 239.367  87.377 268.436  87.175 271.567  87.819 274.138  88.404
 285.227  88.333 293.613  89.349 302.285  93.923 311.157 100.013 314.023  100.98
#Mann= 10 ,-1 , 0
       0      .1       0  47.386      .1       0  54.106     .04       0
  91.726      .1       0  96.767    .036       0 125.567      .1       0
 134.371     .08       0 185.274     .04       0 271.567      .1       0
 285.227     .08       0
#XS Ineff= 2 , 0
                          274.76            97.6
Permanent Ineff=
       T       T
Bank Sta=96.767,132.077
XS Rating Curve= 0 ,0
Exp/Cntr=0.3,0.1

Type RM Length L Ch R = 1 ,941.7494,81.404,55.08,27.551
XS GIS Cut Line= 3
524987.1988944674781798.62289951525156.0417944674781954.95899951
525238.8998944674782022.18349951
#Sta/Elev= 30
       0  95.981       9  94.095  20.231  90.255  24.317  89.863  57.735  87.849
  60.355  88.632  62.107  89.081  65.845  88.068  81.187  87.192 116.366  87.711
  119.78   87.55 122.664  85.273 124.171   84.08 129.766    82.9 144.892  83.243
 149.794  84.397 154.962  87.509  163.05  88.249 170.186  88.128 176.651  88.915
 254.224   88.16 276.688   88.55 290.828  87.829 303.158  87.956 308.962  92.402
 312.156  94.274 316.898  98.132 320.988 100.459 329.335 102.785 336.805 102.602
#Mann= 7 ,-1 , 0
       0      .1       0  24.317     .04       0  60.355      .1       0
  65.845     .04       0 116.366      .1       0 122.664    .036       0
 154.962      .1       0
#XS Ineff= 2 , 0
                          225.11           96.37
Permanent Ineff=
       T       T
Bank Sta=119.78,154.962
XS Rating Curve= 0 ,0
Exp/Cntr=0.3,0.1

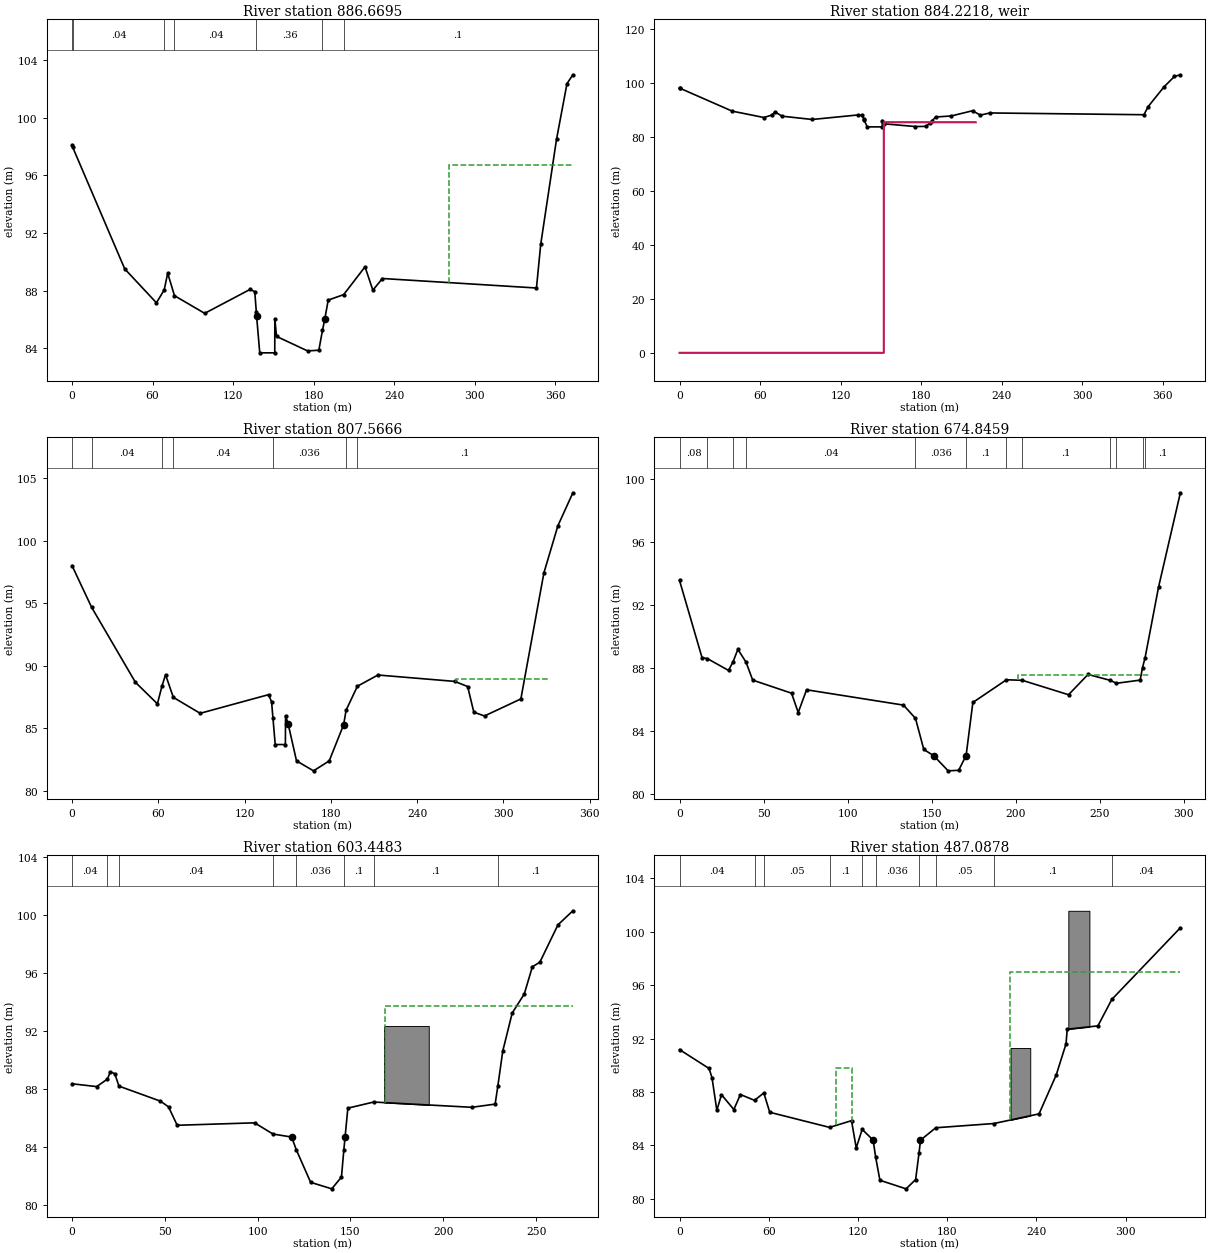
Type RM Length L Ch R = 1 ,886.6695,55.367,79.103,104.043
XS GIS Cut Line= 4
524914.3815920924781847.57505832525001.3192347384781949.22798034
525091.038788929 4781916.3919399525220.0875777554782030.51294408
#Sta/Elev= 30
       0  98.086    .562  97.933  39.247  89.506  62.846  87.152  68.628   88.04
  71.248  89.206  76.298  87.647  98.811   86.42132.5881  88.081136.0961  87.927
 137.277  86.485137.4566  86.241 139.807   83.68150.9899   83.68 151.038  86.038
   152.3   84.82175.4671  83.812183.8173  83.863 186.505  85.231188.2056  86.008
190.7957   87.34202.3056  87.719218.2106  89.649224.0416  88.028231.1696  88.838
345.8916  88.179349.0536  91.209360.8356    98.5368.6136  102.36373.0136 102.974
#Mann= 7 ,-1 , 0
       0      .1       0    .562     .04       0  68.628      .1       0
  76.298     .04       0 137.277     .36       0 186.505      .1       0
202.3056      .1       0
#XS Ineff= 2 , 0
                          280.53            96.7
Permanent Ineff=
       T       T
Bank Sta=137.4566,188.2056
XS Rating Curve= 0 ,0
Exp/Cntr=0.3,0.1

Type RM Length L Ch R = 5 ,884.2218,,,
BEGIN DESCRIPTION:
E194
END DESCRIPTION:
IW Pilot Flow=0
#Inline Weir SE= 9
       0       0  152.17       0  152.19   85.37  155.84   85.37  158.83   85.36
  164.86   85.36  178.47   85.36  196.04   85.36  220.62   85.38
IW Dist,WD,Coef,Skew,MaxSub,Min_El,Is_Ogee,SpillHt,DesHd
0.1,1.85,1.7,0,0.98,, 0 ,,,0,0,

Type RM Length L Ch R = 1 ,807.5666,134.287,132.721,131.154
XS GIS Cut Line= 4
524880.8902944674781884.60779951524954.3682944674781964.33919952
525065.3668944674782034.69039951525152.9150944674782098.78819951
#Sta/Elev= 30
       0  98.001  13.655  94.658  44.093  88.662  59.386  86.939  62.493  88.332
  65.047  89.269   70.47  87.454  89.104  86.179 136.793  87.676 138.811   87.07
 139.721  85.836 141.316   83.68 148.388   83.68 148.501      86  150.35   85.31
  156.13  82.373 167.953  81.575 178.858  82.368 188.942  85.278 190.594  86.427
 198.487  88.348 212.777  89.245 266.147  88.734 275.155  88.325 279.448  86.268
  286.88  85.967  312.17  87.332 328.188  97.421 337.939 101.198 348.345 103.831
#Mann= 7 ,-1 , 0
       0      .1       0  13.655     .04       0  62.493      .1       0
   70.47     .04       0 139.721    .036       0 190.594      .1       0
 198.487      .1       0
#XS Ineff= 1 ,-1
  267.05  332.73    88.9
Permanent Ineff=
       T
Bank Sta=150.35,188.942
XS Rating Curve= 0 ,0
Exp/Cntr=0.3,0.1

Type RM Length L Ch R = 1 ,674.8459,70.638,71.398,72.157
XS GIS Cut Line= 3
524802.2336944674782022.13459951524899.8460944674782091.60649951
525059.8950944674782169.87219951
#Sta/Elev= 30
       0  93.571  13.388  88.659  16.627  88.591  29.147  87.842  31.823  88.382
  34.718  89.182   39.57  88.367  43.539  87.225  66.664  86.391  70.622   85.16
  75.582  86.609 133.236  85.633 140.375  84.791 145.329  82.809 151.241  82.412
 159.806  81.449 166.059  81.483   170.5   82.42 174.517    85.8 194.485  87.245
 203.842  87.214  231.43  86.294 243.053  87.586 256.314  87.208 259.949  87.022
 274.053  87.225 275.444  88.024 276.963  88.642 284.996  93.151  297.97   99.15
#Mann= 12 ,-1 , 0
       0     .08       0  16.627     .04       0  31.823      .1       0
   39.57     .04       0 140.375    .036       0   170.5      .1       0
 194.485     .04       0 203.842      .1       0 256.314     .04       0
 259.949      .1       0 275.444      .1       0 276.963      .1       0
#XS Ineff= 1 ,-1
  201.15  279.38   87.55
Permanent Ineff=
       T
Bank Sta=151.241,170.5
XS Rating Curve= 0 ,0
Exp/Cntr=0.3,0.1

Type RM Length L Ch R = 1 ,603.4483,119.801,116.36,113.013
XS GIS Cut Line= 2
524784.6459116014782106.70269529525020.3225536934782238.02500332
#Sta/Elev= 30
       0  88.347  13.279  88.153  19.074  88.672   20.63  89.174  23.038   89.04
   25.28  88.185  47.607  87.151  51.976  86.759  56.652  85.489  98.328  85.657
 108.269  84.885 118.314  84.678 120.814  83.797 128.532   81.56 139.904  81.111
 145.135  81.921 146.417  83.793 147.074  84.666 148.582  86.668 162.497   87.09
 215.314  86.727 227.917  86.946 229.409  88.224 232.026  90.603  237.11  93.219
 243.612  94.531 247.965  96.404 251.991  96.718 261.755  99.294 269.795 100.262
#Mann= 8 ,-1 , 0
       0     .04       0  19.074      .1       0   25.28     .04       0
 108.269      .1       0 120.814    .036       0 146.417      .1       0
 162.497      .1       0 229.409      .1       0
#XS Ineff= 2 , 0
                          168.63           93.67
Permanent Ineff=
       T       T
#Block Obstruct= 1 ,-1
  168.11  192.16   92.33
Bank Sta=118.314,147.074
XS Rating Curve= 0 ,0
Exp/Cntr=0.3,0.1

Type RM Length L Ch R = 1 ,487.0878,66.925,67.034,67.049
XS GIS Cut Line= 2
524701.6715532634782230.30434442525025.0125944674782324.79149951
#Sta/Elev= 30
       0  91.179  19.898  89.764  21.877  89.061  25.107  86.631  28.232  87.803
  36.537  86.692  40.955  87.816  50.462   87.38  56.694  87.935  60.692  86.486
 100.924  85.355 115.687  85.858 118.851  83.818 122.854  85.206 130.232  84.402
 131.898  83.142 134.782  81.397 152.372  80.755 158.806  81.448  161.12  83.463
  162.08    84.4 172.373  85.327 211.483  85.645 241.806  86.366 253.348  89.274
 259.956  91.606 260.762  92.704 281.395  92.953 290.747  94.932 336.864 100.299
#Mann= 10 ,-1 , 0
       0     .04       0  50.462      .1       0  56.694     .05       0
 100.924      .1       0 122.854      .1       0 131.898    .036       0
  161.12      .1       0 172.373     .05       0 211.483      .1       0
 290.747     .04       0
#XS Ineff= 2 ,-1
  105.15  115.95    89.8  222.03 336.864      97
Permanent Ineff=
       T       T
#Block Obstruct= 2 ,-1
  222.64   235.9    91.3   261.5  275.68  101.57
Bank Sta=130.232,162.08
XS Rating Curve= 0 ,0
Exp/Cntr=0.3,0.1