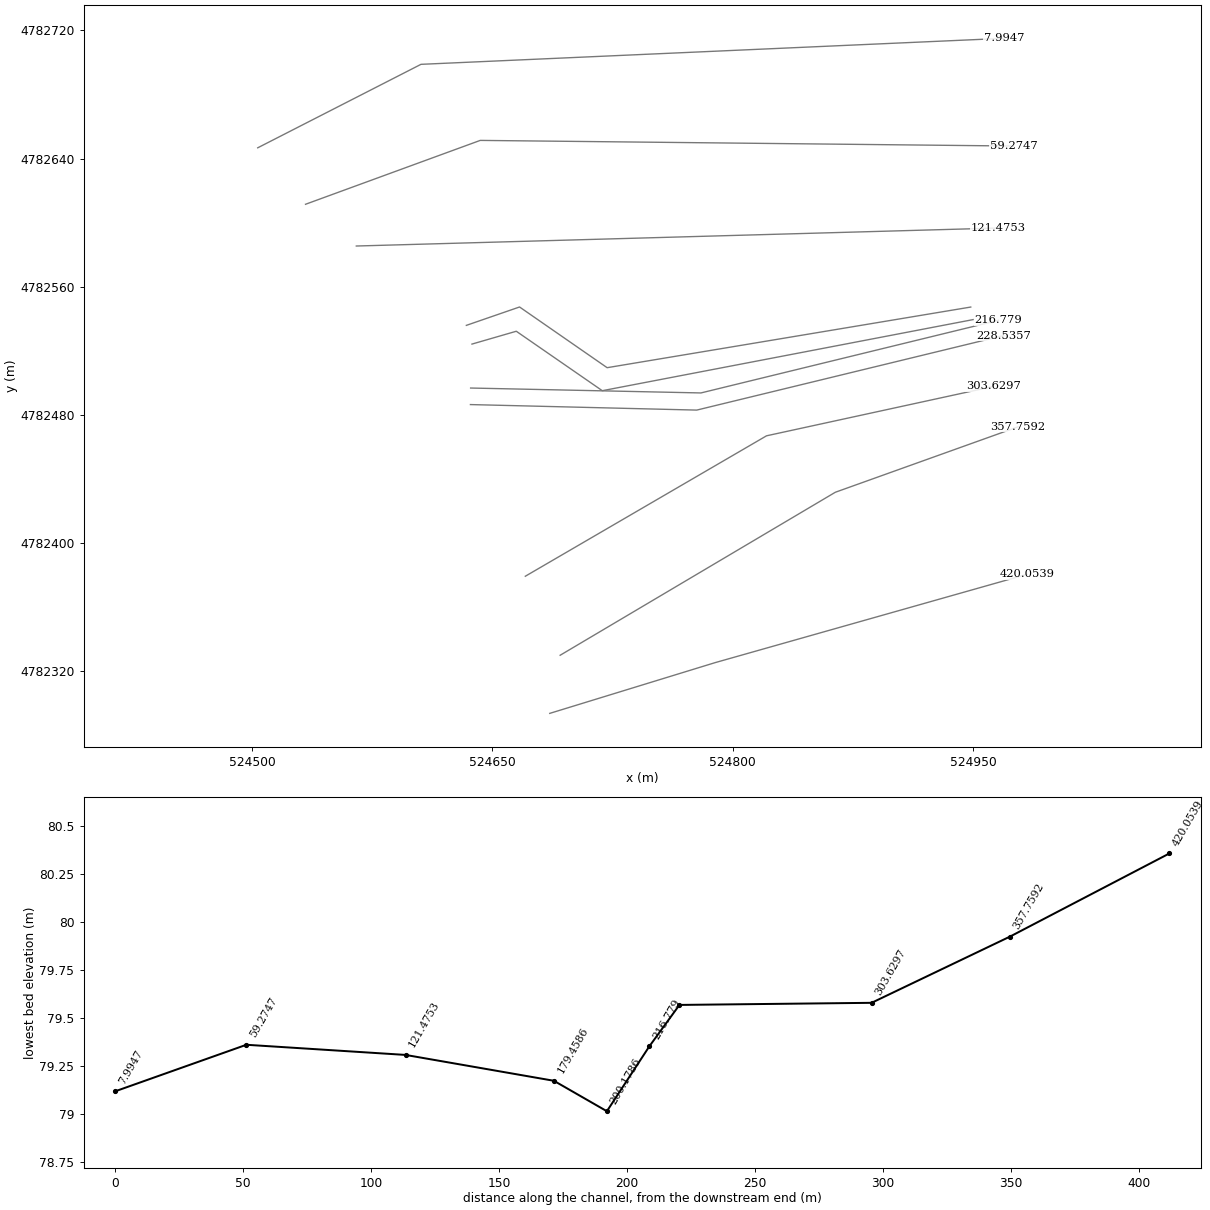
HEC-RAS study Durango.prj: Durango

--- Durango.g18 (geometry) --- (continued)

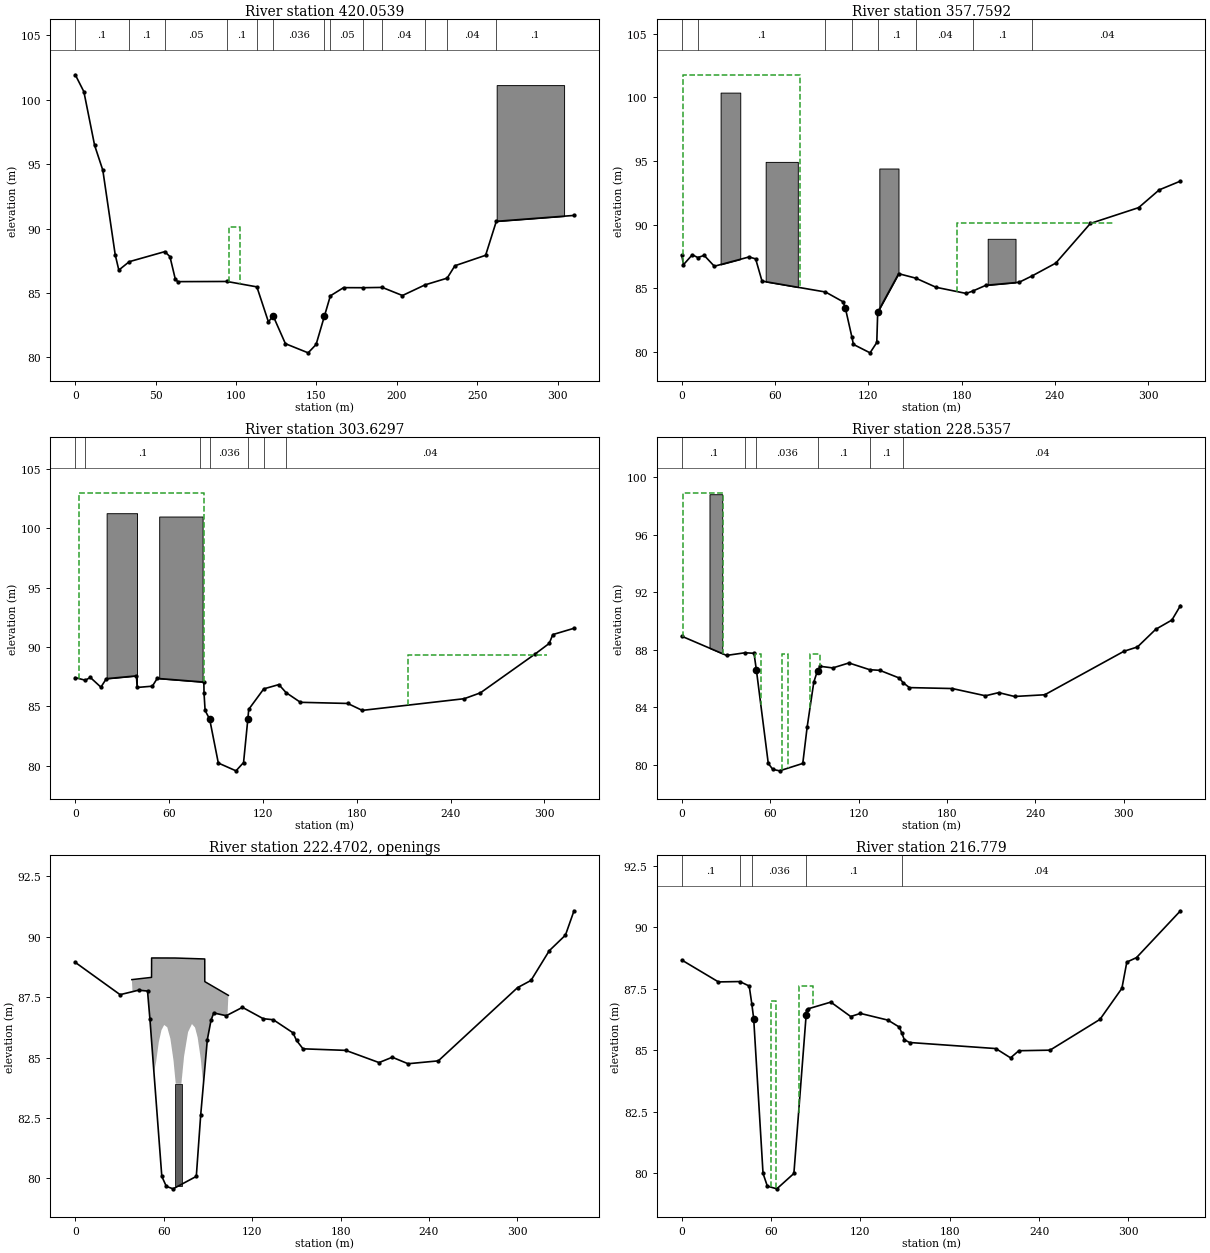
Type RM Length L Ch R = 1 ,420.0539,58.617,62.295,65.973
XS GIS Cut Line= 3
524685.8610944674782293.68719951524789.0428944674782325.34519951
524983.6812944674782380.45369951
#Sta/Elev= 30
       0 101.932   5.339  100.62  12.006  96.465  17.128  94.526  24.836  87.967
  27.079  86.779  33.535   87.43  55.684  88.211  58.871  87.824  62.215  86.076
  63.712  85.883  94.307  85.896 112.951  85.477  120.11   82.77 123.126  83.211
 130.694   81.07 144.843  80.359 149.791  81.008 154.927  83.191 158.653  84.781
 166.856  85.417 178.965  85.412  190.94  85.435 203.514  84.806 217.525  85.631
 231.299  86.153 236.129  87.116 255.229  87.927 261.887  90.562 310.219   91.02
#Mann= 13 ,-1 , 0
       0      .1       0  33.535      .1       0  55.684     .05       0
  94.307      .1       0 112.951      .1       0 123.126    .036       0
 154.927      .1       0 158.653     .05       0 178.965      .1       0
  190.94     .04       0 217.525      .1       0 231.299     .04       0
 261.887      .1       0
#XS Ineff= 1 ,-1
   95.59  102.38    90.1
Permanent Ineff=
       T
#Block Obstruct= 1 ,-1
  262.11  304.05  101.13
Bank Sta=123.126,154.927
XS Rating Curve= 0 ,0
Exp/Cntr=0.3,0.1

Type RM Length L Ch R = 1 ,357.7592,54.361,54.13,53.898
XS GIS Cut Line= 3
524692.361568344 4782329.9643584 524864.100624264782431.69432257
524978.1118118254782472.52912481
#Sta/Elev= 30
       0  87.595   1.119  86.849   6.773  87.625  10.327  87.408  14.423  87.578
  20.949  86.725  43.264  87.454  47.507  87.304  51.616  85.559  92.429  84.702
  103.71  83.937  105.17  83.456 109.339  81.201 110.385  80.587 121.084  79.925
 125.417  80.737 126.001  83.117 139.476  86.141 150.478   85.79 163.517  85.073
 182.953  84.587 187.392  84.791 195.579  85.229 216.944  85.466 225.524   85.98
 240.536  86.972 262.771  90.085 293.794  91.327 307.049  92.723 320.711  93.412
#Mann= 8 ,-1 , 0
       0      .1       0  10.327      .1       0  92.429      .1       0
 109.339    .036       0 126.001      .1       0 150.478     .04       0
 187.392      .1       0 225.524     .04       0
#XS Ineff= 2 ,-1
     .93   75.86  101.76     177  277.84   90.12
Permanent Ineff=
       T       T
#Block Obstruct= 4 ,-1
   24.98   37.62  100.36   53.96   74.63   94.92  127.05  139.38    94.4
  196.74  214.63   88.88
Bank Sta=105.17,126.001
XS Rating Curve= 0 ,0
Exp/Cntr=0.3,0.1

Type RM Length L Ch R = 1 ,303.6297,83.472,75.094,66.49
XS GIS Cut Line= 3
524670.6182944674782379.28119951524821.1628130354782466.92707691
524962.5758944674782497.70569951
#Sta/Elev= 30
       0   87.43    6.41  87.211   9.613  87.446  16.377  86.626  19.848   87.34
  39.136  87.579   39.52  86.602  49.272  86.709  52.391  87.364  82.205  87.055
  82.333   86.12  83.017  84.662  85.921  83.936  91.461  80.237 102.773  79.579
  107.61  80.279  110.36   83.96 110.916  84.759 120.521  86.482 130.176  86.844
 134.777  86.169 143.976  85.351   174.2  85.255  183.51  84.671 248.713  85.655
  259.09   86.15 293.819  89.399 303.064   90.31 305.355  91.055 318.924  91.587
#Mann= 7 ,-1 , 0
       0      .1       0    6.41      .1       0  79.859      .1       0
  85.921    .036       0  110.36      .1       0 120.521      .1       0
 134.777     .04       0
#XS Ineff= 2 ,-1
    2.47   82.03     103  212.78  301.89   89.32
Permanent Ineff=
       T       T
#Block Obstruct= 2 ,-1
   20.04   39.47  101.28   53.66   81.41     101
Bank Sta=85.921,110.36
XS Rating Curve= 0 ,0
Exp/Cntr=0.5,0.3

Type RM Length L Ch R = 1 ,228.5357,11.337,11.757,12.403
XS GIS Cut Line= 3
524636.3546472454782486.42439325524777.5997661664782482.97995294
524969.1684277724782529.50722312
#Sta/Elev= 30
       0  88.941  30.411  87.605  42.946   87.79  49.019  87.754  50.657  86.581
   58.71  80.083  61.785   79.67  66.364  79.568   82.12  80.084  85.094   82.62
  89.599  85.742  92.119  86.548  93.951  86.847 102.446  86.734 113.432   87.08
 127.552   86.61 134.371  86.567 147.707  86.027 150.159  85.709 154.516  85.364
 183.548  85.299 206.108  84.794 215.103  85.015 225.799  84.746 246.333  84.865
  300.11  87.896 309.227  88.194 321.647  89.425  332.61  90.069 338.424  91.077
#Mann= 6 ,-1 , 0
       0      .1       0  42.946      .1       0  50.657    .036       0
  92.119      .1       0 127.552      .1       0 150.159     .04       0
#XS Ineff= 4 ,-1
     .93   28.06   98.93   49.43    53.7    87.7   86.96   93.95    87.7
   68.16   71.99    87.7
Permanent Ineff=
       T       T       T       T
#Block Obstruct= 1 ,-1
   18.81   27.44   98.83
Bank Sta=50.657,92.119
XS Rating Curve= 0 ,0
Exp/Cntr=0.5,0.3

Type RM Length L Ch R = 4 ,222.4702,,,
BEGIN DESCRIPTION:
E54
END DESCRIPTION:
Bridge Culvert--1,0,-1,-1, 0
Deck Dist Width WeirC Skew NumUp NumDn MinLoCord MaxHiCord MaxSubmerge Is_Ogee
0.01,11.56,1.44,0, 28, 28, , , 0.95, 0, ,,,
  38.379  38.829  51.737   51.79  53.127  53.378  54.866  56.678  58.503  60.318
  62.394  64.511  66.644  67.801  68.161  71.987   73.82  76.538  79.162  81.246
  83.034  85.115  86.835   87.54  87.853   87.88 103.297 103.888
  88.228  88.231  88.321  89.124  89.124  89.124  89.124  89.124  89.123  89.123
  89.123  89.122  89.122  89.122  89.121  89.114   89.11  89.105    89.1  89.096
  89.092  89.088  89.085  89.083  89.083  88.145  87.598  87.577
  88.228   13.98  14.049  14.049  14.056  83.861  84.829  85.646  86.142   86.35
  86.257  85.789  84.886  84.148  83.918  83.911  85.058  86.057  86.389  86.247
  85.833  84.965  83.861  15.079  15.074  15.074  14.836  87.577
   30.01   30.46  43.368  43.421  44.758  45.009  46.497  48.309  50.134  51.949
  54.025  56.142  58.275  59.432  59.792  63.618  65.451  68.169  70.793  72.877
  74.665  76.746  78.466  79.171  79.484  79.511  94.928  95.519
  88.228  88.231  88.321  89.124  89.124  89.124  89.124  89.124  89.123  89.123
  89.123  89.122  89.122  89.122  89.121  89.114   89.11  89.105    89.1  89.096
  89.092  89.088  89.085  89.083  89.083  88.145  87.598  87.577
  88.228   13.98  14.049  14.049  14.056  83.861  84.829  85.646  86.142   86.35
  86.257  85.789  84.886  84.148  83.918  83.911  85.058  86.057  86.389  86.247
  85.833  84.965  83.861  15.079  15.074  15.074  14.836  87.577
Pier Skew, UpSta & Num, DnSta & Num=  ,70.11, 4 ,61.74, 4 , 0 , 0 , 0 ,,
    4.87    4.87    3.83    3.83
      78   80.47   80.47      88
    4.87    4.87    3.83    3.83
      78   80.47   80.47      88
BR Coef=-1 , 1 , 0 ,, 0 ,,,0.8,-1,1.39,0,
WSPro=,,,, 1 ,,,, 0 ,,,, 0 ,,,,-1 ,-1 ,-1 , 0 , 0 , 0 , 0 , 0
BC Mult= 1 ,0,40,0,33
BC Mult= 3 ,40,102,33,96
BC Mult= 1 ,102,350,96,350
BC Design=,, 0 ,, 0 ,,,,,,
BC Use User HTab Curves=0
BC User HTab FreeFlow(D)= 0

Type RM Length L Ch R = 1 ,216.779 ,29.369,16.6,2.179
XS GIS Cut Line= 3
524636.4753379134782496.74780745524780.2316909824782493.68445398
524965.9535699764782539.01647818
#Sta/Elev= 30
       0  88.666  24.656  87.775   38.99   87.79  45.306  87.608   47.06  86.878
  48.307  86.286   54.59  79.981  57.476  79.463  63.847  79.352  75.313  79.978
  83.561  86.438  83.799  86.621  84.586  86.675 100.121  86.953 113.477  86.366
 119.978  86.493 138.484   86.22 146.099  85.937  147.82  85.689 149.492  85.421
 153.044  85.309 210.958  85.062  220.84  84.684 226.371  84.974 247.343  84.997
 280.882   86.25 295.614  87.514 298.924  88.582 305.429  88.765 334.964  90.671
#Mann= 5 ,-1 , 0
       0      .1       0   38.99      .1       0   47.06    .036       0
  83.561      .1       0  147.82     .04       0
#XS Ineff= 2 ,-1
   59.79   63.62      87   78.47      88    87.6
Permanent Ineff=
       T       T
Bank Sta=48.307,83.561
XS Rating Curve= 0 ,0
Exp/Cntr=0.5,0.3

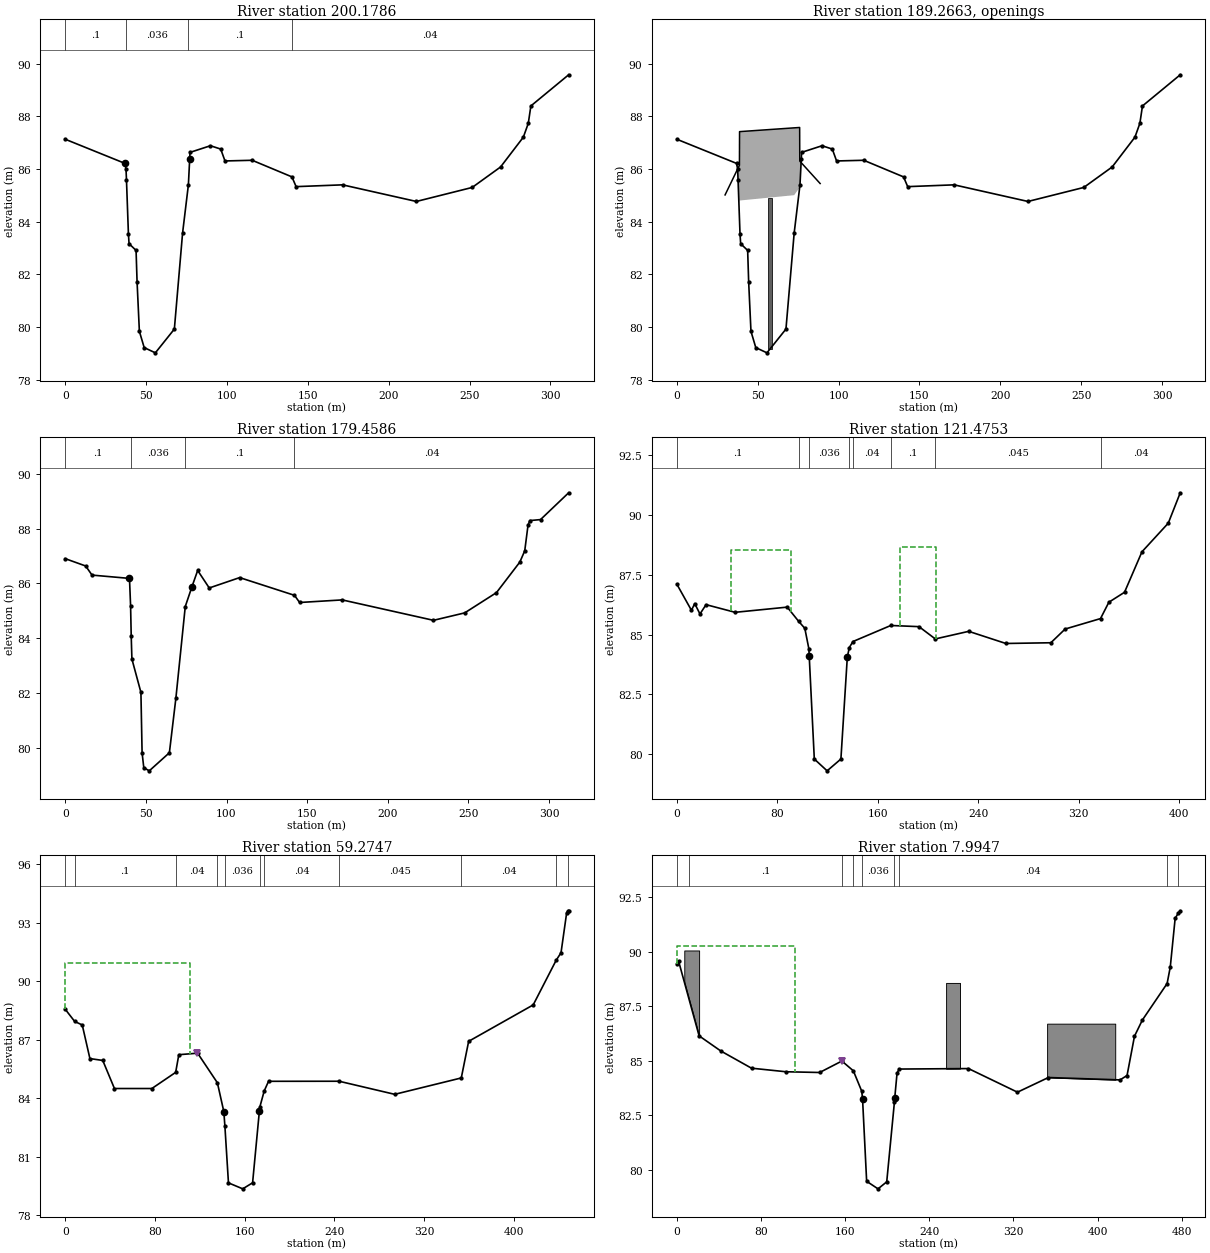
Type RM Length L Ch R = 1 ,200.1786,18.19,20.72,23.07
XS GIS Cut Line= 4
524637.3196716714782524.18063426524664.9777650444782532.18926916
524718.6540098484782495.08346263524950.103510018 4782539.4634824
#Sta/Elev= 30
       0  87.12436.89996  86.20837.55898      8637.84041  85.59539.04886  83.534
 39.4512  83.15843.78152  82.90344.40095  81.712 45.8286   79.8348.80764  79.212
  55.709  79.01367.46535  79.91672.54451  83.56176.14156  85.39476.94624  86.381
77.14565  86.62689.77477  86.87896.12676  86.75298.77477    86.3115.5848  86.326
140.1878  85.695142.7478  85.325171.4748  85.393217.1398  84.762251.6458  85.294
269.1927  86.071283.2938  87.204286.3468   87.73287.9438  88.389311.3098  89.573
#Mann= 4 ,-1 , 0
       0      .1       037.84041    .036       076.14156      .1       0
140.1878     .04       0
Bank Sta=36.89996,76.94624
XS Rating Curve= 0 ,0
Exp/Cntr=0.5,0.3

Type RM Length L Ch R = 4 ,189.2663,,,
BEGIN DESCRIPTION:
E55
END DESCRIPTION:
Bridge Culvert--1,0,-1,-1, 0
Deck Dist Width WeirC Skew NumUp NumDn MinLoCord MaxHiCord MaxSubmerge Is_Ogee
0.01,20.52,1.44,45, 11, 11, , , 0.95, 0, ,,,
  29.814  29.979  38.432  38.694  38.768  58.493  75.939  76.016  76.124  88.471
  88.604
   85.01  85.031  86.103  86.136  87.414  87.498  87.572  86.295  86.288  85.452
  85.443
   85.01 -35.944 -35.844  84.796  84.797  84.916  85.021  85.021 -34.172 -34.416
  85.443
  31.493  31.658  40.111  40.373  40.447  60.172  77.618  77.695  77.803   90.15
  90.283
   85.01  85.031  86.103  86.136  87.414  87.498  87.572  86.295  86.288  85.452
  85.443
   85.01 -35.944 -35.844  84.796  84.797  84.916  85.021  85.021 -34.172 -34.416
  85.443
Pier Skew, UpSta & Num, DnSta & Num=  ,57.61, 4 ,59.24, 4 , 0 , 0 , 0 ,,
     2.3     2.3     .93     .93
      60   80.65   80.65      87
     2.3     2.3     .93     .93
      60   80.65   80.65      87
BR Coef=-1 , 1 , 0 ,, 0 ,,,0.8,-1,1.33,0,
WSPro=,,,, 1 ,,,, 0 ,,,, 0 ,,,,-1 ,-1 ,-1 , 0 , 0 , 0 , 0 , 0
BC Mult= 1 ,0,35,0,39
BC Mult= 3 ,35,77,39,82
BC Mult= 1 ,77,350,82,350
BC Design=,, 0 ,, 0 ,,,,,,
BC Use User HTab Curves=0
BC User HTab FreeFlow(D)= 0

Type RM Length L Ch R = 1 ,179.4586,46.755,57.983,71.044
XS GIS Cut Line= 4
524633.8141634624782535.86152262524667.0169075734782547.33302904
524721.6801716184782509.44695045524948.6359465554782547.29359854
#Sta/Elev= 30
       0  86.904   12.65  86.637  16.593  86.305 39.8241  86.18540.50928   85.19
40.89536  84.087 41.3274  83.24746.91779  82.03147.64257   79.8348.69687  79.288
52.09169  79.17264.57213  79.83168.62102   81.8374.42495   85.1678.50142   85.87
82.11333  86.47489.29132  85.836108.1653  86.214142.1603  85.568145.3373  85.307
171.7753  85.401228.3703  84.657247.7243  84.928267.4423  85.667281.9303   86.78
284.9673  87.191286.9953   88.12288.1253  88.292294.7573  88.328312.2033  89.305
#Mann= 4 ,-1 , 0
       0      .1       040.50928    .036       074.42495      .1       0
142.1603     .04       0
Bank Sta=39.8241,78.50142
XS Rating Curve= 0 ,0
Exp/Cntr=0.5,0.3

Type RM Length L Ch R = 1 ,121.4753,62.748,62.201,61.653
XS GIS Cut Line= 2
524565.1254895524782585.38781937524965.7681599094782596.61170195
#Sta/Elev= 30
       0  87.105  11.615  86.014  14.222  86.296  18.391  85.862  23.257  86.251
  46.392  85.931  87.888  86.148  96.914  85.557 101.886  85.261 105.098  84.407
 105.385  84.101 109.436    79.8 119.632  79.307 130.614    79.8 135.711  84.057
 137.291  84.458   140.2   84.71  170.34  85.381 192.795  85.332 205.771  84.819
 232.372  85.136 261.944  84.629  297.78  84.659 309.172  85.233 337.314  85.669
 343.971  86.353 356.422  86.768  370.32   88.46 391.271  89.657   400.8  90.926
#Mann= 8 ,-1 , 0
       0      .1       0  96.914      .1       0 105.098    .036       0
 137.291      .1       0   140.2     .04       0  170.34      .1       0
 205.771    .045       0 337.314     .04       0
#XS Ineff= 2 ,-1
   43.17   90.75   88.53  177.53  206.17   88.66
Permanent Ineff=
       T       T
Bank Sta=105.385,135.711
XS Rating Curve= 0 ,0
Exp/Cntr=0.3,0.1

Type RM Length L Ch R = 1 ,59.2747 ,50.497,51.28,52.063
XS GIS Cut Line= 3
524533.4333944674782611.44019951524642.4777944674782651.30589951
524975.4735944674782647.78839951
#Sta/Elev= 30
       0  88.567   8.399  87.944  15.147  87.764  21.982   86.04  33.441  85.945
  43.861  84.505  77.259  84.505  98.492  85.333 101.303  86.239 118.075  86.317
 135.724  84.798 141.472  83.318 142.404  82.584 145.591  79.666 158.341   79.36
 167.127   79.67  173.15   83.33 173.574  83.553 177.492   84.38 181.352  84.875
  244.32  84.878 293.931  84.207 353.322  85.047 359.889  86.925 417.488  88.793
  437.98  91.083 442.305  91.467  447.36  93.527 448.939   93.61 449.118   93.62
#Mann= 11 ,-1 , 0
       0     .04       0   8.399      .1       0  98.492     .04       0
 135.724      .1       0 142.404    .036       0 173.574      .1       0
 177.492     .04       0  244.32    .045       0 353.322     .04       0
  437.98     .04       0 448.939      .1       0
Levee=-1,117.62,86.32,0,,,Levee 20,
#XS Ineff= 2 , 0
          111.01   90.93
Permanent Ineff=
       T       T
Bank Sta=141.472,173.15
XS Rating Curve= 0 ,0
Exp/Cntr=0.3,0.1

Type RM Length L Ch R = 1 ,7.9947  ,7.904,7.995,8.085
XS GIS Cut Line= 3
524503.5991944674782646.68099951524605.4821383394782698.78312141
524969.2351742854782715.01019518
#Sta/Elev= 30
       0  89.455   1.585   89.58  21.156   86.14  41.723  85.447  70.953  84.656
 103.734  84.492 135.743  84.458 156.868  84.984 167.779  84.535 175.782  83.595
 176.536  83.236 180.417  79.464 191.223  79.117 199.506  79.438 206.813  83.094
  207.17   83.31 209.301  84.418 211.231  84.616 277.232  84.638 323.797  83.554
 353.177  84.227 421.329  84.118 427.975   84.32  435.04  86.124  442.52  86.865
 466.057  88.541 469.074  89.303 473.695   91.53 476.537  91.763 478.547  91.882
#Mann= 9 ,-1 , 0
       0     .04       0  11.342      .1       0 156.868     .04       0
 167.779      .1       0 175.782    .036       0 206.813      .1       0
 211.231     .04       0 466.057     .04       0 476.537      .1       0
Levee=-1,156.83,85,0,,,Levee 20,
#XS Ineff= 2 , 0
          112.78   90.25
Permanent Ineff=
       T       T
#Block Obstruct= 3 ,-1
    7.05   21.15   90.06  255.95  269.16   88.57  351.98  416.74    86.7
Bank Sta=176.536,207.17
XS Rating Curve= 0 ,0
Exp/Cntr=0.3,0.1

Chan Stop Cuts=-1
Use User Specified Reach Order=0
Composite Channel Slope=5

--- Durango.g10 (geometry) ---

Geom Title=ZALDEI T100 - IBAIZ T100 visor
Program Version=4.10

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
River Reach=MAÑARIA         ,MAÑARIA-100

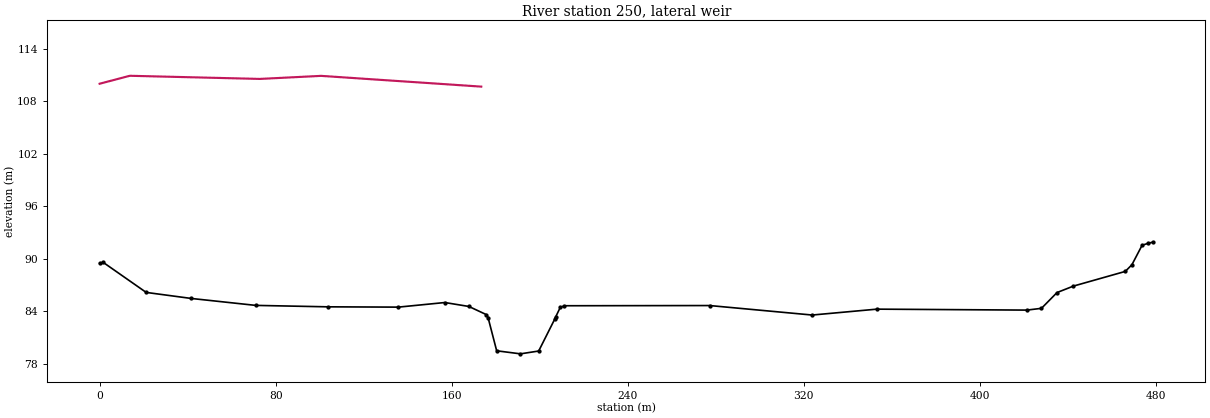
Type RM Length L Ch R = 6 ,250     ,,,
Lateral Weir Pos= 0
Lateral Weir End=CORTA           ,MANA            ,244     ,
Lateral Weir Distance=0.1
Lateral Weir TW Multiple XS=0
Lateral Weir WD=1
Lateral Weir Coef=1.1
Lateral Weir WSCriteria= 0
Lateral Weir Flap Gates= 0
Lateral Weir Hagers EQN= 0 ,,,,,
Lateral Weir SS=0.05,0.05,
Lateral Weir Type= 0
Lateral Weir Connection Pos and Dist= 1 ,
Lateral Weir SE= 5
       0     110   13.72  110.91   72.79  110.55  100.65   110.9  173.42  109.67
Lateral Weir HW RS Station=250.0139,-0.1
Lateral Weir TW RS Station=221.1893,0
LW Div RC= 0 ,False,

River Reach=ZALDEI          ,ZALDEI

River Reach=CORTA           ,MANA

River Reach=IBAIZABAL       ,IBAIZABAL-103

River Reach=IBAIZABAL       ,IBAIZABAL-102

River Reach=IBAIZABAL       ,IBAIZABAL-101

River Reach=IBAIZABAL       ,IBAIZABAL-100

--- Durango.g19 (geometry) ---

Geom Title=ZALDEI T500 - IBAIZ T500 visor URBAN
Program Version=4.10

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
River Reach=MAÑARIA         ,MAÑARIA-100

River Reach=ZALDEI          ,ZALDEI

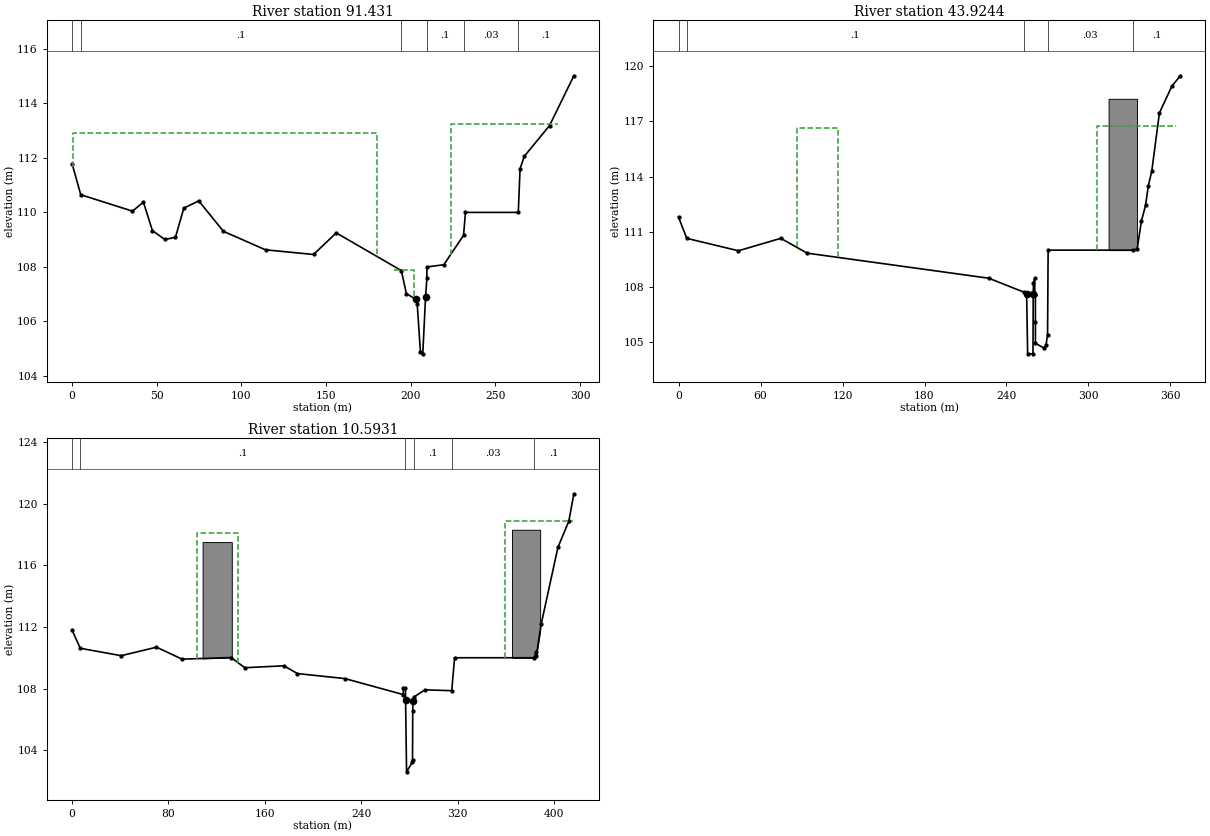
Type RM Length L Ch R = 1 ,91.431  ,46.536,47.507,48.532
XS GIS Cut Line= 4
529951.8689309634780429.89509595529907.1676365494780368.95141284
529790.5459466784780377.45274854529764.3223888684780477.95739569
#Sta/Elev= 30
       0 111.792   5.127  110.65  35.672 110.046  42.139 110.378  47.441 109.332
  54.794 109.005  61.062 109.084  66.008 110.156   74.82 110.424  89.386 109.305
 114.257 108.626 142.609 108.454 156.031 109.248 194.488 107.863 197.467 107.011
 203.137 106.813 203.878 106.622 205.746 104.882 207.146 104.805  208.78  106.88
 209.565 107.581 209.571 107.997 219.576 108.078 231.229 109.158 232.354     110
 263.561     110 264.608 111.603 267.116 112.061 282.009 113.188 296.381 115.018
#Mann= 6 ,-1 , 0
       0     .04       0   5.127      .1       0 194.488    .034       0
 209.571      .1       0 231.229     .03       0 263.561      .1       0
#XS Ineff= 3 ,-1
     .53  180.26  112.93  190.04  201.67  107.87  223.61  287.05  113.23
Permanent Ineff=
       T       T       T
Bank Sta=203.137,208.78
XS Rating Curve= 0 ,0
Exp/Cntr=0.5,0.3

Type RM Length L Ch R = 1 ,43.9244 ,29.919,33.331,36.263
XS GIS Cut Line= 5
529951.8689309634780429.89509595529901.7987287954780344.17316274
529758.1332086974780351.32274952529738.8764973014780377.32082088
529723.2543950064780467.72026496
#Sta/Elev= 30
       0 111.792   6.022  110.64  43.813 109.966  74.838 110.642    94.1 109.836
 227.019 108.473 252.504 107.722 254.746   107.6  255.47  104.37  259.38  104.36
  259.55   107.6 259.739 108.226  260.64 108.463 260.758 107.587 261.145 107.607
 261.167 106.112 261.178 104.934 267.508 104.673 268.927 104.832 270.056 105.408
  270.47     110   332.7     110 335.623  110.05 338.715 111.577 341.759 112.433
 343.789 113.505 346.303 114.291 351.907 117.462 361.041 118.922  367.21 119.482
#Mann= 5 ,-1 , 0
       0     .04       0   6.022      .1       0 252.504    .034       0
 270.056     .03       0   332.7      .1       0
Levee=0,,,-1,275.8,,,
#XS Ineff= 2 ,-1
    86.7     117  116.65   305.9   363.7  116.74
Permanent Ineff=
       T       T
#Block Obstruct= 1 ,-1
  314.71  335.51  118.23
Bank Sta=254.746,259.55
XS Rating Curve= 0 ,0
Exp/Cntr=0.5,0.3

Type RM Length L Ch R = 1 ,10.5931 ,0.717,10.593,0.526
XS GIS Cut Line= 6
529951.8689309634780429.89509595529900.8169160564780327.58129156
529817.7433632714780346.25106084529762.9253917314780342.62653683
529737.3809712844780331.31531477529707.6163544394780461.68704897
#Sta/Elev= 30
       0 111.792    6.79 110.615  40.769 110.134  70.062 110.685  91.337 109.909
 132.006 110.015 143.359 109.354 175.887 109.478 187.108 108.973 226.436 108.651
 274.882 107.613  275.02 108.028 276.725 108.012  276.84 107.286 277.673 102.603
 282.563 103.242 282.613 103.369 282.793 106.516 282.878 107.203 284.149 107.473
 292.919 107.921 315.165 107.864 317.546     110 383.566     110 385.184 110.377
 385.378  110.13 389.489 112.207 403.328 117.159 412.356 118.854 416.546 120.632
#Mann= 6 ,-1 , 0
       0     .04       0    6.79      .1       0 276.725    .034       0
 284.149      .1       0 315.165     .03       0 383.566      .1       0
Levee=0,,,-1,303.15,,,
#XS Ineff= 2 ,-1
  103.96  137.89  118.07  359.03  415.42  118.87
Permanent Ineff=
       T       T
#Block Obstruct= 2 ,-1
  108.37   132.6   117.5   365.2  388.55   118.3
Bank Sta=276.84,282.878
XS Rating Curve= 0 ,0
Exp/Cntr=0.5,0.3

River Reach=CORTA           ,MANA

River Reach=IBAIZABAL       ,IBAIZABAL-103

River Reach=IBAIZABAL       ,IBAIZABAL-102

River Reach=IBAIZABAL       ,IBAIZABAL-101

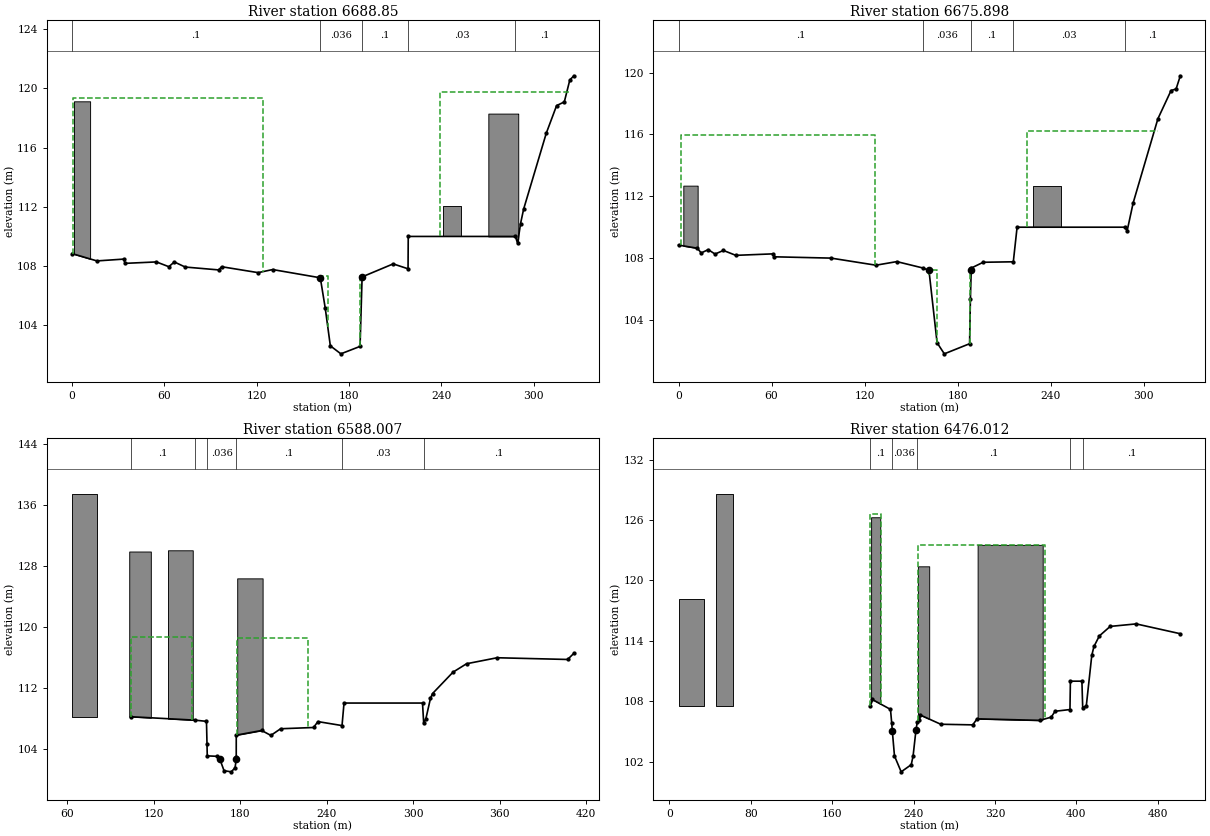
Type RM Length L Ch R = 1 ,6688.85 ,12.892,12.952,13.024
XS GIS Cut Line= 4
529753.5801596394780143.39904175529734.720327219 4780277.2826349
 529722.320670314780369.81203209 529688.240634544780461.10191425
#Sta/Elev= 30
       0 108.842   16.12 108.346  33.422 108.468  34.567 108.182  54.778 108.278
  62.857 107.956  66.434 108.275  73.516 107.932  95.172 107.739  97.192 107.954
 120.897 107.554 130.331 107.762 161.281 107.206 164.508 105.137 167.792 102.609
 174.638 102.068 187.101 102.571  188.43 107.267 208.613 108.145 218.283 107.814
 218.406     110 287.966     110 289.482  109.54 291.357 110.861 293.368 111.845
 308.097 116.978 314.794 118.841 319.795 119.088 323.379 120.572 326.006 120.855
#Mann= 5 ,-1 , 0
       0      .1       0 161.281    .036       0  188.43      .1       0
 218.283     .03       0 287.966      .1       0
#XS Ineff= 4 ,-1
     .62  123.96  119.33  161.28  166.18   107.3  187.01   188.4   107.3
   239.3  322.86  119.77
Permanent Ineff=
       T       T       T       T
#Block Obstruct= 3 ,-1
    1.23   11.72  119.13  241.15  252.86  112.07  270.44  289.87   118.3
Bank Sta=161.281,188.43
XS Rating Curve= 0 ,0
Exp/Cntr=0.5,0.3

Type RM Length L Ch R = 1 ,6675.898,81.325,87.891,94.457
XS GIS Cut Line= 4
529753.5801596394780143.39904175529722.221959279 4780274.8000968
 529709.866534874780364.11424001 529672.411606344780455.16602867
#Sta/Elev= 30
       0 108.842  12.102  108.64  14.642 108.333  19.133  108.55   23.54 108.262
  28.942 108.495  36.944 108.178  60.906 108.274  61.674 108.084  98.412 107.999
 127.348  107.54 140.819 107.773 157.841 107.355 161.555   107.2 166.792 102.521
 171.462 101.804  187.76 102.459 188.289 105.359   188.8   107.2 188.802 107.353
 196.523  107.73 215.969 107.761 218.406     110 287.966     110 289.368 109.752
 293.302 111.579 309.243 117.018 317.737 118.845  320.98 118.945  323.71 119.799
#Mann= 5 ,-1 , 0
       0      .1       0 157.841    .036       0 188.802      .1       0
 215.969     .03       0 287.966      .1       0
#XS Ineff= 4 ,-1
    1.54  126.74  115.97  161.85  166.91   107.2  187.74   188.8  107.35
   224.8   309.3  116.24
Permanent Ineff=
       T       T       T       T
#Block Obstruct= 2 ,-1
    3.08   12.33  112.69  228.81     247  112.64
Bank Sta=161.555,188.8
XS Rating Curve= 0 ,0
Exp/Cntr=0.5,0.3

Type RM Length L Ch R = 1 ,6588.007,112.76,111.994,111.228
XS GIS Cut Line= 3
529685.0109435714780221.88110906529562.2602542334780362.37751118
529488.8510944674780458.15569951
#Sta/Elev= 30
 104.217 108.207 148.948 107.753 156.662   107.6 157.016 104.676 157.198 103.073
 163.654  103.02 165.989  102.61 168.832 101.132 173.832  100.98 176.489 101.516
  177.28  102.61 177.301 102.912 177.316 105.792 194.932 106.401 201.311 105.756
 208.077 106.629 230.889 106.794 233.954 107.568 250.672 107.046 252.049     110
 306.489     110 307.312 107.356 308.755 107.887 312.005  110.61 313.432 111.242
 327.654 114.052 337.021 115.152 358.234  115.94 407.124 115.714 411.459 116.519
#Mann= 6 ,-1 , 0
 104.217      .1       0 148.948      .1       0 157.016    .036       0
 177.316      .1       0 250.672     .03       0 307.312      .1       0
#XS Ineff= 2 ,-1
       0  146.69118.6233  177.98  227.31118.4967
Permanent Ineff=
       T       T
#Block Obstruct= 4 ,-1
   63.44   81.06  137.44  103.08  118.06  129.87  129.96  147.14  130.03
  177.97  195.59  126.35
Bank Sta=165.989,177.28
XS Rating Curve= 0 ,0
Exp/Cntr=0.3,0.1

Type RM Length L Ch R = 1 ,6476.012,176.73,75.552,74.374
XS GIS Cut Line= 3
529580.7708754214780167.78914113529526.3717219344780239.28517142
529453.4148841394780441.47983617
#Sta/Elev= 30
 197.332 107.507 199.368 108.185  217.28   107.2 218.508 105.827  219.12  105.02
 221.204  102.58 227.782 101.001  237.69 101.711 239.505  102.58 242.323 105.137
 243.573 105.928 245.751 106.173 246.152 106.659 266.694 105.724 298.103 105.664
 302.433 106.263 364.093  106.11 375.295 106.432 378.977 107.013 393.663 107.184
 394.096     110 405.406     110  406.19  107.35  409.74  107.57 415.122 112.568
 417.248 113.444 422.544 114.491 433.195 115.436 458.709 115.685 502.126 114.708
#Mann= 5 ,-1 , 0
 197.332      .1       0 218.508    .036       0 243.573      .1       0
 393.663     .03       0  406.19      .1       0
#XS Ineff= 2 ,-1
  185.55  208.28  126.64  244.23  368.99  123.48
Permanent Ineff=
       T       T
#Block Obstruct= 5 ,-1
    8.99   34.36   118.2   45.46   62.38   128.6  198.24  207.22  126.27
  244.23  255.33   121.4  302.91  366.87  123.53
Bank Sta=219.12,242.323
XS Rating Curve= 0 ,0
Exp/Cntr=0.3,0.1

River Reach=IBAIZABAL       ,IBAIZABAL-100

--- Durango.g20 (geometry) ---

Geom Title=ZALDEI T100 - IBAIZ T100 visor VID
Program Version=4.10

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
River Reach=MAÑARIA         ,MAÑARIA-100

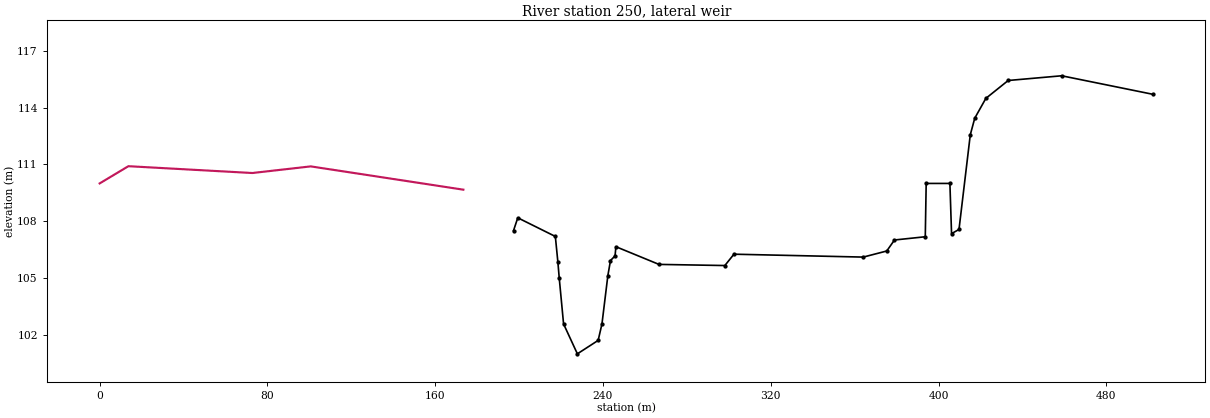
Type RM Length L Ch R = 6 ,250     ,,,
Lateral Weir Pos= 0
Lateral Weir End=CORTA           ,MANA            ,244     ,
Lateral Weir Distance=0.1
Lateral Weir TW Multiple XS=0
Lateral Weir WD=1
Lateral Weir Coef=1.1
Lateral Weir WSCriteria= 0
Lateral Weir Flap Gates= 0
Lateral Weir Hagers EQN= 0 ,,,,,
Lateral Weir SS=0.05,0.05,
Lateral Weir Type= 0
Lateral Weir Connection Pos and Dist= 1 ,
Lateral Weir SE= 5
       0     110   13.72  110.91   72.79  110.55  100.65   110.9  173.42  109.67
Lateral Weir HW RS Station=250.0139,-0.1
Lateral Weir TW RS Station=221.1893,0
LW Div RC= 0 ,False,

River Reach=ZALDEI          ,ZALDEI

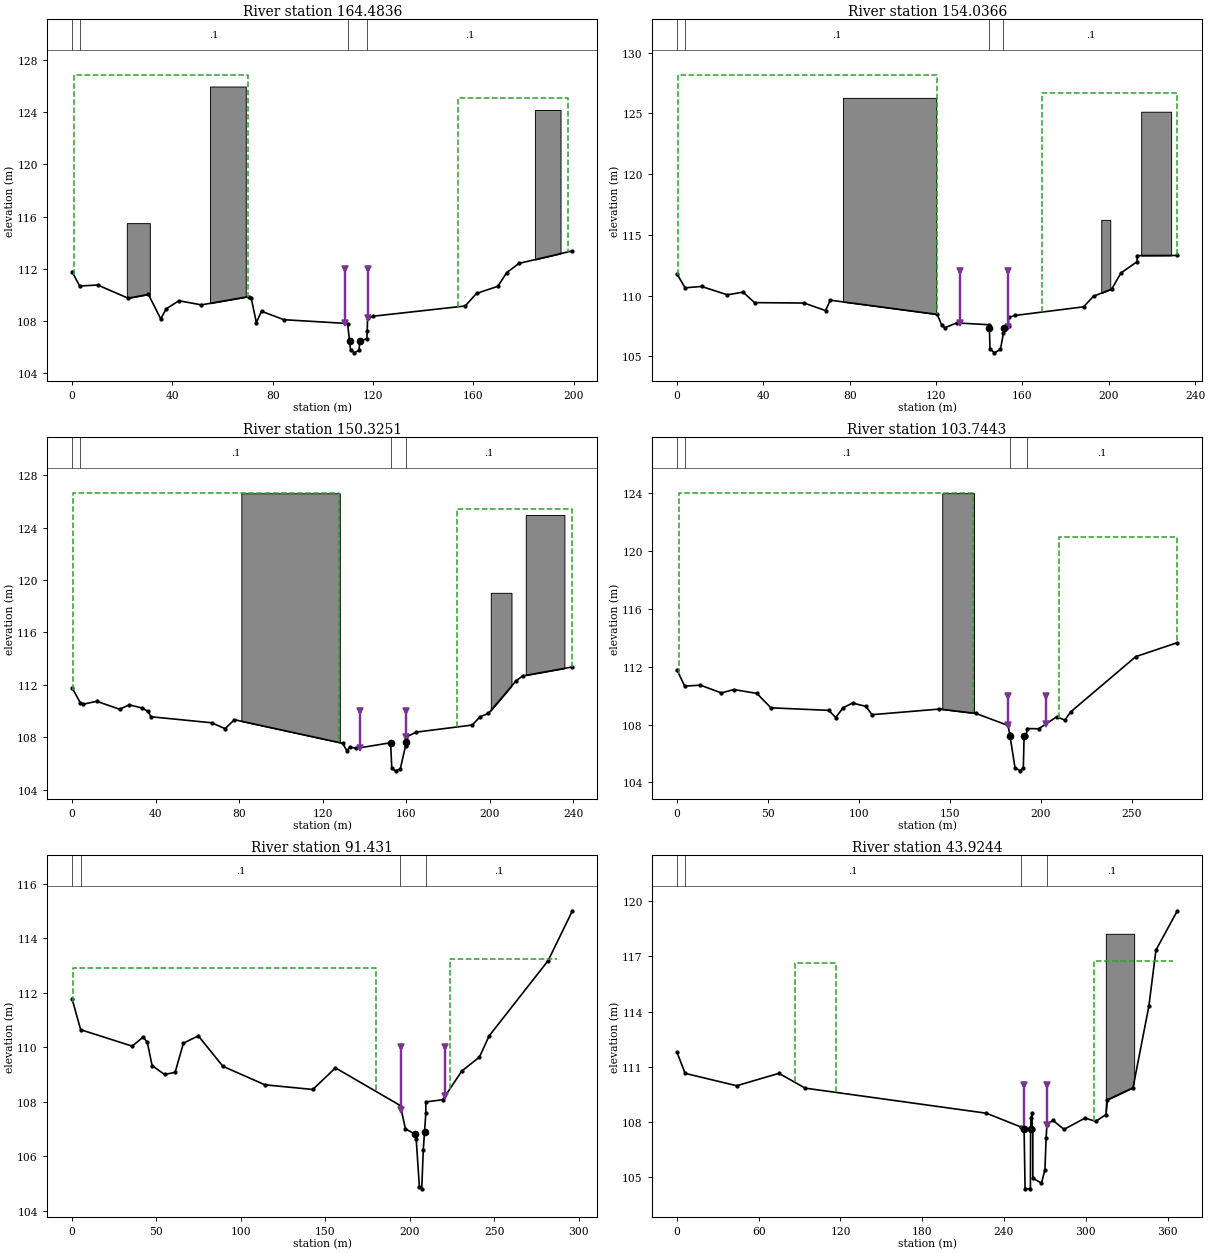
Type RM Length L Ch R = 1 ,164.4836,11.431,10.447,9.463
XS GIS Cut Line= 5
529951.8689309634780429.89509595529900.8607581254780422.00339017
529861.1645233424780411.24459756529840.7599166774780440.55303259
529785.481982259 4780485.0721744
#Sta/Elev= 30
       0 111.792   3.051 110.676  10.218 110.758  22.361 109.747  30.456 110.033
  35.362 108.159  37.539  108.93  42.599  109.55  51.544 109.235  70.357 109.868
  71.393 109.793  73.466  107.88  75.538 108.744  84.464 108.098 109.833 107.805
  110.62  106.45  111.01 105.797 112.501 105.558 114.413 105.751 114.663 106.432
 117.532 106.653  117.66 107.231 117.795   108.2  119.89 108.364 156.688 109.149
 161.225 110.112 169.759  110.66 173.235 111.707   178.2 112.417 199.431 113.375
#Mann= 4 ,-1 , 0
       0     .04       0   3.051      .1       0 109.833    .034       0
  117.66      .1       0
Levee=-1,109,112,-1,118,112,,
#XS Ineff= 2 ,-1
      .7   70.13  126.87  153.83  197.71   125.1
Permanent Ineff=
       T       T
#Block Obstruct= 3 ,-1
   21.85   31.01   115.5   54.98   69.25  125.97  184.49  194.71  124.17
Bank Sta=110.62,114.663
XS Rating Curve= 0 ,0
Exp/Cntr=0.5,0.3

Type RM Length L Ch R = 1 ,154.0366,3.695,3.712,3.728
XS GIS Cut Line= 5
529951.8688944674780429.89509951529897.8653909364780389.03640177
529846.976218642 4780396.2669203529835.803125614  4780440.532689
529784.4979188814780483.54827538
#Sta/Elev= 30
       0 111.792   3.777 110.639  11.408 110.752   23.34 110.062  30.627 110.283
  35.945 109.421  58.876 109.386  68.824 108.764   70.99 109.623 120.537 108.451
 122.599 107.575 123.984 107.347 129.478  107.75 144.602   107.6  144.69  107.33
  144.96  105.62 147.041 105.288 149.798  105.57 151.206 106.916 151.665 107.328
  153.54 107.458 153.569   108.2  156.62 108.366 188.302 109.074 192.897 109.945
 201.355 110.538 205.598 111.858 213.033 112.781 213.192  113.29 231.726 113.302
#Mann= 4 ,-1 , 0
       0     .04       0   3.777      .1       0 144.602    .034       0
 151.206      .1       0
Levee=-1,131,112,-1,153.5,112,,
#XS Ineff= 2 ,-1
     .44  120.48  128.17  169.16   232.6  126.67
Permanent Ineff=
       T       T
#Block Obstruct= 3 ,-1
   76.87  120.04  126.27  196.48  200.66  116.23  214.98  228.85  125.13
Bank Sta=144.69,151.665
XS Rating Curve= 0 ,0
Exp/Cntr=0.5,0.3

Type RM Length L Ch R = 1 ,150.3251,46.619,46.581,46.518
XS GIS Cut Line= 5
529951.8688944674780429.89509951529898.0775065694780385.19648778
529844.3287805754780392.48585639529832.1345755834780439.48787744
529781.0203245284780482.44102406
#Sta/Elev= 30
       0 111.792   3.928 110.643   5.328 110.522  11.829 110.745  22.765 110.138
  27.431 110.471  33.625 110.231  36.386 109.966  37.833 109.563  66.838 109.104
  73.273 108.654  77.716 109.338 129.506 107.539 131.572 106.958 132.937 107.253
  136.14  107.15 152.515  107.58 153.048 105.626 154.842 105.433 157.099 105.565
  159.65 107.348  159.69   107.6 159.776     108 164.759  108.39 191.522  108.93
 195.419 109.571 199.337  109.82 212.399 112.287 215.691 112.685 239.504 113.368
#Mann= 4 ,-1 , 0
       0     .04       0   3.928      .1       0 152.515    .034       0
  159.69      .1       0
Levee=-1,138,110,-1,160,110,,
#XS Ineff= 2 ,-1
     .66  127.75  126.67  184.14  239.65   125.4
Permanent Ineff=
       T       T
#Block Obstruct= 3 ,-1
   81.06  128.19  126.63  200.44  210.35  119.03  217.18  235.68  124.97
Bank Sta=152.515,159.69
XS Rating Curve= 0 ,0
Exp/Cntr=0.5,0.3

Type RM Length L Ch R = 1 ,103.7443,12.313,12.313,12.363
XS GIS Cut Line= 5
529951.8689309634780429.89509595529900.489765277 4780378.5972269
529801.6003678864780381.42073808529788.917586548 4780431.1014923
529775.4651753514780481.73323877
#Sta/Elev= 30
       0 111.792   4.266 110.661  12.856  110.73  24.479 110.191  31.227 110.427
  43.945 110.159  51.673 109.163  83.523 108.986  87.329  108.49   91.33 109.161
  96.615 109.494 103.952  109.26 107.283 108.688 144.356 109.078  164.36 108.776
 182.082 107.945 182.972 107.383 183.162 107.227 185.907 105.025 188.807 104.806
 190.485 105.014  190.92 107.206 192.129 107.233 192.557 107.729 198.968 107.714
 208.915 108.549 213.303 108.309 216.545 108.883 252.337 112.703 275.196 113.666
#Mann= 4 ,-1 , 0
       0     .04       0   4.266      .1       0 182.972    .034       0
 192.557      .1       0
Levee=-1,182.08,110,-1,203,110,,
#XS Ineff= 2 ,-1
    1.06  162.56  124.03  210.13  278.85     121
Permanent Ineff=
       T       T
#Block Obstruct= 1 ,-1
   145.9  163.35     124
Bank Sta=183.162,190.92
XS Rating Curve= 0 ,0
Exp/Cntr=0.5,0.3

Type RM Length L Ch R = 1 ,91.431  ,46.536,47.507,48.532
XS GIS Cut Line= 4
529951.8689309634780429.89509595529907.1676365494780368.95141284
529790.5459466784780377.45274854529764.3223888684780477.95739569
#Sta/Elev= 30
       0 111.792   5.127  110.65  35.672 110.046  42.139 110.378  44.608 110.187
  47.441 109.332  54.794 109.005  61.062 109.084  66.008 110.156   74.82 110.424
  89.386 109.305 114.257 108.626 142.609 108.454 156.031 109.248 194.488 107.863
 197.467 107.011 203.137 106.813 203.878 106.622 205.746 104.882 207.146 104.805
 208.054 106.237  208.78  106.88 209.565 107.581 209.571 107.997 219.576 108.078
 230.845 109.131 241.279 109.642 247.073 110.422 282.009 113.188 296.381 115.018
#Mann= 4 ,-1 , 0
       0     .04       0   5.127      .1       0 194.488    .034       0
 209.571      .1       0
Levee=-1,195,110,-1,221,110,,
#XS Ineff= 2 ,-1
     .53  180.26  112.93  223.61  287.05  113.23
Permanent Ineff=
       T       T
Bank Sta=203.137,208.78
XS Rating Curve= 0 ,0
Exp/Cntr=0.5,0.3

Type RM Length L Ch R = 1 ,43.9244 ,29.919,33.331,36.263
XS GIS Cut Line= 5
529951.8689309634780429.89509595529901.7987287954780344.17316274
529758.1332086974780351.32274952529738.8764973014780377.32082088
529723.2543950064780467.72026496
#Sta/Elev= 30
       0 111.792   6.022  110.64  43.813 109.966  74.838 110.642    94.1 109.836
 227.019 108.473 252.504 107.722 254.746   107.6  255.47  104.37  259.38  104.36
  259.55   107.6 259.739 108.226  260.64 108.463 260.758 107.587 261.145 107.607
 261.178 104.934 267.508 104.673 270.056 105.408 270.891 107.108 271.485 107.811
 275.796 108.091 284.034 107.595 299.461 108.207 307.255 108.031 314.777 108.396
 315.643 109.193 334.655 109.858 346.303 114.291 351.516 117.349  367.21 119.482
#Mann= 4 ,-1 , 0
       0     .04       0   6.022      .1       0 252.504    .034       0
 271.485      .1       0
Levee=-1,254.75,110,-1,271.5,110,,
#XS Ineff= 2 ,-1
    86.7     117  116.65   305.9   363.7  116.74
Permanent Ineff=
       T       T
#Block Obstruct= 1 ,-1
  314.71  335.51  118.23
Bank Sta=254.746,259.55
XS Rating Curve= 0 ,0
Exp/Cntr=0.5,0.3

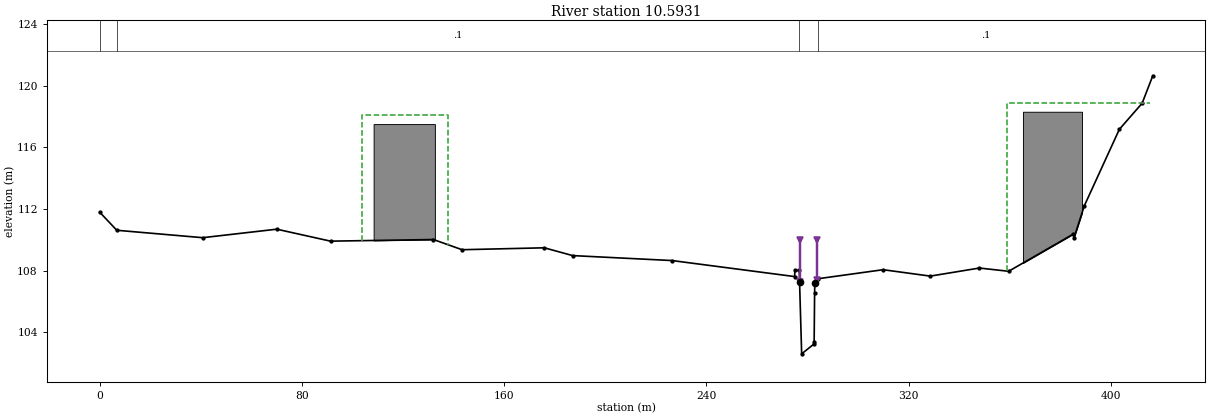
Type RM Length L Ch R = 1 ,10.5931 ,0.717,10.593,0.526
XS GIS Cut Line= 6
529951.8689309634780429.89509595529900.8169160564780327.58129156
529817.7433632714780346.25106084529762.9253917314780342.62653683
529737.3809712844780331.31531477529707.6163544394780461.68704897
#Sta/Elev= 30
       0 111.792    6.79 110.615  40.769 110.134  70.062 110.685  91.337 109.909
 132.006 110.015 143.359 109.354 175.887 109.478 187.108 108.973 226.436 108.651
 274.882 107.613  275.02 108.028 276.725 108.012  276.84 107.286 277.673 102.603
 282.563 103.242 282.613 103.369 282.793 106.516 282.878 107.203 284.149 107.473
 309.905 108.058 328.541 107.643 347.979 108.166 359.539 107.956 385.184 110.377
 385.378  110.13 389.489 112.207 403.328 117.159 412.356 118.854 416.546 120.632
#Mann= 4 ,-1 , 0
       0     .04       0    6.79      .1       0 276.725    .034       0
 284.149      .1       0
Levee=-1,276.84,110,-1,283.875,110,,
#XS Ineff= 2 ,-1
  103.96  137.89  118.07  359.03  415.42  118.87
Permanent Ineff=
       T       T
#Block Obstruct= 2 ,-1
  108.37   132.6   117.5   365.2  388.55   118.3
Bank Sta=276.84,282.878
XS Rating Curve= 0 ,0
Exp/Cntr=0.5,0.3

River Reach=CORTA           ,MANA

River Reach=IBAIZABAL       ,IBAIZABAL-103

River Reach=IBAIZABAL       ,IBAIZABAL-102

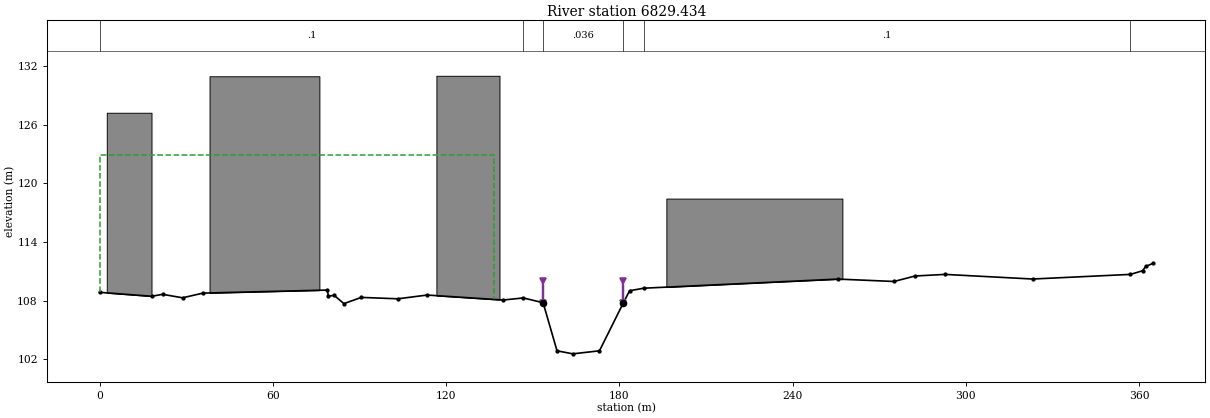
Type RM Length L Ch R = 1 ,6829.434,2.837,140.584,2.906
XS GIS Cut Line= 4
529753.5801596394780143.39904175529809.9892876514780260.66592653
529899.0181985664780305.90390722529951.8689309634780429.89509595
#Sta/Elev= 30
       0 108.842  18.023 108.439  21.822 108.637  28.731 108.282  35.779 108.762
  78.874 109.074  79.225  108.45  81.245 108.532  84.604 107.687   90.65 108.322
 103.286 108.179 113.456 108.564 139.852 108.055  146.75 108.268 153.613 107.776
 158.427  102.86 163.897  102.55  173.13  102.86  181.43  107.78 183.563     109
  188.48 109.265 255.796 110.196 275.108 109.951 282.475 110.512 292.819 110.675
 323.193 110.202 357.044 110.676  361.24 111.047 362.327 111.486 364.777 111.792
#Mann= 6 ,-1 , 0
       0      .1       0  146.75      .1       0 153.613    .036       0
  181.43      .1       0  188.48      .1       0 357.044     .04       0
Levee=-1,153.613,110,-1,181.43,110,,
#XS Ineff= 2 , 0
          136.74  122.87
Permanent Ineff=
       T       T
#Block Obstruct= 4 ,-1
    2.47   17.97  127.21   38.06   76.12  130.94  116.65   138.5  130.99
   196.3  257.27  118.43
Bank Sta=153.613,181.43
XS Rating Curve= 0 ,0
Exp/Cntr=0.5,0.3

River Reach=IBAIZABAL       ,IBAIZABAL-101