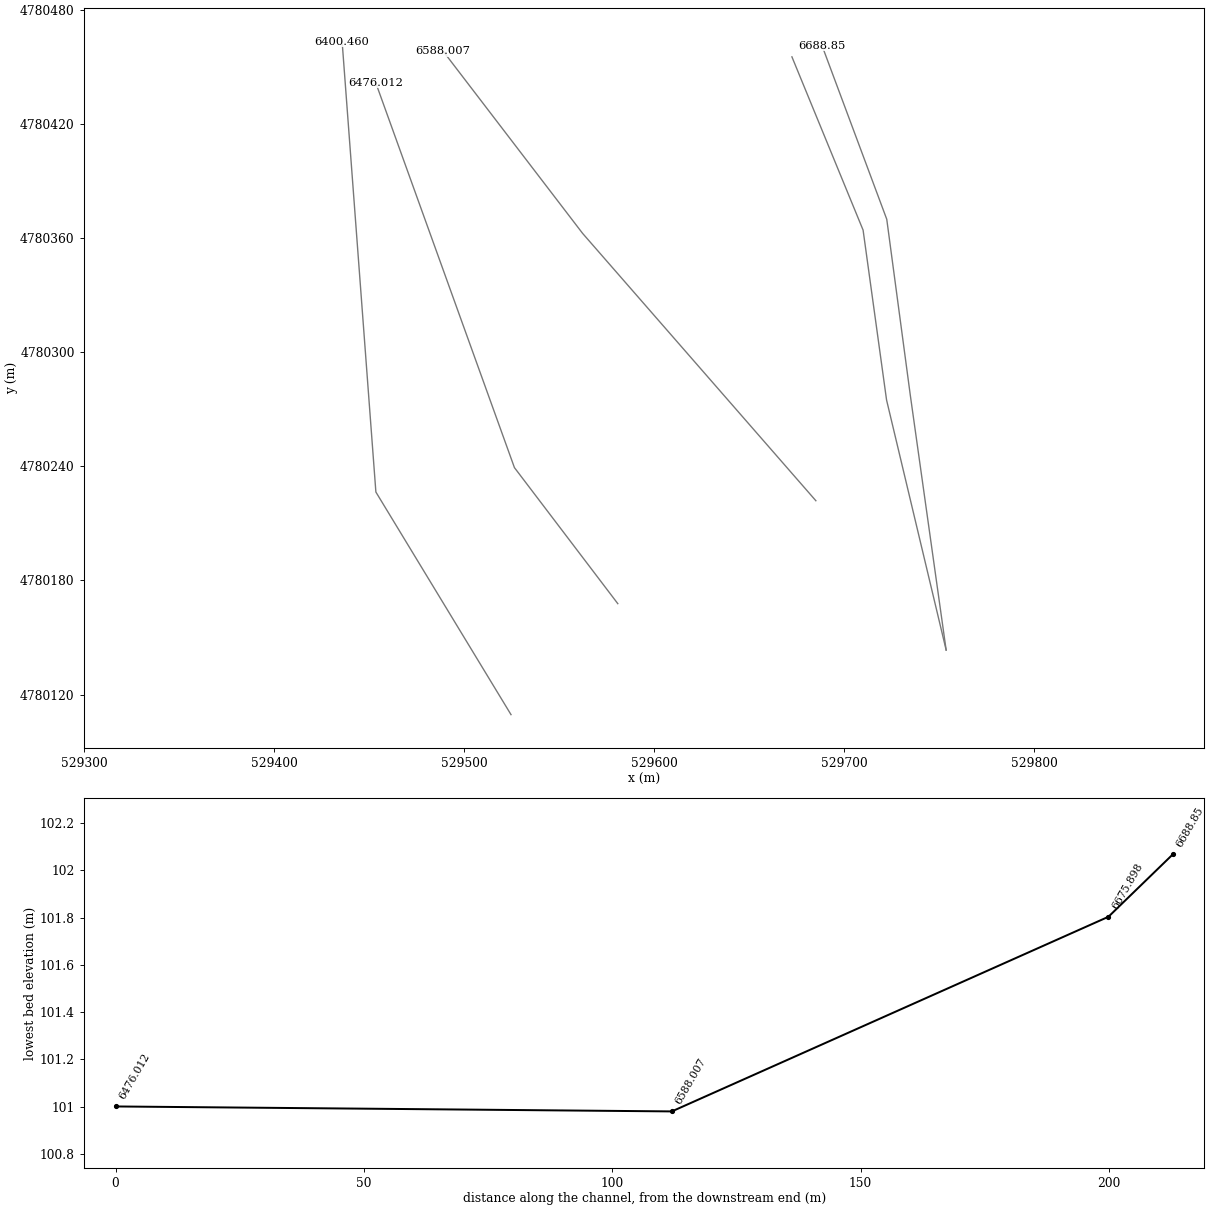
HEC-RAS study Durango.prj: Durango

--- Durango.g20 (geometry) --- (continued)

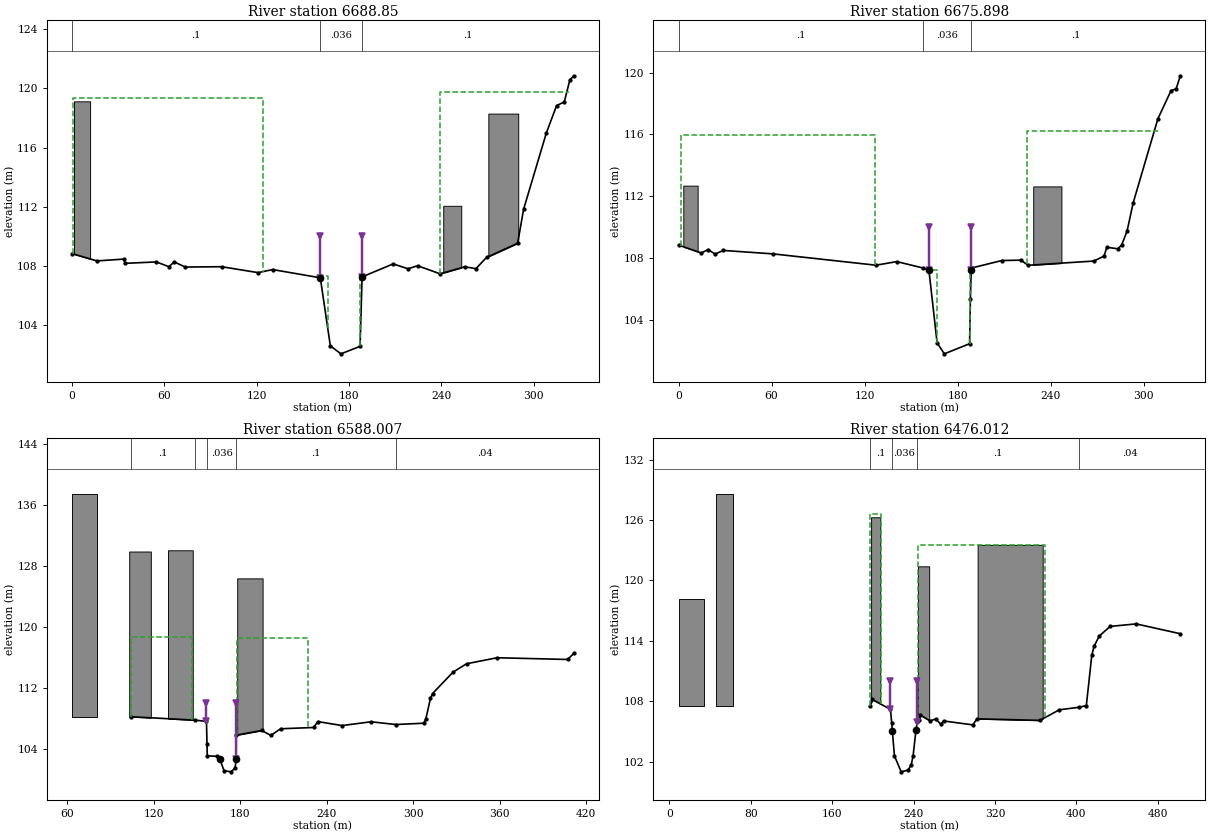
Type RM Length L Ch R = 1 ,6688.85 ,12.892,12.952,13.024
XS GIS Cut Line= 4
529753.5801596394780143.39904175529734.720327219 4780277.2826349
 529722.320670314780369.81203209 529688.240634544780461.10191425
#Sta/Elev= 30
       0 108.842   16.12 108.346  33.422 108.468  34.567 108.182  54.778 108.278
  62.857 107.956  66.434 108.275  73.516 107.932  97.192 107.954 120.897 107.554
 130.331 107.762 161.281 107.206 167.792 102.609 174.638 102.068 187.101 102.571
  188.43 107.267 208.613 108.145 218.283 107.814 224.451 108.022 239.054 107.476
 255.065  107.95 262.387 107.823 269.273 108.583 289.482  109.54 293.368 111.845
 308.097 116.978 314.794 118.841 319.795 119.088 323.379 120.572 326.006 120.855
#Mann= 3 ,-1 , 0
       0      .1       0 161.281    .036       0  188.43      .1       0
Levee=-1,161,110,-1,188.5,110,,
#XS Ineff= 4 ,-1
     .62  123.96  119.33  161.28  166.18   107.3  187.01   188.4   107.3
   239.3  322.86  119.77
Permanent Ineff=
       T       T       T       T
#Block Obstruct= 3 ,-1
    1.23   11.72  119.13  241.15  252.86  112.07  270.44  289.87   118.3
Bank Sta=161.281,188.43
XS Rating Curve= 0 ,0
Exp/Cntr=0.5,0.3

Type RM Length L Ch R = 1 ,6675.898,81.325,87.891,94.457
XS GIS Cut Line= 4
529753.5801596394780143.39904175529722.221959279 4780274.8000968
 529709.866534874780364.11424001 529672.411606344780455.16602867
#Sta/Elev= 30
       0 108.842  14.642 108.333  19.133  108.55   23.54 108.262  28.942 108.495
  60.906 108.274 127.348  107.54 140.819 107.773 157.841 107.355 161.555   107.2
 166.792 102.521 171.462 101.804  187.76 102.459 188.289 105.359   188.8   107.2
 188.802 107.353 208.548 107.842   220.8 107.868 225.507 107.536 267.996 107.809
 274.484 108.132 276.298 108.703 283.337 108.602 285.805  108.83 289.368 109.752
 293.302 111.579 309.243 117.018 317.737 118.845  320.98 118.945  323.71 119.799
#Mann= 3 ,-1 , 0
       0      .1       0 157.841    .036       0 188.802      .1       0
Levee=-1,161.555,110,-1,188.8,110,,
#XS Ineff= 4 ,-1
    1.54  126.74  115.97  161.85  166.91   107.2  187.74   188.8  107.35
   224.8   309.3  116.24
Permanent Ineff=
       T       T       T       T
#Block Obstruct= 2 ,-1
    3.08   12.33  112.69  228.81     247  112.64
Bank Sta=161.555,188.8
XS Rating Curve= 0 ,0
Exp/Cntr=0.5,0.3

Type RM Length L Ch R = 1 ,6588.007,112.76,111.994,111.228
XS GIS Cut Line= 3
529685.0109435714780221.88110906529562.2602542334780362.37751118
529488.8510944674780458.15569951
#Sta/Elev= 30
 104.217 108.207 148.948 107.753 156.662   107.6 157.016 104.676 157.198 103.073
 163.654  103.02 165.989  102.61 168.832 101.132 173.832  100.98 176.489 101.516
  177.28  102.61 177.301 102.912 177.316 105.792 194.932 106.401 201.311 105.756
 208.077 106.629 230.889 106.794 233.954 107.568 250.672 107.046 270.764 107.545
 287.943 107.186 307.312 107.356 308.755 107.887 312.005  110.61 313.432 111.242
 327.654 114.052 337.021 115.152 358.234  115.94 407.124 115.714 411.459 116.519
#Mann= 5 ,-1 , 0
 104.217      .1       0 148.948      .1       0 157.016    .036       0
 177.316      .1       0 287.943     .04       0
Levee=-1,156.662,110,-1,177.28,110,,
#XS Ineff= 2 ,-1
       0  146.69118.6233  177.98  227.31118.4967
Permanent Ineff=
       T       T
#Block Obstruct= 4 ,-1
   63.44   81.06  137.44  103.08  118.06  129.87  129.96  147.14  130.03
  177.97  195.59  126.35
Bank Sta=165.989,177.28
XS Rating Curve= 0 ,0
Exp/Cntr=0.3,0.1

Type RM Length L Ch R = 1 ,6476.012,76.73,75.552,74.374
XS GIS Cut Line= 3
529580.7708754214780167.78914113529526.3717219344780239.28517142
529453.4148841394780441.47983617
#Sta/Elev= 30
 197.332 107.507 199.368 108.185  217.28   107.2 218.508 105.827  219.12  105.02
 221.204  102.58 227.782 101.001 234.676 101.176  237.69 101.711 239.505  102.58
 242.323 105.137 243.573 105.928 245.751 106.173 246.152 106.659 256.204 106.064
 261.739 106.249 266.694 105.724  269.51  106.05 298.103 105.664 302.433 106.263
 364.093  106.11 383.228 107.159 402.152 107.405 409.741 107.575 415.122 112.568
 417.248 113.444 422.544 114.491 433.195 115.436 458.709 115.685 502.126 114.708
#Mann= 4 ,-1 , 0
 197.332      .1       0 218.508    .036       0 243.573      .1       0
 402.152     .04       0
Levee=-1,217.28,110,-1,243.639,110,,
#XS Ineff= 2 ,-1
  185.55  208.28  126.64  244.23  368.99  123.48
Permanent Ineff=
       T       T
#Block Obstruct= 5 ,-1
    8.99   34.36   118.2   45.46   62.38   128.6  198.24  207.22  126.27
  244.23  255.33   121.4  302.91  366.87  123.53
Bank Sta=219.12,242.323
XS Rating Curve= 0 ,0
Exp/Cntr=0.3,0.1

River Reach=IBAIZABAL       ,IBAIZABAL-100

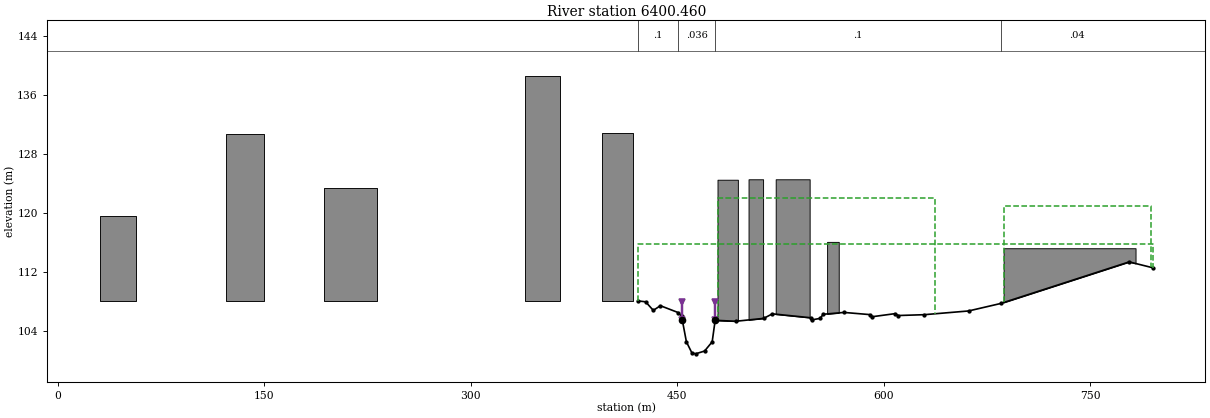
Type RM Length L Ch R = 1 ,6400.460,107.738,105.947,103.969
XS GIS Cut Line= 3
 529524.580314094780109.45072531529453.4589908724780226.44564855
529435.6967944674780463.10629951
#Sta/Elev= 30
 421.347 108.115 427.056 107.994 432.651 106.831   437.8 107.463 450.702 106.537
 453.167 106.052 453.707  105.53 456.706  102.57  460.62 101.097 463.346 100.944
 469.876  101.32  475.43  102.57 477.593 105.482 492.674 105.357 512.852 105.749
 519.161 106.361 547.261 105.828  547.96 105.551 553.811 105.743 556.152 106.303
 571.215 106.554 589.887  106.26 591.736 105.972 608.413 106.391 610.606 106.134
 629.517 106.247 661.696 106.751 685.083 107.765 778.445 113.398  795.59 112.605
#Mann= 4 ,-1 , 0
 421.347      .1       0 450.702    .036       0 477.593      .1       0
 685.083     .04       0
Levee=-1,453.707,108,-1,477.593,108,,
#XS Ineff= 3 ,-1
 421.347  415.86  115.89   479.3  637.53  122.03  687.58  794.01     121
Permanent Ineff=
       T       T       F
#Block Obstruct= 10 ,-1
   30.31   57.09  119.63  121.94  149.43  130.67  193.13  231.89  123.36
  339.74  365.11  138.61  395.42  417.97  130.83   479.3   494.1  124.53
  501.85  512.42  124.59  521.59  546.26  124.59  558.94   567.4  116.11
  687.22  783.08  115.25
Bank Sta=453.707,477.593
XS Rating Curve= 0 ,0
Exp/Cntr=0.5,0.3